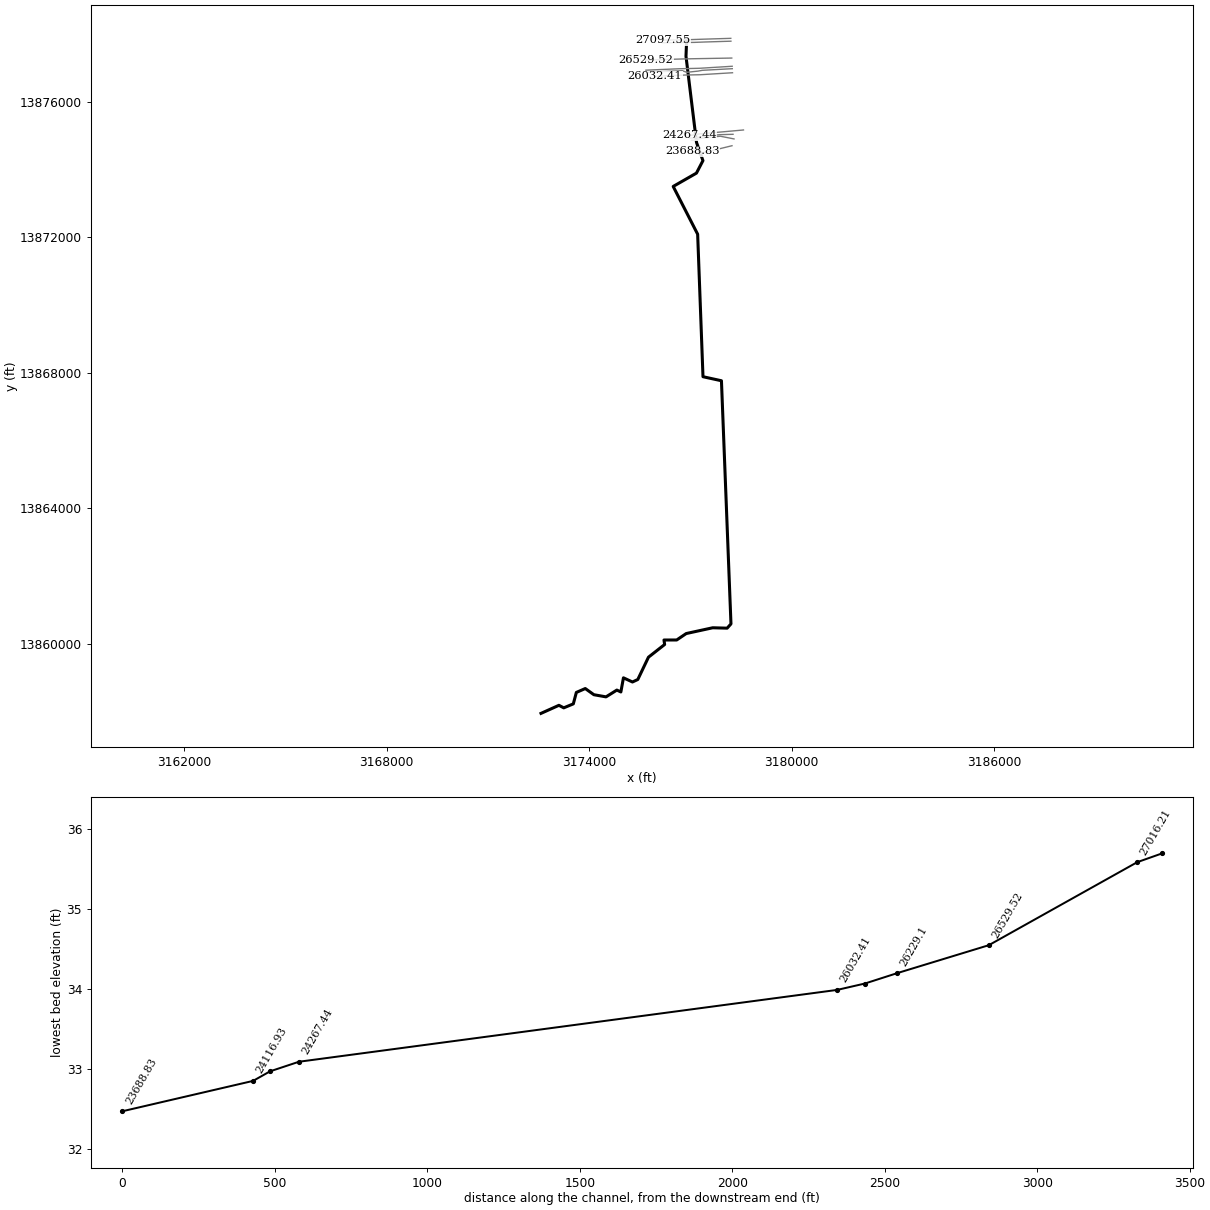
--- P107-00-00.prj (project) ---

Proj Title=P107-00-00
Current Plan=p02
Default Exp/Contr=.3,.1
English Units
Geom File=g01
Flow File=f02
Flow File=f01
Plan File=p01
Plan File=p02
Y Axis Title=Elevation
X Axis Title(PF)=Main Channel Distance
X Axis Title(XS)=Station
BEGIN DESCRIPTION:
HCFCD MODEL SUMMARY METADATA
The purpose of this summary is to document the high points of hydrologic and hydraulic models filed within the HCFCD Model and Map Management (M3) system.  The document includes references to the project that prompted the creation or update of the model.
DESCRIPTION OF PROJECT:
The following model was the hydraulic model which represented the effective condition of Harris County's watersheds.
PURPOSE OF PROJECT:
Development of effective models to support the National Flood Insurance Program.
HCFCD Watershed Unit ID: P
M3 Study Identifier: 2007_Effective_P
Engineer: HCFCD
Project Name: EffectiveFEMA Study for watershed Greens Bayou (P)
Study Completion Date: 6/18/2007
FEMA Case Number: [No Data]
FEMA Approval Date: [No Date in Database]
Vertical Datum: NAVD 1988
Datum Note: 2001 ADJ
HYDRAULICS
HCFCD Unit No.:  P107-00-00
Hydraulic Program Name: HEC-RAS
Hydraulic Program Version: 3.0.1
Steady Hydraulic Model: Yes
Unsteady Hydraulic Model: No
Update1:
The effective FEMA hydraulic model for unit number P107-00-00 has been updated by FEMA LOMR 12-06-1235P with an effective date of 9/5/2012.
Update2:
HCFCD Nomenclature Update 2014,  Effective date of 9/5/2012.
Update3:
The effective FEMA hydraulic model for unit number P107-00-00 has been updated by FEMA LOMR 16-06-3936P with an effective date of 9/18/2017.
END DESCRIPTION:
DSS Export Rating Curves= 0
DSS Export Rating Curve Sorted= 0
DSS Export Volume Flow Curves= 0
DXF Filename=..\..\Superseded\20170208\HEC-RAS_301\Test RAS 4.1.0\P107-00-00\P107-00-00.
DXF OffsetX= 0
DXF OffsetY= 0
DXF ScaleX= 1
DXF ScaleY= 10

--- P107-00-00.p02 (plan) ---

Plan Title=Effective Floodway 2019
Program Version=3.0.1
Short Identifier=Eff+LOMR FW
Geom File=g01
Flow File=f01
Subcritical Flow
K Sum by GR= 0
Std Step Tol= 0.01
Critical Tol= 0.01
Num of Std Step Trials= 20
Max Error Tol= 0.3
Flow Tol Ratio= 0.001
Split Flow NTrial= 30
Split Flow Tol= 0.02
Split Flow Ratio= 0.02
Log Output Level= 0
Friction Slope Method= 1
Unsteady Friction Slope Method= 2
Unsteady Bridges Friction Slope Method= 1
Parabolic Critical Depth
Global Vel Dist= 0 , 0 , 0
Global Log Level= 0
CheckData=True
Encroach Param=-1 ,0,0, 2
Encroach River=P107-00-00
Encroach Reach=P107-00-00_0010
Encroach Node=27097.55
       1 4896.38 5140.75
Encroach Node=27016.21
       1 4863.69 5119.68
Encroach Node=26769.56
       1 4794.94 5028.19
Encroach Node=26529.52
       1 4794.94 5028.19
Encroach Node=26229.1
       1 4885.78  5112.7
Encroach Node=26123.4
       1 4912.25  5236.8
Encroach Node=26032.41
       1 4875.04 5134.94
Encroach Node=25148.09
       1 4867.65 5122.15
Encroach Node=24267.44
       1 4867.65 5122.15
Encroach Node=24172.81
       1 4891.36 5156.31
Encroach Node=24116.93
       1 4857.65 5112.75
Encroach Node=23688.83
       1 4828.89 5124.04
Encroach Node=23528.31
       1  4862.1 5224.35
Encroach Node=23454.82
       1 4886.17 5242.21
Encroach Node=23233.63
       1  4934.6 5150.08
Encroach Node=23183.42
       1  4971.4  5028.1
Encroach Node=23133.3
       1  4971.4  5028.1
Encroach Node=22757.1
       1    4935    5030
Encroach Node=22185.3
       1    4983    5018
Encroach Node=22165.3
       1    4983    5018
Encroach Node=22145.3
       1    4983    5018
Encroach Node=22133.8
       1    4970    5023
Encroach Node=22057.3
       1    4970    5023
Encroach Node=21980.8
       1    4970    5023
Encroach Node=21823.7
       1  4960.7 5028.93
Encroach Node=21507.9
       1 4972.73 5028.93
Encroach Node=21497.4
       1 4972.73 5028.93
Encroach Node=21486.9
       1 4972.73 5028.93
Encroach Node=21476.0
       1 4972.73 5028.93
Encroach Node=21465.5
       1 4972.73 5028.93
Encroach Node=21226.5
       1  4978.8    5205
Encroach Node=20954.1
       1  4978.8    5235
Encroach Node=20904.1
       1  4978.8    5235
Encroach Node=20875.1
       1  4978.8    5235
Encroach Node=20846.1
       1  4978.8    5235
Encroach Node=20700.7
       1    4970    5250
Encroach Node=19812.5
       1    4930    5350
Encroach Node=18768.1
       1    4880    5120
Encroach Node=17762.0
       1    4850    5030
Encroach Node=17366
       1    3387 3498.32
Encroach Node=17111
       1 3514.35 3601.38
Encroach Node=17048
       1 3514.35 3750.38
Encroach Node=16984
       1 3563.28 3750.38
Encroach Node=16947
       1 3622.98 3773.85
Encroach Node=16830
       1 3248.86 3773.85
Encroach Node=16718
       1 3248.86 3461.98
Encroach Node=16675
       1 3222.62 3398.55
Encroach Node=16622
       1 3222.62 4100.72
Encroach Node=16569
       1 3999.23 4100.72
Encroach Node=16381.1
       1  4957.1  5042.7
Encroach Node=15777.9
       1  4977.1  5042.7
Encroach Node=15060.7
       1  4975.8  5060.8
Encroach Node=14503.9
       1  4975.8  5050.6
Encroach Node=13439.3
       1  4970.7  5048.7
Encroach Node=12644.9
       1 4974.75 5031.05
Encroach Node=12633.4
       1 4974.75 5031.05
Encroach Node=12621.9
       1 4974.75 5031.05
Encroach Node=12087.0
       1    4955 5069.31
Encroach Node=11740.0
       1 4962.75 5059.75
Encroach Node=11729.5
       1 4962.75 5059.75
Encroach Node=11719.0
       1 4962.75 5059.75
Encroach Node=11162.3
       1  4940.2 5059.22
Encroach Node=10460.3
       1 4954.52 5059.22
Encroach Node=10449.3
       1 4954.52 5059.22
Encroach Node=10438.3
       1 4954.52 5059.22
Encroach Node=9861.2
       1  4963.3  5052.9
Encroach Node=8925.0
       1  4963.3  5052.9
Encroach Node=8565.4
       1    4944  5069.9
Encroach Node=8393.5
       1    4944  5059.9
Encroach Node=7675.6
       1    4944  5059.9
Encroach Node=7336.1
       1    4944  5059.9
Encroach Node=7123.8
       1    4938 5075.11
Encroach Node=7083.8
       1    4938 5075.11
Encroach Node=7043.8
       1    4938 5075.11
Encroach Node=7002.0
       1 4923.83 5055.45
Encroach Node=6990.5
       1 4923.83 5058.45
Encroach Node=6979.0
       1 4923.83 5058.45
Encroach Node=6501.9
       1 4937.12  5054.8
Encroach Node=6344.4
       1    4955    5060
Encroach Node=6153.4
       1    4950    5050
Encroach Node=6124.4
       1    4950    5050
Encroach Node=6095.4
       1    4950    5050
Encroach Node=5440.2
       1  4920.1  5097.6
Encroach Node=4886.5
       1  4920.1  5097.6
Encroach Node=4397.0
       1    4945    5055
Encroach Node=3612.2
       1  4953.9  5134.6
Encroach Node=2594.3
       1  4886.4  5027.2
Encroach Node=1857.7
       1  4892.7  5102.1
Encroach Node=1567.5
       1  4892.6  5101.9
Encroach Node=1507.5
       1  4892.6  5101.9
Encroach Node=1447.5
       1  4892.6  5101.9
Encroach Node=1009.8
       1  4951.8  5152.9
BEGIN DESCRIPTION:
P107-00-00 Post-Project Conditions Floodway Model.
END DESCRIPTION:
Computation Interval=1HOUR
Output Interval=1HOUR
Instantaneous Interval=1HOUR
Mapping Interval=1HOUR
Run HTab= 0
Run UNet= 0
Run Sediment= 0
Run PostProcess= 0
Run WQNet= 0
Run RASMapper= 0
UNET Theta= 1
UNET Theta Warmup= 1
UNET ZTol= 0.02
UNET ZSATol= 0.1
UNET MxIter= 20
UNET Max Iter WO Improvement= 0
UNET MaxInSteps= 20
UNET DtIC= 0
UNET DtMin= 0
UNET MaxCRTS= 20
UNET WFStab= 2
UNET SFStab= 1
UNET WFX= 1
UNET SFX= 1
UNET DSS MLevel= 4
UNET Pardiso=0
UNET DZMax Abort= 100
UNET Use Existing IB Tables=-1
UNET Froude Reduction=False
UNET Froude Limit= 0.8
UNET Froude Power= 4
UNET Time Slicing=0,0, 5
UNET D1 Cores= 0
UNET D2 Coriolis=0
UNET D2 Cores= 0
UNET D2 Theta= 1
UNET D2 Theta Warmup= 1
UNET D2 Z Tol= 0.01
UNET D2 Volume Tol= 0.01
UNET D2 Max Iterations= 20
UNET D2 Equation= 0
UNET D2 RampUpFraction=0.1
UNET D2 TimeSlices= 1
UNET D2 BCVolumeCheck=0
UNET D1D2 MaxIter= 0
UNET D1D2 ZTol=0.01
UNET D1D2 QTol=0.1
UNET D1D2 MinQTol=1
DSS File=dss
Write IC File= 0
Write IC File at Fixed DateTime=0
IC Time=0,,
Write IC File at Sim End=0
Echo Input=False
Echo Parameters=False
Echo Output=False
Write Detailed= 0
HDF Write Warmup=0
HDF Write Time Slices=0
HDF Flush=0
HDF Face Node Velocities=0
HDF Compression= 1
HDF Chunk Size= 1
HDF Spatial Parts= 1
HDF Use Max Rows=0
HDF Fixed Rows= 1
Calibration Method= 0
Calibration Iterations= 20
Calibration Max Change=0.05
Calibration Tolerance=0.2
Calibration Maximum=1.5
Calibration Minimum=0.5
Calibration Optimization Method= 1
WQ AD Non Conservative
WQ ULTIMATE=-1
WQ Max Comp Step=1HOUR
WQ Output Interval=15MIN
WQ Output Selected Increments= 0
WQ Output face flow=0
WQ Output face velocity=0
WQ Output face area=0
WQ Output face dispersion=0
WQ Output cell volume=0
WQ Output cell surface area=0
WQ Output cell continuity=0
WQ Output cumulative cell continuity=0
WQ Output face conc=0
WQ Output face dconc_dx=0
WQ Output face courant=0
WQ Output face peclet=0
WQ Output face adv mass=0
WQ Output face disp mass=0
WQ Output cell mass=0
WQ Output cell source sink temp=0
WQ Output nsm pathways=0
WQ Output nsm derived pathways=0
WQ Output MaxMinRange=-1
WQ Daily Max Min Mean=-1
WQ Daily Range=0
WQ Daily Time=0
WQ Create Restart=0
WQ Fixed Restart=0
WQ System Summary=0
WQ Write To DSS=0
WQ Use Fixed Temperature=0
Sorting and Armoring Iterations= 10
XS Update Threshold= 0.02
Bed Roughness Predictor= 0
Hydraulics Update Threshold= 0.02
Energy Slope Method= 1
Volume Change Method= 1
Sediment Retention Method= 0
XS Weighting Method= 0
Number of US Weighted Cross Sections= 1
Number of DS Weighted Cross Sections= 1
Upstream XS Weight=0
Main XS Weight=1
Downstream XS Weight=0
Number of DS XS's Weighted with US Boundary= 1
Upstream Boundary Weight= 1
Weight of XSs Associated with US Boundary= 0
Number of US XS's Weighted with DS Boundary= 1
Downstream Boundary Weight= 0.5
Weight of XSs Associated with DS Boundary= 0.5
Percentile Method= 0
Sediment Output Level= 3
Mass or Volume Output= 0
Output Increment Type= 1
Profile and TS Output Increment= 1
XS Output Flag= 0
XS Output Increment= 10
Write Gradation File= 0
Read Gradation Hotstart= 0
Write HDF5 File= 1
Write DSS Sediment File= 0
SV Curve= 0
Specific Gage Flag= 0

--- P107-00-00.p01 (plan) ---

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Plan Title=Effective Multi-Profile 2019
Short Identifier=Eff+LOMR MP
Geom File=g01
Flow File=f02
P107-00-00 Post-Project Conditions Model.
Sediment Output Level= 4

--- P107-00-00.f01 (steady flow) ---

Flow Title=Effective Floodway 2019
Program Version=3.0.1
Number of Profiles= 2
Profile Names=1PCT_100yr,Floodway_100yrFW
River Rch & RM=P107-00-00,P107-00-00_0010 ,27097.55
     147     147
River Rch & RM=P107-00-00,P107-00-00_0010 ,27016.21
     156     156
River Rch & RM=P107-00-00,P107-00-00_0010 ,26229.1
     170     170
River Rch & RM=P107-00-00,P107-00-00_0010 ,26123.4
     201     201
River Rch & RM=P107-00-00,P107-00-00_0010 ,26032.41
     243     243
River Rch & RM=P107-00-00,P107-00-00_0010 ,24116.93
     258     258
River Rch & RM=P107-00-00,P107-00-00_0010 ,23688.83
     280     280
River Rch & RM=P107-00-00,P107-00-00_0010 ,23454.82
     289     289
River Rch & RM=P107-00-00,P107-00-00_0010 ,23233.63
     309     309
River Rch & RM=P107-00-00,P107-00-00_0010 ,22757.1
     342     342
River Rch & RM=P107-00-00,P107-00-00_0010 ,22185.3
     354     354
River Rch & RM=P107-00-00,P107-00-00_0010 ,22133.8
     364     364
River Rch & RM=P107-00-00,P107-00-00_0010 ,21823.7
     385     385
River Rch & RM=P107-00-00,P107-00-00_0010 ,21507.9
     405     405
River Rch & RM=P107-00-00,P107-00-00_0010 ,21226.5
     425     425
River Rch & RM=P107-00-00,P107-00-00_0010 ,20954.1
     433     433
River Rch & RM=P107-00-00,P107-00-00_0010 ,20904.1
     445     445
River Rch & RM=P107-00-00,P107-00-00_0010 ,20700.7
    1035    1035
River Rch & RM=P107-00-00,P107-00-00_0010 ,19812.5
    1192    1192
River Rch & RM=P107-00-00,P107-00-00_0010 ,18768.1
    1364    1364
River Rch & RM=P107-00-00,P107-00-00_0010 ,17762.0
    1523    1523
River Rch & RM=P107-00-00,P107-00-00_0010 ,16381.1
    1687    1687
River Rch & RM=P107-00-00,P107-00-00_0010 ,15777.9
    1742    1742
River Rch & RM=P107-00-00,P107-00-00_0010 ,15060.7
    1786    1786
River Rch & RM=P107-00-00,P107-00-00_0010 ,14503.9
    1874    1874
River Rch & RM=P107-00-00,P107-00-00_0010 ,13439.3
    1942    1942
River Rch & RM=P107-00-00,P107-00-00_0010 ,12644.9
    2024    2024
River Rch & RM=P107-00-00,P107-00-00_0010 ,11740.0
    2075    2075
River Rch & RM=P107-00-00,P107-00-00_0010 ,11162.3
    2141    2141
River Rch & RM=P107-00-00,P107-00-00_0010 ,10460.3
    2200    2200
River Rch & RM=P107-00-00,P107-00-00_0010 ,9861.2
    2294    2294
River Rch & RM=P107-00-00,P107-00-00_0010 ,8925.0
    2349    2349
River Rch & RM=P107-00-00,P107-00-00_0010 ,8393.5
    2426    2426
River Rch & RM=P107-00-00,P107-00-00_0010 ,7675.6
    2503    2503
River Rch & RM=P107-00-00,P107-00-00_0010 ,7002.0
    2604    2604
River Rch & RM=P107-00-00,P107-00-00_0010 ,6153.4
    2682    2682
River Rch & RM=P107-00-00,P107-00-00_0010 ,5440.2
    2749    2749
River Rch & RM=P107-00-00,P107-00-00_0010 ,4886.5
    2810    2810
River Rch & RM=P107-00-00,P107-00-00_0010 ,4397.0
    2911    2911
River Rch & RM=P107-00-00,P107-00-00_0010 ,3612.2
    3047    3047
River Rch & RM=P107-00-00,P107-00-00_0010 ,2594.3
    3190    3190
River Rch & RM=P107-00-00,P107-00-00_0010 ,1567.5
    3271    3271
Boundary for River Rch & Prof#=P107-00-00,P107-00-00_0010 , 1
Up Type= 0
Dn Type= 3
Dn Slope=0.002
Boundary for River Rch & Prof#=P107-00-00,P107-00-00_0010 , 2
Up Type= 0
Dn Type= 3
Dn Slope=0.002
DSS Import GetInterval= 0
DSS Import GetPeak= 0
DSS Import FillOption= 0

--- P107-00-00.f02 (steady flow) ---

Flow Title=Effective Multi-Profile 2019
Program Version=3.0.1
Number of Profiles= 4
Profile Names=10PCT_10yr, 2PCT_50yr, 1PCT_100yr, 0.2PCT_500yr
River Rch & RM=P107-00-00,P107-00-00_0010 ,27097.55
      85     126     147     208
River Rch & RM=P107-00-00,P107-00-00_0010 ,27016.21
      90     134     156     221
River Rch & RM=P107-00-00,P107-00-00_0010 ,26229.1
      98     146     170     241
River Rch & RM=P107-00-00,P107-00-00_0010 ,26123.4
     116     172     201     284
River Rch & RM=P107-00-00,P107-00-00_0010 ,26032.41
     140     208     243     344
River Rch & RM=P107-00-00,P107-00-00_0010 ,24116.93
     149     221     258     365
River Rch & RM=P107-00-00,P107-00-00_0010 ,23688.83
     162     240     280     397
River Rch & RM=P107-00-00,P107-00-00_0010 ,23454.82
     167     248     289     409
River Rch & RM=P107-00-00,P107-00-00_0010 ,23233.63
     178     265     309     437
River Rch & RM=P107-00-00,P107-00-00_0010 ,22757.1
     197     293     342     484
River Rch & RM=P107-00-00,P107-00-00_0010 ,22185.3
     204     304     354     502
River Rch & RM=P107-00-00,P107-00-00_0010 ,22133.8
     210     313     364     516
River Rch & RM=P107-00-00,P107-00-00_0010 ,21823.7
     222     331     385     546
River Rch & RM=P107-00-00,P107-00-00_0010 ,21507.9
     234     347     405     574
River Rch & RM=P107-00-00,P107-00-00_0010 ,21226.5
     245     365     425     602
River Rch & RM=P107-00-00,P107-00-00_0010 ,20954.1
     250     372     433     614
River Rch & RM=P107-00-00,P107-00-00_0010 ,20904.1
     256     381     445     630
River Rch & RM=P107-00-00,P107-00-00_0010 ,20700.7
     597     888    1035    1466
River Rch & RM=P107-00-00,P107-00-00_0010 ,19812.5
     687    1022    1192    1687
River Rch & RM=P107-00-00,P107-00-00_0010 ,18768.1
     786    1170    1364    1932
River Rch & RM=P107-00-00,P107-00-00_0010 ,17762.0
     878    1306    1523    2157
River Rch & RM=P107-00-00,P107-00-00_0010 ,16381.1
     975    1450    1687    2379
River Rch & RM=P107-00-00,P107-00-00_0010 ,15777.9
    1010    1501    1742    2444
River Rch & RM=P107-00-00,P107-00-00_0010 ,15060.7
    1038    1542    1786    2496
River Rch & RM=P107-00-00,P107-00-00_0010 ,14503.9
    1094    1623    1874    2598
River Rch & RM=P107-00-00,P107-00-00_0010 ,13439.3
    1137    1687    1942    2676
River Rch & RM=P107-00-00,P107-00-00_0010 ,12644.9
    1190    1764    2024    2771
River Rch & RM=P107-00-00,P107-00-00_0010 ,11740.0
    1223    1812    2075    2829
River Rch & RM=P107-00-00,P107-00-00_0010 ,11162.3
    1266    1875    2141    2905
River Rch & RM=P107-00-00,P107-00-00_0010 ,10460.3
    1303    1930    2200    2971
River Rch & RM=P107-00-00,P107-00-00_0010 ,9861.2
    1365    2019    2294    3077
River Rch & RM=P107-00-00,P107-00-00_0010 ,8925.0
    1401    2072    2349    3139
River Rch & RM=P107-00-00,P107-00-00_0010 ,8393.5
    1451    2145    2426    3225
River Rch & RM=P107-00-00,P107-00-00_0010 ,7675.6
    1501    2218    2503    3311
River Rch & RM=P107-00-00,P107-00-00_0010 ,7002.0
    1568    2315    2604    3422
River Rch & RM=P107-00-00,P107-00-00_0010 ,6153.4
    1619    2389    2682    3508
River Rch & RM=P107-00-00,P107-00-00_0010 ,5440.2
    1664    2454    2749    3581
River Rch & RM=P107-00-00,P107-00-00_0010 ,4886.5
    1704    2513    2810    3648
River Rch & RM=P107-00-00,P107-00-00_0010 ,4397.0
    1771    2610    2911    3757
River Rch & RM=P107-00-00,P107-00-00_0010 ,3612.2
    1862    2742    3047    3903
River Rch & RM=P107-00-00,P107-00-00_0010 ,2594.3
    1958    2881    3190    4057
River Rch & RM=P107-00-00,P107-00-00_0010 ,1567.5
    2012    2960    3271    4142
Boundary for River Rch & Prof#=P107-00-00,P107-00-00_0010 , 1
Up Type= 0
Dn Type= 3
Dn Slope=0.002
Boundary for River Rch & Prof#=P107-00-00,P107-00-00_0010 , 2
Up Type= 0
Dn Type= 3
Dn Slope=0.002
Boundary for River Rch & Prof#=P107-00-00,P107-00-00_0010 , 3
Up Type= 0
Dn Type= 3
Dn Slope=0.002
Boundary for River Rch & Prof#=P107-00-00,P107-00-00_0010 , 4
Up Type= 0
Dn Type= 3
Dn Slope=0.002
DSS Import GetInterval= 0
DSS Import GetPeak= 0
DSS Import FillOption= 0

--- P107-00-00.g01 (geometry) ---

Geom Title=P107-00-00 2019
Program Version=3.0.1

River Reach=P107-00-00      ,P107-00-00_0010
Reach XY= 30
       3176890.6     13877828.61      3176870.16     13877340.71
      3177182.64       13874796.      3177372.91     13874260.76
      3177180.25       13873892.        3176491.       13873499.
        3177216.       13872089.      3177374.25       13867883.
      3177921.28      13867763.7      3178203.53     13860586.97
      3178090.15     13860461.52       3177662.5       13860473.
      3176876.73     13860302.31      3176594.93     13860112.53
      3176218.16     13860111.73      3176237.46     13859979.06
      3175757.99     13859604.39        3175442.       13858946.
       3175283.7     13858872.93      3175016.52     13858995.61
      3174940.18     13858578.48       3174820.6     13858633.95
      3174500.09     13858433.67      3174140.75       13858497.
      3173885.09     13858679.36      3173620.64     13858564.85
      3173530.67     13858226.79      3173247.13     13858109.56
      3173103.82     13858184.27      3172572.95     13857946.38

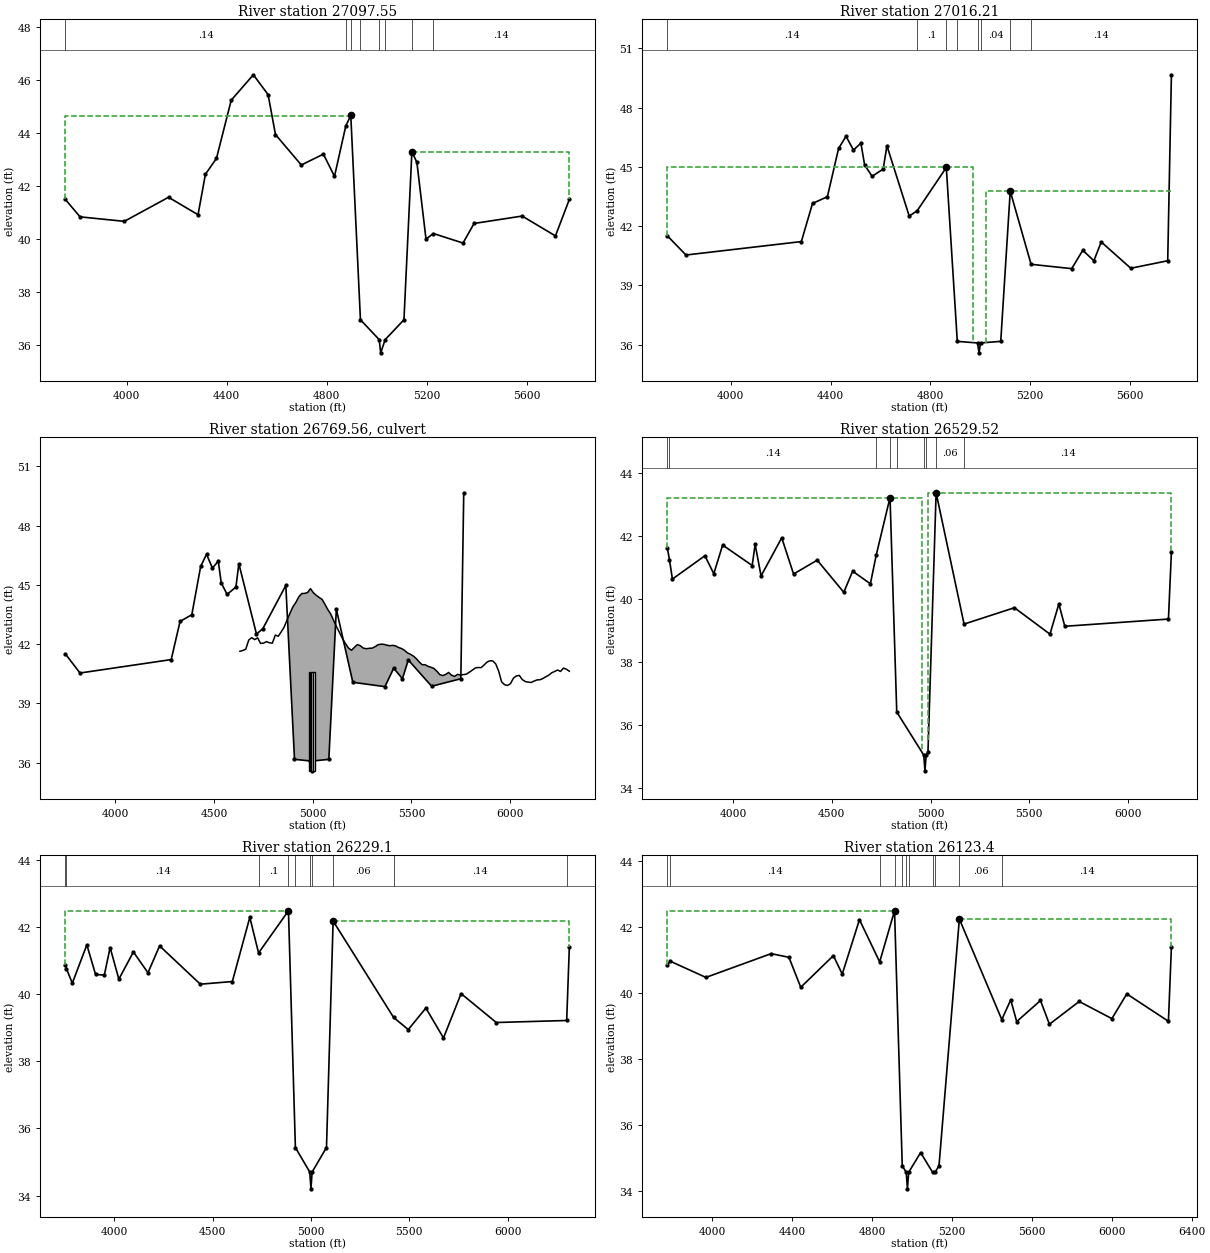
Type RM Length L Ch R = 1 ,27097.55,84.47,81.34,79.79
XS GIS Cut Line= 6
  3178198.35080413877870.2381956  3177446.693187 13877847.161142
 3176989.700006513877831.7599261 3176830.519878713877826.6198445
 3176194.516557513877818.8242564 3176183.348272813877818.9029964
#Sta/Elev= 30
 3754.69    41.5 3813.67   40.84 3990.62   40.67 4167.56   41.58 4285.52   40.92
 4315.01   42.45 4359.25   43.05 4418.23   45.25  4506.7   46.21  4565.7   45.46
  4595.2   43.95 4698.45    42.8 4786.95   43.21  4831.2   42.374876.375  44.275
4896.375  44.675    4935   36.95    5010    36.2    5016    35.7    5034    36.2
    5109   36.95 5140.75    43.3 5160.75    42.9 5197.18      40 5226.76   40.21
 5345.09   39.85 5389.47   40.59 5581.76   40.87 5714.89   40.12 5770.44    41.5
#Mann= 8 ,-1 , 0
 3754.69     .14       04876.375      .1       04896.375    .035       0
    4935     .04       0    5010    .018       0    5034     .04       0
 5140.75     .06       0 5226.76     .14       0
#XS Ineff= 2 , 0
       04896.375   44.67 5140.75       0    43.3
Permanent Ineff=
       T       T
Bank Sta=4896.375,5140.75
XS Rating Curve= 0 ,0
Exp/Cntr=0.3,0.1

Type RM Length L Ch R = 1 ,27016.21,481.88,486.69,484
BEGIN DESCRIPTION:
U/S of culvert at Tidwell Rd
END DESCRIPTION:
XS GIS Cut Line= 5
  3178202.20676713877785.9457133 3177442.349363713877762.6232533
 3177115.100018213877750.5110729 3176760.913718713877746.0540608
 3176184.138297413877739.8933119
#Sta/Elev= 30
 3746.48   41.51 3821.01   40.54  4283.1   41.22 4327.82   43.15 4387.45   43.49
 4432.16   45.93 4461.98   46.55 4491.79   45.85 4521.59    46.2 4536.47    45.1
 4566.24   44.52  4610.9   44.89 4625.78   46.07 4715.09   42.51 4746.99   42.78
4863.685   44.97 4907.68  36.171 4988.68   36.09 4994.68   35.59 5000.68   36.09
 5081.68  36.1715119.675   43.77 5203.17   40.07 5365.86   39.85 5410.23   40.78
  5454.6   40.25 5484.18    41.2  5602.5   39.87  5750.4   40.25 5765.19   49.66
#Mann= 8 ,-1 , 0
 3746.48     .14       0 4746.99      .1       04863.685    .035       0
 4907.68     .04       0 4988.68    .018       0 5000.68     .04       0
5119.675     .06       0 5203.17     .14       0
#XS Ineff= 2 , 0
       0    4970   44.97    5021       0   43.77
Permanent Ineff=
       T       T
Bank Sta=4863.685,5119.675
XS Rating Curve= 0 ,0
Exp/Cntr=0.5,0.3

Type RM Length L Ch R = 2 ,26769.56,,,
BEGIN DESCRIPTION:
TIDWELL ROAD
END DESCRIPTION:
Bridge Culvert--1,0,-1,-1, 0
Deck Dist Width WeirC Skew NumUp NumDn MinLoCord MaxHiCord MaxSubmerge Is_Ogee
131,180,3,0, 115, 123, , , 0.95, 0, 2,2,,
 4631.12 4646.06    4661 4675.94 4690.88 4705.82 4720.76  4735.7 4750.64 4765.58
 4780.52 4795.46  4810.4 4825.34 4840.18 4855.02 4869.87 4884.71 4899.55 4914.39
 4929.23 4944.08 4958.92 4973.76  4988.6 5003.45 5018.29 5033.13 5047.97 5062.81
 5077.66 5081.15  5092.5 5107.34 5109.74 5122.18 5137.02 5151.87 5166.71 5181.55
 5196.47 5211.38  5226.3 5241.21 5256.13 5271.04 5285.96 5300.87 5315.79  5330.7
 5345.62 5360.53 5375.45 5390.37 5405.28  5420.2 5435.11 5450.03 5464.94 5479.86
 5494.77 5509.69  5524.6 5539.52 5554.43 5569.35 5584.26 5599.18  5614.1 5629.01
 5643.93 5658.84 5673.76 5688.67 5703.59  5718.5 5733.42 5748.33 5763.25 5778.16
 5793.08 5807.99 5822.91 5837.83 5852.74 5867.66 5882.57 5897.49  5912.4 5927.32
 5942.23 5957.15 5972.06 5986.98 6001.89 6016.81 6031.73 6046.64 6061.56 6076.47
 6091.39  6106.3 6121.22 6136.13 6151.05 6165.96 6180.88 6195.79 6210.71 6225.63
 6240.54 6255.46 6270.37 6285.29  6300.2
   41.64   41.68   41.75   42.21   42.33   42.23   42.32   42.04   42.05   42.13
   42.07   42.05   42.46    42.4   42.62   42.86   43.22   43.56   43.89   44.11
   44.39   44.56   44.57   44.61   44.81    44.6   44.47   44.36   44.26      44
   43.73   43.68    43.5   43.17   43.11   42.85   42.56   42.26   42.02    41.8
   41.69   41.84   41.98   41.92    41.8   41.77   41.79    41.8   41.87   41.97
      42   41.99   41.95   41.92   41.94   41.91   41.83   41.78   41.69   41.56
   41.49    41.4   41.27    41.1   40.96   40.96   40.88   40.83   40.77   40.63
   40.46   40.41   40.47   40.57   40.43   40.37   40.47   40.44   40.46   40.48
   40.58   40.68   40.79   40.82   40.81   40.94   41.09   41.16   41.15      41
   40.63   40.09   39.95   39.91      40   40.28   40.39   40.42   40.21   40.11
   40.08   40.06   40.13   40.19    40.2   40.26   40.35   40.43   40.55   40.62
   40.69   40.62   40.79   40.73   40.63
                                                                                
                                                                                
                                                                                
                                                                                
                                                                                
                                                                                
                                                                                
                                                                                
                                                                                
                                                                                
                                                                                
                                        
  4511.6 4526.54 4541.48 4556.42 4571.36  4586.3 4601.24 4616.18 4631.12 4646.06
    4661 4675.94 4690.88 4705.82 4720.76  4735.7 4750.64 4765.58 4780.52 4795.46
  4810.4 4825.34 4840.18 4855.02 4869.87 4884.71 4899.55 4914.39 4929.23 4944.08
 4958.92 4973.76  4988.6 5003.45 5018.29 5033.13 5047.97 5062.81 5077.66 5081.15
  5092.5 5107.34 5109.74 5122.18 5137.02 5151.87 5166.71 5181.55 5196.47 5211.38
  5226.3 5241.21 5256.13 5271.04 5285.96 5300.87 5315.79  5330.7 5345.62 5360.53
 5375.45 5390.37 5405.28  5420.2 5435.11 5450.03 5464.94 5479.86 5494.77 5509.69
  5524.6 5539.52 5554.43 5569.35 5584.26 5599.18  5614.1 5629.01 5643.93 5658.84
 5673.76 5688.67 5703.59  5718.5 5733.42 5748.33 5763.25 5778.16 5793.08 5807.99
 5822.91 5837.83 5852.74 5867.66 5882.57 5897.49  5912.4 5927.32 5942.23 5957.15
 5972.06 5986.98 6001.89 6016.81 6031.73 6046.64 6061.56 6076.47 6091.39  6106.3
 6121.22 6136.13 6151.05 6165.96 6180.88 6195.79 6210.71 6225.63 6240.54 6255.46
 6270.37 6285.29  6300.2
   40.78   40.76   40.79   40.84   41.01   41.21    41.1   41.41   41.64   41.68
   41.75   42.21   42.33   42.23   42.32   42.04   42.05   42.13   42.07   42.05
   42.46    42.4   42.62   42.86   43.22   43.56   43.89   44.11   44.39   44.56
   44.57   44.61   44.81    44.6   44.47   44.36   44.26      44   43.73   43.68
    43.5   43.17   43.11   42.85   42.56   42.26   42.02    41.8   41.69   41.84
   41.98   41.92    41.8   41.77   41.79    41.8   41.87   41.97      42   41.99
   41.95   41.92   41.94   41.91   41.83   41.78   41.69   41.56   41.49    41.4
   41.27    41.1   40.96   40.96   40.88   40.83   40.77   40.63   40.46   40.41
   40.47   40.57   40.43   40.37   40.47   40.44   40.46   40.48   40.58   40.68
   40.79   40.82   40.81   40.94   41.09   41.16   41.15      41   40.63   40.09
   39.95   39.91      40   40.28   40.39   40.42   40.21   40.11   40.08   40.06
   40.13   40.19    40.2   40.26   40.35   40.43   40.55   40.62   40.69   40.62
   40.79   40.73   40.63
                                                                                
                                                                                
                                                                                
                                                                                
                                                                                
                                                                                
                                                                                
                                                                                
                                                                                
                                                                                
                                                                                
                                                                                
                        
BR Coef=-1 , 0 , 0 ,, 0 ,,,0.8,-1,,0,
WSPro=,,,, 1 ,,,, 0 ,,,, 0 ,,,,-1 ,-1 ,-1 , 0 , 0 , 0 , 0 , 0
Multiple Barrel Culv=2,5,9,452,0.015,0.4,1,9,2,35.59,35.25, 3,Culvert #1  , 0 ,1
    4984    4961    4995    4972    5006    4983
Culvert Bottom n=0.015
BC Design=,, 0 ,, 0 ,,,,,,
BC HTab HWMax=46.2
BC Use User HTab Curves=0
BC User HTab FreeFlow(D)= 0

Type RM Length L Ch R = 1 ,26529.52,286.93,300.42,286.66
BEGIN DESCRIPTION:
D/S of culvert at Tidwell Rd
END DESCRIPTION:
XS GIS Cut Line= 5
  3178227.22771513877288.4995297 3178216.6713059 13877287.929977
  3177140.18986313877269.4621662 3176785.849036313877262.0428897
 3175677.181634213877227.4031952
#Sta/Elev= 30
 3668.13   41.63  3678.7   41.25 3693.65   40.64 3858.14   41.38    3903   40.81
 3947.86   41.72 4097.39   41.07 4112.35   41.74 4142.25   40.74 4246.93   41.95
 4306.74    40.8 4426.37   41.24 4560.95   40.22 4605.81   40.89 4695.53   40.49
 4725.43   41.414794.935   43.23    4829  36.417  4965.7   35.05  4971.7   34.55
  4977.7   35.05    4987  35.1435028.185   43.38 5169.72   39.21 5424.54   39.73
 5604.41   38.89 5649.38   39.85 5679.36   39.14 6203.98   39.37 6218.97    41.5
#Mann= 9 ,-1 , 0
 3668.13      .2       0  3678.7     .14       0 4725.43      .1       0
4794.935    .035       0    4829     .04       0  4965.7    .018       0
  4977.7     .04       05028.185     .06       0 5169.72     .14       0
#XS Ineff= 2 , 0
       0    4955   43.23    4989       0   43.38
Permanent Ineff=
       T       T
Bank Sta=4794.935,5028.185
XS Rating Curve= 0 ,0
Exp/Cntr=0.5,0.3

Type RM Length L Ch R = 1 ,26229.1 ,92.2,105.7,102.2
XS GIS Cut Line= 6
  3178239.43143113877045.8730464 3178233.504605513877045.5334802
 3177274.307048913876986.4400944  3176677.79708713876972.8551479
 3175695.0749711 13876931.068486 3175681.556953513876930.6498517
#Sta/Elev= 30
 3752.07   40.86 3758.01   40.75 3787.57   40.32 3861.49   41.46 3905.85   40.58
  3950.2   40.56 3979.77   41.38 4024.13   40.44 4098.05   41.25 4171.98   40.63
 4231.12   41.43  4438.1   40.29 4600.74   40.37 4689.45   42.28 4733.93   41.22
4885.775  42.475    4921   35.43    4994    34.7    5000    34.2    5006    34.7
    5079   35.43  5112.7   42.17 5420.01    39.3 5494.52   38.94 5583.94   39.58
 5673.36   38.69 5762.78   40.01 5941.62   39.15  6299.3   39.21 6312.82    41.4
#Mann= 10 ,-1 , 0
 3752.07      .2       0 3758.01     .14       0 4733.93      .1       0
4885.775    .035       0    4921     .04       0    4994    .018       0
    5006     .04       0  5112.7     .06       0 5420.01     .14       0
  6299.3      .2       0
#XS Ineff= 2 , 0
       04885.775  42.475  5112.7       0   42.17
Permanent Ineff=
       T       T
Bank Sta=4885.775,5112.7
XS Rating Curve= 0 ,0
Exp/Cntr=0.3,0.1

Type RM Length L Ch R = 1 ,26123.4 ,98.26,90.99,87.88
XS GIS Cut Line= 6
  3178243.01803813876974.5339503 3177353.997834413876926.2722358
 3177227.8501208 13876903.100038  3176890.58012613876867.0600839
  3176761.855974 13876915.974028 3175735.226793713876868.3868528
#Sta/Elev= 30
 3775.09   40.86 3789.93   40.97 3967.99   40.48 4294.45    41.2 4383.48   41.09
 4442.84   40.18 4606.06   41.14 4650.58   40.58 4736.67   42.23 4837.92   40.95
 4912.25    42.5  4950.9   34.77  4970.9   34.57  4976.9   34.07  4982.9   34.57
  5042.9   35.17  5102.9   34.57  5114.9   34.57  5134.9   34.77  5236.8   42.25
 5449.31    39.2 5493.99    39.8 5523.78   39.14 5642.94   39.78 5687.62   39.06
 5836.57   39.75 6000.41   39.23 6074.88   39.98 6283.41   39.15  6298.3    41.4
#Mann= 11 ,-1 , 0
 3775.09      .2       0 3789.93     .14       0 4837.92      .1       0
 4912.25    .035       0  4950.9     .04       0  4970.9    .018       0
  4982.9     .04       0  5102.9    .018       0  5114.9     .04       0
  5236.8     .06       0 5449.31     .14       0
#XS Ineff= 2 , 0
       0 4912.25    42.5  5236.8       0   42.25
Permanent Ineff=
       T       T
Bank Sta=4912.25,5236.8
XS Rating Curve= 0 ,0
Exp/Cntr=0.3,0.1

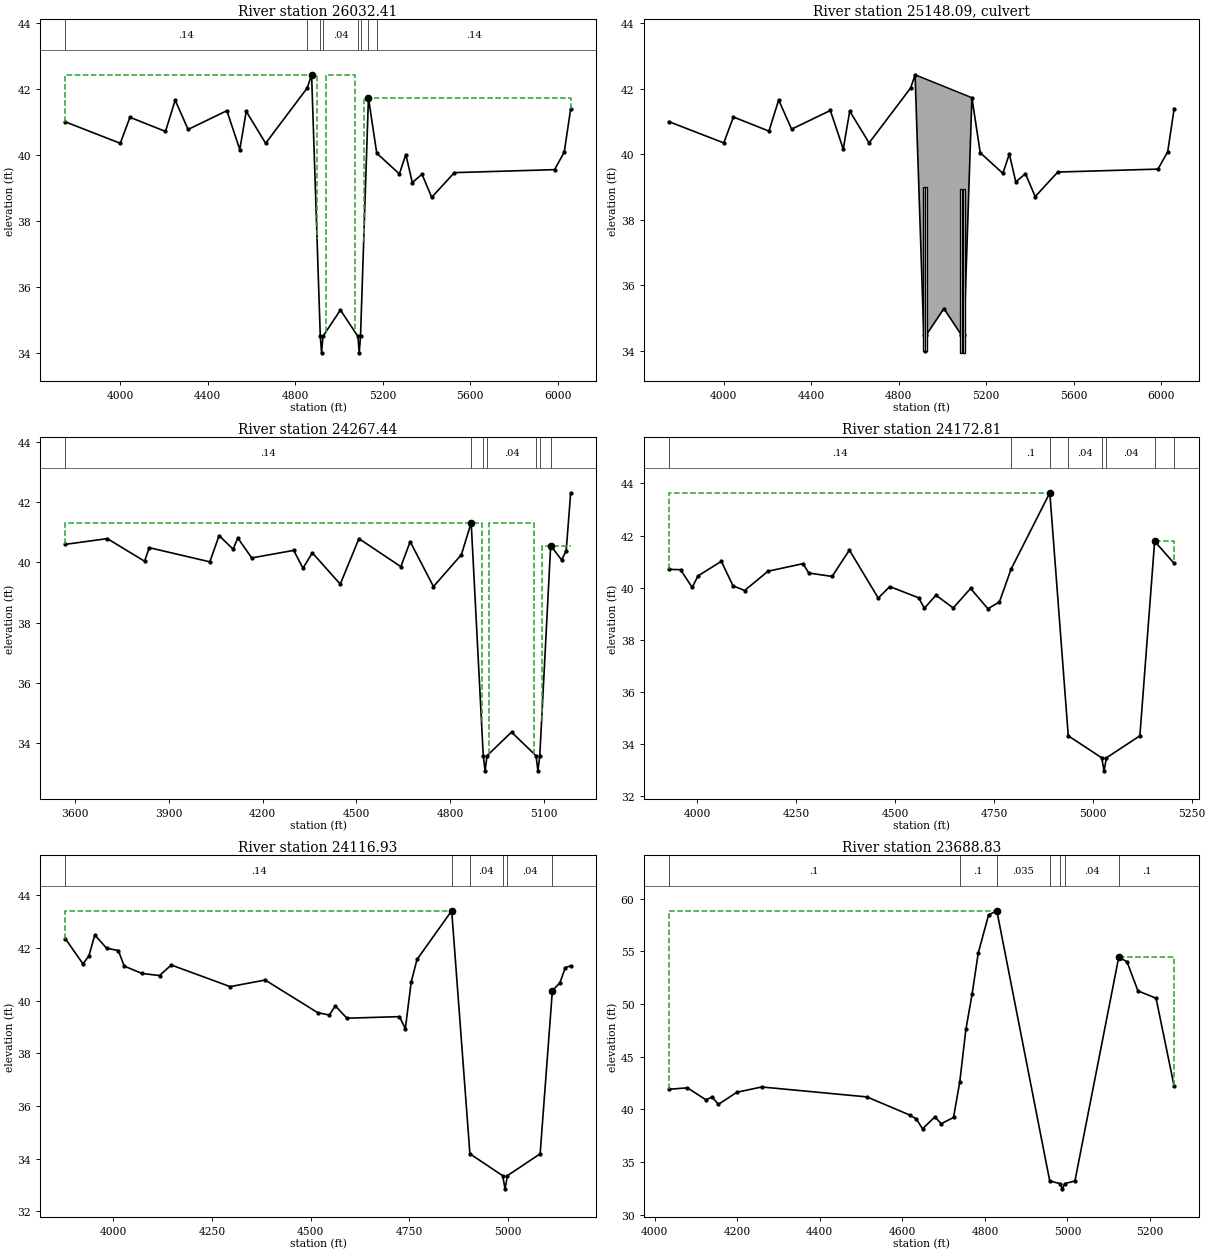
Type RM Length L Ch R = 1 ,26032.41,1760.07,1764.97,1791.79
BEGIN DESCRIPTION:
U/S of Culvert between ponds
END DESCRIPTION:
XS GIS Cut Line= 4
  3178249.144666   13876854.7169 3177290.8299817   13876795.9211
 3176856.6123462   13876787.3847 3175940.9721171    13876747.958
#Sta/Elev= 30
 3748.97      41 4000.08   40.35 4044.39   41.14 4206.87   40.71 4251.18   41.66
 4310.27   40.77 4487.52   41.34 4546.61   40.16 4576.15   41.32 4664.77   40.35
 4855.04   42.03 4875.04   42.43 4914.74   34.49 4920.74   33.99 4926.74   34.49
 5006.74   35.29 5086.74   34.49 5092.74   33.99 5098.74   34.49 5134.94   41.73
 5172.95   40.05 5276.43   39.42 5305.99   40.01 5335.55   39.16  5379.9   39.41
 5424.25   38.71 5527.72   39.46 5985.96   39.55 6030.31   40.08 6059.87    41.4
#Mann= 8 ,-1 , 0
 3748.97     .14       0 4855.04      .1       0 4914.74    .018       0
 4926.74     .04       0 5086.74    .018       0 5098.74     .04       0
 5134.94     .06       0 5172.95     .14       0
#XS Ineff= 3 ,-1
 3748.97    4900   42.43    4941    5072   42.43    5113 6059.87   41.73
Permanent Ineff=
       F       F       F
Bank Sta=4875.04,5134.94
XS Rating Curve= 0 ,0
Exp/Cntr=0.5,0.3

Type RM Length L Ch R = 2 ,25148.09,,,
BEGIN DESCRIPTION:
NB & SB Mainlanes
END DESCRIPTION:
Bridge Culvert--1,0,-1,-1, 0
Deck Dist Width WeirC Skew NumUp NumDn MinLoCord MaxHiCord MaxSubmerge Is_Ogee
50,1664,3,0, 2, 2, , , 0.95, 0, 2,2,,
 4875.04 5134.94
   42.43   41.73
                
 4867.65 5122.15
   41.32   40.56
                
BR Coef=-1 , 0 , 0 ,, 0 ,,,0.8,-1,,0,
WSPro=,,,, 1 ,,,, 0 ,,,, 0 ,,,,-1 ,-1 ,-1 , 0 , 0 , 0 , 0 , 0
Multiple Barrel Culv=2,5,9,1763,0.015,0.4,1,9,2,33.99,33.09, 2,SB FR       , 0 ,1
 4915.24  4906.8 4926.24  4917.8
Culvert Bottom n=0.015
Multiple Barrel Culv=2,5,9,1721,0.015,0.4,1,9,2,33.94,33.09, 2,NB FR       , 0 ,43
 5087.24  5075.8 5098.24  5086.8
Culvert Bottom n=0.015
BC Design=,, 0 ,, 0 ,,,,,,
BC HTab HWMax=42.43
BC Use User HTab Curves=0
BC User HTab FreeFlow(D)= 0

Type RM Length L Ch R = 1 ,24267.44,89.93,94.63,86.34
BEGIN DESCRIPTION:
D/S of culvert between ponds
END DESCRIPTION:
XS GIS Cut Line= 4
  3178574.61973613875165.3794321 3177266.971433613875048.6529595
 3176994.197044813875004.8200419 3176965.380501413875004.0661064
#Sta/Elev= 30
  3568.3    40.6 3702.57   40.79 3821.92   40.04 3836.84   40.49 4030.78   40.02
 4060.62   40.89 4105.37   40.44 4120.29   40.81 4165.05   40.15 4299.32    40.4
 4329.16   39.81 4358.99   40.32  4448.5   39.28 4508.18   40.79 4642.45   39.86
 4672.29   40.69 4746.88    39.2 4836.39   40.26 4867.65   41.32  4906.3   33.59
  4912.3   33.09  4918.3   33.59  4996.8  34.375  5075.3   33.59  5081.3   33.09
  5087.3   33.59 5122.15   40.56 5157.42   40.08 5171.83   40.39 5186.25   42.31
#Mann= 7 ,-1 , 0
  3568.3     .14       0 4867.65    .035       0  4906.3    .018       0
  4918.3     .04       0  5075.3    .018       0  5087.3     .04       0
 5122.15      .1       0
#XS Ineff= 3 ,-1
  3568.3    4901   41.32    4924    5070   41.32    5093 5186.25   40.56
Permanent Ineff=
       F       F       F
Bank Sta=4867.65,5122.15
XS Rating Curve= 0 ,0
Exp/Cntr=0.5,0.3

Type RM Length L Ch R = 1 ,24172.81,46.16,55.88,69.45
XS GIS Cut Line= 5
  3178265.30342613875037.7405798   3177867.4364413875026.7556936
 3177403.230019413874978.9496869 3177130.173150813874930.3100204
 3176995.086478713874927.3024804
#Sta/Elev= 30
 3928.48    40.7 3957.96   40.69 3987.45   40.01 4002.19   40.45 4061.15   41.01
 4090.64   40.07 4120.12   39.89 4179.08   40.63 4267.53   40.92 4282.27   40.56
 4341.08   40.43 4384.83   41.44 4457.75    39.6 4486.91   40.04 4559.83   39.61
 4574.41   39.21 4603.58   39.71 4647.33   39.22 4691.08   39.97 4734.83   39.19
 4763.99   39.45 4793.16    40.74891.355   43.64 4937.98  34.315 5022.48   33.47
 5028.48   32.97 5034.48   33.47 5118.98  34.3155156.305   41.78 5205.64   40.93
#Mann= 8 ,-1 , 0
 3928.48     .14       0 4793.16      .1       04891.355    .035       0
 4937.98     .04       0 5022.48    .018       0 5034.48     .04       0
5156.305      .1       0 5205.64     .99       0
#XS Ineff= 2 , 0
       0 4891.35   43.64 5156.31       0   41.78
Permanent Ineff=
       T       T
Bank Sta=4891.355,5156.305
XS Rating Curve= 0 ,0
Exp/Cntr=0.5,0.3

Type RM Length L Ch R = 1 ,24116.93,429.72,428.1,435.36
XS GIS Cut Line= 6
  3178294.22134713874901.4783851 3177884.4990699 13874981.844038
 3177354.648751713874925.8405411 3177259.359900313874901.7398675
 3177086.680127513874860.8800411 3177032.159239213874860.5716428
#Sta/Elev= 30
 3878.63   42.35 3923.37   41.39 3938.28    41.7 3953.19   42.49 3983.01   41.99
 4012.84    41.9 4027.75   41.31 4072.48   41.03 4117.22   40.95 4147.04   41.35
 4296.16   40.53 4384.96   40.78 4518.16   39.54 4547.76   39.45 4562.56    39.8
 4592.16   39.33 4725.36   39.39 4740.16   38.93 4754.96    40.7 4769.76   41.56
 4857.65   43.41  4903.8   34.18  4986.8   33.35  4992.8   32.85  4998.8   33.35
  5081.8   34.18 5112.75   40.37 5131.96   40.68 5145.59   41.25 5159.22   41.32
#Mann= 6 ,-1 , 0
 3878.63     .14       0 4857.65    .035       0  4903.8     .04       0
  4986.8    .018       0  4998.8     .04       0 5112.75      .1       0
#XS Ineff= 2 , 0
       0 4857.66   43.41 5159.22       0   41.32
Permanent Ineff=
       T       T
Bank Sta=4857.65,5112.75
XS Rating Curve= 0 ,0
Exp/Cntr=0.3,0.1

Type RM Length L Ch R = 1 ,23688.83,288.24,160.52,139.52
XS GIS Cut Line= 3
  3178234.05676913874700.7763587 3177244.113539713874459.3270384
 3177055.655583313874539.1146085
#Sta/Elev= 30
  4034.7   41.91 4079.65   42.05 4124.61   40.91 4139.59   41.18 4154.58   40.48
 4199.53   41.63 4259.47   42.13 4514.21   41.19 4619.11   39.45 4634.09   39.09
 4649.07   38.16 4679.04    39.3 4694.03   38.64    4724   39.24 4738.98   42.56
 4753.97   47.59 4768.95   50.92 4783.94   54.844808.885   58.444828.885   58.84
 4957.01  33.215 4981.51   32.97 4987.51   32.47 4993.51   32.97 5018.01  33.215
5124.035   54.425144.035   54.02 5170.61   51.24 5214.46   50.55 5258.31   42.19
#Mann= 7 ,-1 , 0
  4034.7      .1       0 4738.98      .1       04828.885    .035       0
 4957.01     .04       0 4981.51    .018       0 4993.51     .04       0
5124.035      .1       0
#XS Ineff= 2 , 0
       0 4828.88   58.84 5124.04       0   54.42
Permanent Ineff=
       T       T
Bank Sta=4828.885,5124.035
XS Rating Curve= 0 ,0
Exp/Cntr=0.3,0.1