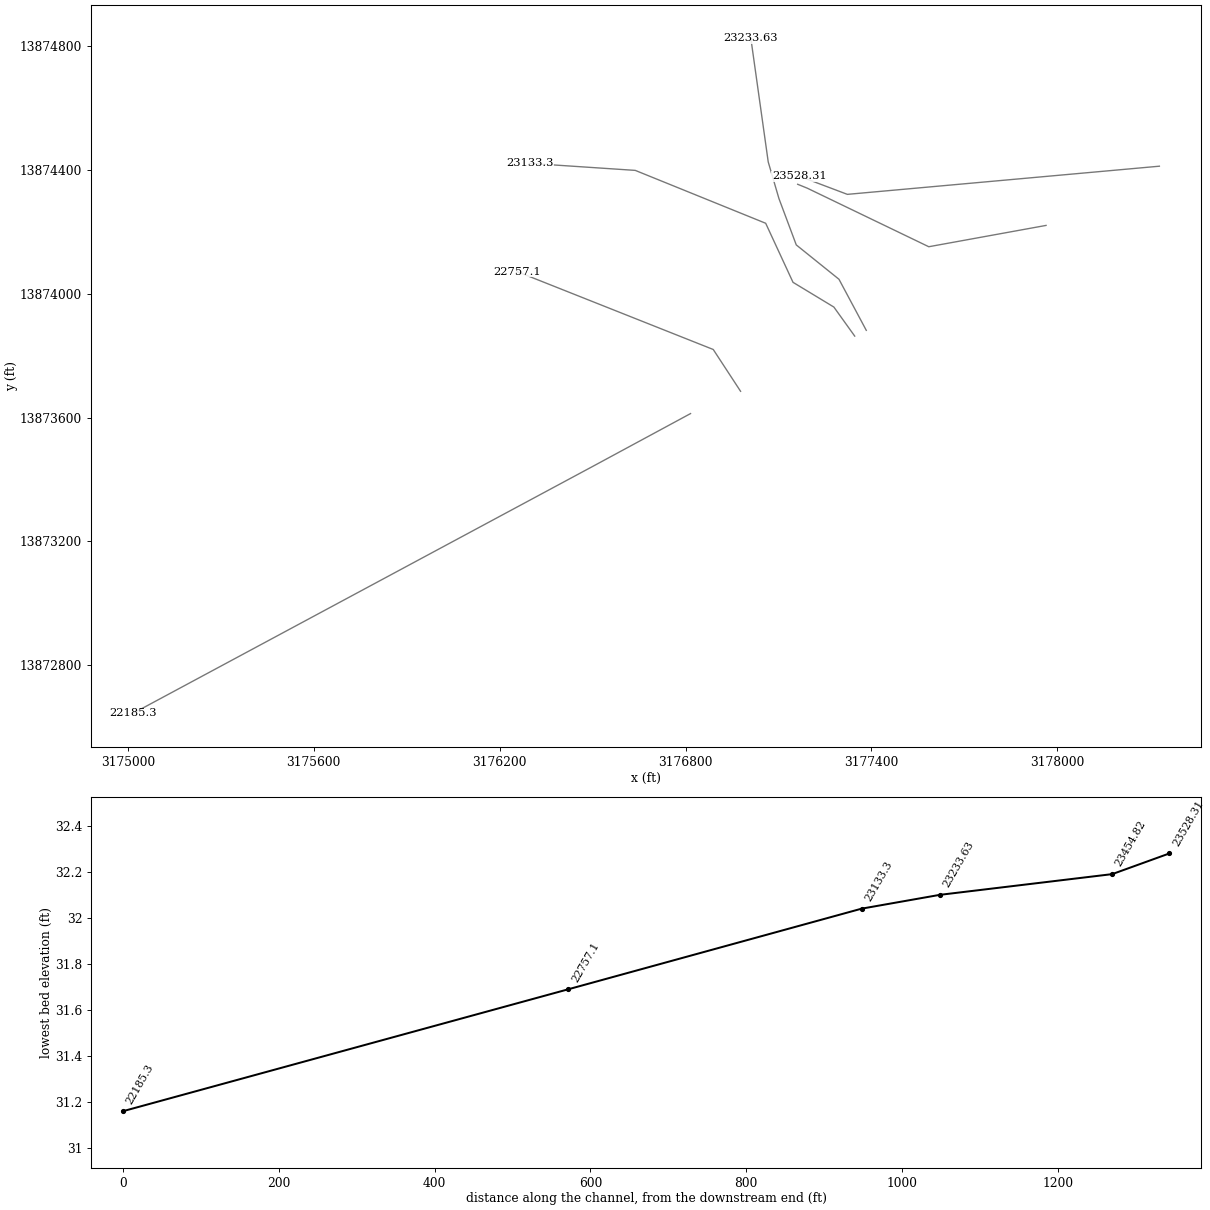
HEC-RAS study P107-00-00.prj: P107-00-00

--- P107-00-00.g01 (geometry) --- (continued)

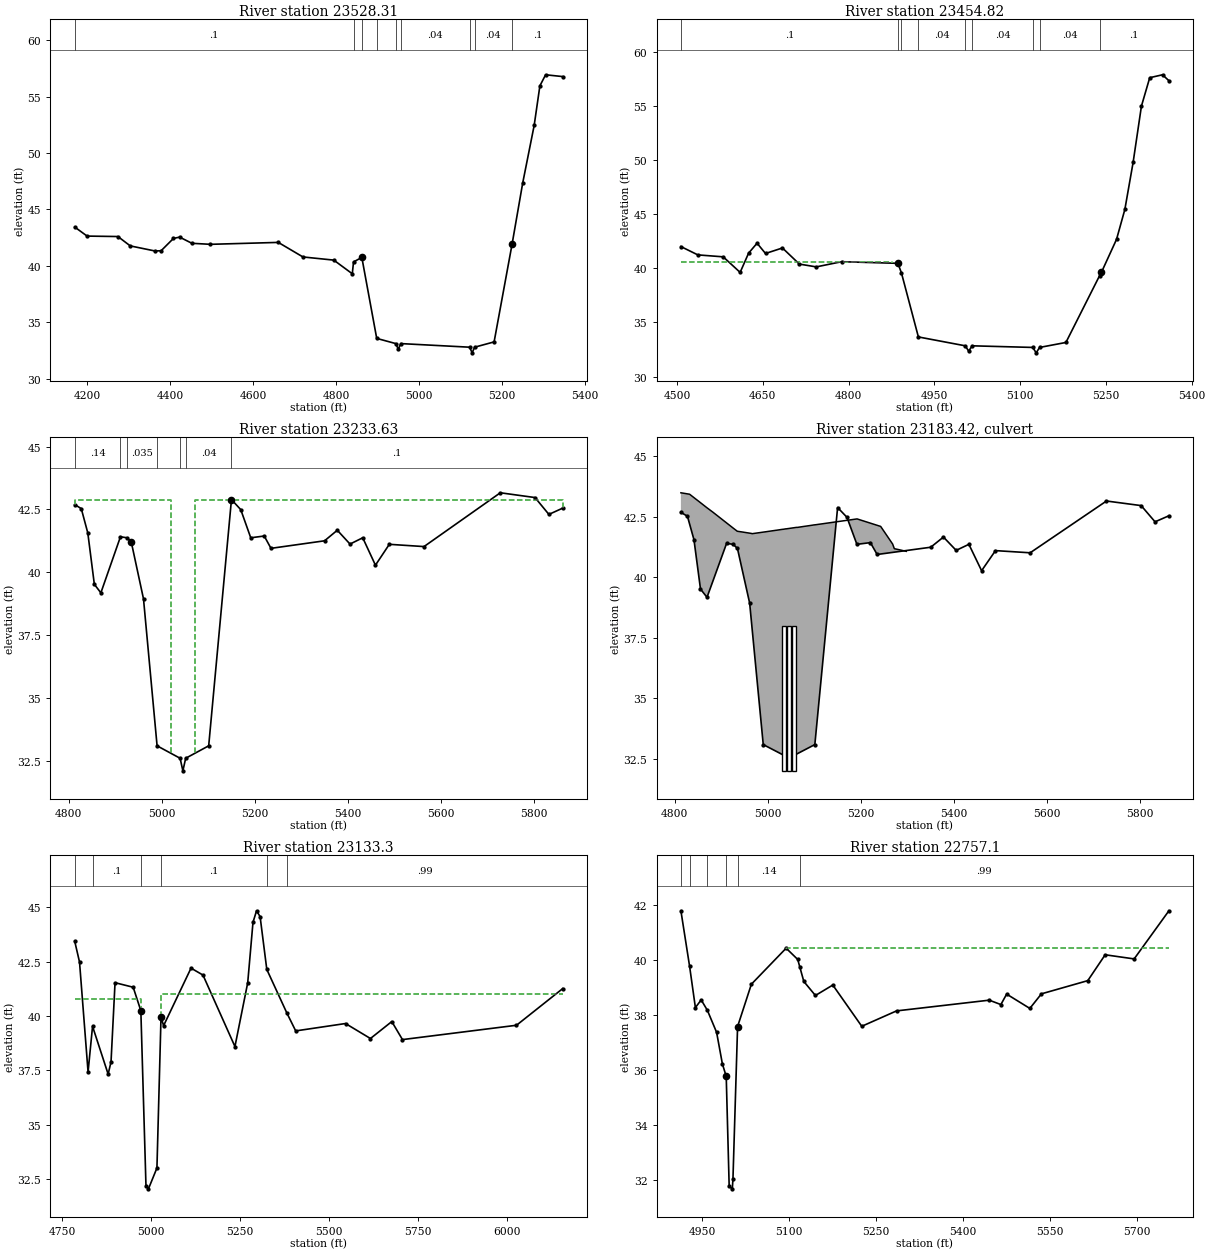
Type RM Length L Ch R = 1 ,23528.31,234.04,73.49,37.35
XS GIS Cut Line= 3
  3178329.21635613874411.0371088 3177322.229525213874320.1383404
 3177167.473929213874378.6280528
#Sta/Elev= 30
    4170   43.43 4199.74   42.63 4274.08   42.59 4303.82   41.76 4363.29   41.31
 4378.16   41.33  4407.9   42.42 4422.77   42.54 4452.51   41.99 4497.11    41.9
 4660.67   42.07 4720.15   40.78 4794.49    40.5  4839.1   39.29  4842.1   40.34
  4862.1   40.74    4898   33.56    4944    33.1    4950    32.6    4956    33.1
    5122   32.78    5128   32.28    5134   32.78    5181   33.25 5224.35   41.92
 5250.01   47.35 5277.59   52.44 5291.37   55.95 5305.16   56.93 5346.52   56.77
#Mann= 9 ,-1 , 0
    4170      .1       0  4842.1     .01       0  4862.1    .035       0
    4898     .04       0    4944    .018       0    4956     .04       0
    5122    .018       0    5134     .04       0 5224.35      .1       0
#XS Ineff= 2 , 0
       0  4862.1   40.74               0
Permanent Ineff=
       T       F
Bank Sta=4862.1,5224.35
XS Rating Curve= 0 ,0
Exp/Cntr=0.5,0.3

Type RM Length L Ch R = 1 ,23454.82,303.78,221.19,216.14
XS GIS Cut Line= 4
  3177963.46019813874219.9111787 3177584.983592913874151.1235866
 3177192.9830645 13874340.022487 3177161.913244813874352.6769893
#Sta/Elev= 30
 4506.74   42.02 4536.33   41.25 4580.72   41.07 4610.31   39.63  4625.1   41.41
  4639.9   42.33 4654.69   41.38 4684.28   41.89 4713.87    40.4 4743.46   40.14
 4787.85   40.62 4886.17   40.47 4892.35   39.59    4922   33.66    5004   32.84
    5010   32.34    5016   32.84    5122   32.69    5128   32.19    5134   32.69
    5180   33.15    5239   39.34 5242.21   39.65 5268.54   42.69 5283.04   45.45
 5297.55   49.82 5312.05   55.01 5326.56   57.64 5348.92   57.91 5360.11   57.36
#Mann= 9 ,-1 , 0
 4506.74      .1       0 4886.17      .1       0 4892.35    .035       0
    4922     .04       0    5004    .018       0    5016     .04       0
    5122    .018       0    5134     .04       0    5239      .1       0
#XS Ineff= 2 , 0
       0 4876.62   40.55               0
Permanent Ineff=
       T       F
Bank Sta=4886.17,5242.21
XS Rating Curve= 0 ,0
Exp/Cntr=0.5,0.3

Type RM Length L Ch R = 1 ,23233.63,76.72,100.33,123.73
BEGIN DESCRIPTION:
U/S of Culvert at BW8 Access Rd
END DESCRIPTION:
XS GIS Cut Line= 6
  3177383.30190913873881.2681552 3177295.166259113874046.1218281
 3177157.353542613874156.9710159 3177101.434691213874306.5235383
 3177066.8648785  13874424.66405 3177010.765909313874823.6707979
#Sta/Elev= 30
    4813   42.69 4827.04   42.53 4841.09   41.56 4855.13   39.52 4869.17   39.18
  4911.3   41.41 4925.34   41.37  4934.6    41.24960.875   38.94  4990.1  33.095
  5039.6    32.6  5045.6    32.1  5051.6    32.6  5101.1  33.0955150.075   42.89
5170.075   42.49 5191.56   41.37 5220.59   41.44  5235.1   40.95 5350.38   41.25
 5377.74   41.67 5405.09   41.12 5432.45   41.37  5459.8   40.28 5489.65   41.11
 5564.26   41.02 5728.42   43.16 5803.04   42.97 5832.89    42.3 5862.73   42.55
#Mann= 7 ,-1 , 0
    4813     .14       0  4911.3      .1       0 4925.34    .035       0
  4990.1     .04       0  5039.6    .018       0  5051.6     .04       0
5150.075      .1       0
#XS Ineff= 2 , 0
       0    5020   42.89    5072       0   42.89
Permanent Ineff=
       T       T
Bank Sta=4934.6,5150.075
XS Rating Curve= 0 ,0
Exp/Cntr=0.5,0.3

Type RM Length L Ch R = 2 ,23183.42,,,
BEGIN DESCRIPTION:
BELTWAY 8 ACCESS RAMP
END DESCRIPTION:
Bridge Culvert--1,0,-1,-1, 0
Deck Dist Width WeirC Skew NumUp NumDn MinLoCord MaxHiCord MaxSubmerge Is_Ogee
23.5,62,3,0, 36, 60, , , 0.95, 0, 2,2,,
    4813  4831.7  4845.1  4852.5  4869.1  4881.7  4925.5  4933.6  4934.4  4944.9
  4964.6  4966.3  4995.9  5017.4  5017.9    5028  5031.8  5032.7  5038.8  5039.7
  5061.5  5062.6  5063.9  5074.1  5081.3  5095.5  5098.4  5103.1  5158.4  5191.8
    5192  5242.7  5268.5  5272.1  5281.8  5297.7
    43.5   43.44   43.24   43.13   42.88    42.7   42.04   41.92   41.91   41.88
   41.82   41.81   41.89   41.95   41.95   41.98   41.99   41.99   42.01   42.01
   42.07   42.07   42.07    42.1   42.12   42.16   42.17   42.18   42.33   42.42
   42.42   42.11   41.38   41.19   41.15   41.08
                                                                                
                                                                                
                                                                                
                                                
  4785.7  4799.1  4806.5  4823.1  4835.7  4879.5  4887.6  4888.4  4898.9  4918.6
  4920.3  4949.9  4971.4  4971.9    4982  4985.8  4986.7  4992.8  4993.7  5015.5
  5016.6  5017.9  5028.1  5035.3  5049.5  5052.4  5057.1  5112.4  5145.8    5146
  5196.7  5222.5  5226.1  5235.8  5251.7  5271.5  5271.7  5286.5  5296.5  5306.5
  5325.3  5326.5  5381.5  5406.5  5436.5  5486.5  5506.5  5536.5  5546.5  5616.5
  5636.5  5666.5  5676.5  5706.5  5746.5  5796.9  5926.9  6026.9  6146.9  6156.9
   43.44   43.24   43.13   42.88    42.7   42.04   41.92   41.91   41.88   41.82
   41.81   41.89   41.95   41.95   41.98   41.99   41.99   42.01   42.01   42.07
   42.07   42.07    42.1   42.12   42.16   42.17   42.18   42.33   42.42   42.42
   42.11   41.38   41.19   41.15   41.08   41.54   41.54   44.32   44.85   44.58
   42.15   41.99   40.15   39.32   39.79    39.7   39.08   39.27   39.66   38.97
   39.33   39.38   39.75   38.92   39.56    39.3   39.34   39.58   40.69   41.27
                                                                                
                                                                                
                                                                                
                                                                                
                                                                                
                                                                                
BR Coef=-1 , 0 , 0 ,, 0 ,,,0.8,-1,,0,
WSPro=,,,, 1 ,,,, 0 ,,,, 0 ,,,,-1 ,-1 ,-1 , 0 , 0 , 0 , 0 , 0
Multiple Barrel Culv=2,6,9,97,0.015,0.4,1,9,2,32.01,31.95, 3,Culvert #1  , 0 ,1
    5035    4989    5046    5000    5057    5011
Culvert Bottom n=0.015
BC Design=,, 0 ,, 0 ,,,,,,
BC HTab HWMax=42.89
BC Use User HTab Curves=0
BC User HTab FreeFlow(D)= 0

Type RM Length L Ch R = 1 ,23133.3 ,376.2,376.2,376.2
BEGIN DESCRIPTION:
D/S of Culvert at BW8 Access Rd
END DESCRIPTION:
XS GIS Cut Line= 6
   3177345.9568413873862.7245571 3177278.702381313873956.4294222
 3177146.838471813874036.2419266 3177058.657217713874226.8268473
 3176637.663965213874397.5000623 3176296.317863113874420.2562504
#Sta/Elev= 30
  4785.7   43.43  4799.1   42.48  4823.1   37.42  4835.7   39.52  4879.5   37.32
  4887.6   37.88  4898.9   41.53  4949.9   41.32  4971.4   40.24  4985.8   32.19
  4992.8   32.04  5016.6      33  5028.1   39.96  5035.3   39.55  5112.4    42.2
    5146   41.88  5235.8   38.59  5271.7   41.53  5286.5   44.31  5296.5   44.84
  5306.5   44.57  5325.3   42.14  5381.5   40.14  5406.5   39.31  5546.5   39.65
  5616.5   38.96  5676.5   39.74  5706.5   38.91  6026.9   39.57  6156.9   41.26
#Mann= 6 ,-1 , 0
  4785.7      .2       0  4835.7      .1       0  4971.4    .055       0
  5028.1      .1       0  5325.3     .14       0  5381.5     .99       0
#XS Ineff= 2 , 0
       0    4971    40.8  5028.2       0      41
Permanent Ineff=
       F       F
Bank Sta=4971.4,5028.1
XS Rating Curve= 0 ,0
Exp/Cntr=0.5,0.3

Type RM Length L Ch R = 1 ,22757.1 ,375.5,571.8,724
BEGIN DESCRIPTION:
Cross Section 22757.1-Interpolated
END DESCRIPTION:
XS GIS Cut Line= 5
      3176977.61     13873684.61      3176930.22     13873757.09
       3176930.2      13873757.1      3176889.42     13873819.49
      3176256.54     13874070.79
#Sta/Elev= 30
  4913.4    41.8  4928.4   39.78  4938.4   38.28  4948.4   38.56  4959.1   38.18
    4975   37.38    4985   36.23  4991.6   35.78  4996.7   31.78  5002.1   31.69
  5003.2   32.04  5011.2   37.59    5035   39.13    5095   40.44    5115   40.03
  5118.4   39.77  5125.5   39.23  5145.5   38.72  5175.5    39.1  5225.5    37.6
  5285.5   38.16  5445.5   38.55  5465.5   38.39  5475.5   38.77  5515.5   38.25
  5535.5   38.78  5615.5   39.26  5645.5    40.2  5695.5   40.05  5755.5    41.8
#Mann= 6 , 1 , 0
  4913.4      .2       0  4928.4      .1       0  4959.1     .14       0
  4991.6    .055       0  5011.2     .14       0  5118.4     .99       0
#XS Ineff= 2 , 0
       0                    5094       0   40.45
Permanent Ineff=
       F       F
Bank Sta=4991.6,5011.2
XS Rating Curve= 0 ,0
Exp/Cntr=0.5,0.3

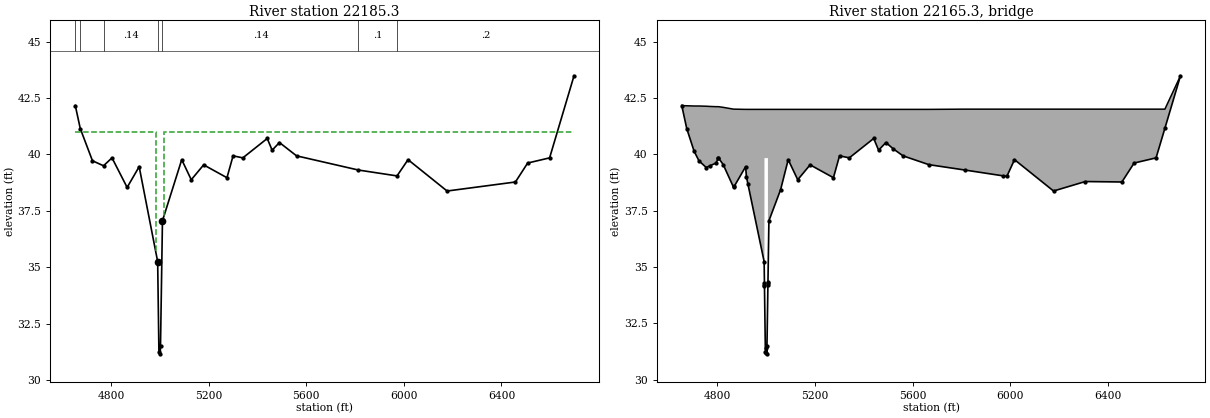
Type RM Length L Ch R = 1 ,22185.3 ,40,40,40
BEGIN DESCRIPTION:
Upstream Section of Bridge/Culvert/Weir
END DESCRIPTION:
XS GIS Cut Line= 3
      3176816.09     13873612.65      3176506.16     13873445.25
      3175016.48     13872645.14
#Sta/Elev= 30
  4654.1   42.17  4674.5   41.15  4724.5   39.72  4769.8    39.5  4804.5   39.85
  4866.5   38.54  4915.8   39.46  4991.6   35.25  4996.7   31.25  5002.1   31.16
  5003.2   31.51  5011.2   37.06  5090.2   39.77  5129.2   38.88    5180   39.54
  5275.5   38.97  5300.5   39.94  5340.5   39.85  5440.5   40.71  5460.5   40.19
  5490.5   40.53  5560.5   39.94  5814.2   39.31  5972.2   39.05  6017.3   39.77
  6177.3   38.38  6457.3   38.78  6507.3   39.62  6597.3   39.85  6697.3   43.49
#Mann= 7 , 1 , 0
  4654.1      .2       0  4674.5      .1       0  4769.8     .14       0
  4991.6    .035       0  5011.2     .14       0  5814.2      .1       0
  5972.2      .2       0
#XS Ineff= 2 , 0
       0  4982.8      41    5017       0      41
Permanent Ineff=
       F       F
Bank Sta=4991.6,5011.2
XS Rating Curve= 0 ,0
Exp/Cntr=0.5,0.3

Type RM Length L Ch R = 3 ,22165.3 ,,,
BEGIN DESCRIPTION:
SOUTHERN PACIFIC RAILROAD
Structure ID: P07-13
END DESCRIPTION:
Bridge Culvert--1,0,-1,-1, 0
Deck Dist Width WeirC Skew NumUp NumDn MinLoCord MaxHiCord MaxSubmerge Is_Ogee
10,20,2.6,0, 52, 52, , , 0.95, 0, 1,1,,
  4654.1  4674.5  4704.5  4724.5  4754.5  4769.8  4794.5  4804.1  4804.5  4823.9
  4866.5  4869.3  4915.8  4918.9  4924.8  4991.6 4992.81  4992.9    4993  4996.7
  4998.5  5000.6  5002.1  5003.2  5007.1 5007.19  5007.3  5011.2  5059.1  5090.2
  5129.2    5180  5275.5  5300.5  5340.5  5440.5  5460.5  5490.5  5520.5  5560.5
    5666  5814.2  5972.2    5986  6017.3  6177.3  6307.3  6457.3  6507.3  6597.3
  6633.4  6697.3
   42.16   42.15   42.14   42.14   42.13   42.12   42.11   42.11   42.11   42.08
      42      42   41.99   41.99   41.99   41.99   41.99   41.99   41.99   41.99
   41.99   41.99   41.99   41.99   41.99   41.99   41.99   41.99   41.99   41.99
   41.99   41.99   41.99   41.99   41.99   41.99   41.99   41.99   41.99   41.99
   41.99      42      42      42      42      42      42      42      42      42
      42   43.48
   42.16   41.14   40.14   39.71   39.41   39.49   39.61   39.83   39.84   39.54
   38.53   38.58   39.45   39.01    38.7   35.24   34.29   39.83   39.83   39.83
   39.83   39.83   39.83   39.83   39.83   39.83   34.34   37.05   38.43   39.76
   38.87   39.53   38.96   39.93   39.84    40.7   40.18   40.52   40.24   39.93
   39.54    39.3   39.04   39.02   39.76   38.37   38.79   38.77   39.61   39.84
   41.15   43.48
  4654.1  4674.5  4704.5  4724.5  4754.5  4769.8  4794.5  4804.1  4804.5  4823.9
  4866.5  4869.3  4915.8  4918.9  4924.8  4991.6 4992.81  4992.9    4993  4996.7
  4998.5  5000.6  5002.1  5003.2  5007.1 5007.19  5007.3  5011.2  5059.1  5090.2
  5129.2    5180  5275.5  5300.5  5340.5  5440.5  5460.5  5490.5  5520.5  5560.5
    5666  5814.2  5972.2    5986  6017.3  6177.3  6307.3  6457.3  6507.3  6597.3
  6633.4  6697.3
   42.16   42.15   42.14   42.14   42.13   42.12   42.11   42.11   42.11   42.08
      42      42   41.99   41.99   41.99   41.99   41.99   41.99   41.99   41.99
   41.99   41.99   41.99   41.99   41.99   41.99   41.99   41.99   41.99   41.99
   41.99   41.99   41.99   41.99   41.99   41.99   41.99   41.99   41.99   41.99
   41.99      42      42      42      42      42      42      42      42      42
      42   43.48
   41.51   40.49   39.49   39.06   38.76   38.84   38.96   39.18   39.19   38.89
   37.88   37.93    38.8   38.36   38.05   34.59   33.64   39.18   39.18   39.18
   39.18   39.18   39.18   39.18   39.18   39.18   33.69    36.4   37.78   39.11
   38.22   38.88   38.31   39.28   39.19   40.05   39.53   39.87   39.59   39.28
   38.89   38.65   38.39   38.37   39.11   37.72   38.14   38.12   38.96   39.19
    40.5   42.83
BR Coef= 1 , 1 , 0 ,1.25, 0 ,,,0.8,0,2,0,
WSPro=,,,, 1 ,,,, 0 ,,,, 0 ,,,,-1 ,-1 ,-1 , 0 , 0 , 0 , 0 , 0
BR U #Sta/Elev= 52
  4654.1   42.16  4674.5   41.14  4704.5   40.14  4724.5   39.71  4754.5   39.41
  4769.8   39.49  4794.5   39.61  4804.1   39.83  4804.5   39.84  4823.9   39.54
  4866.5   38.53  4869.3   38.58  4915.8   39.45  4918.9   39.01  4924.8    38.7
  4991.6   35.24 4992.81   34.29  4992.9   34.22    4993   34.14  4996.7   31.24
  4998.5   31.17  5000.6   31.42  5002.1   31.15  5003.2    31.5  5007.1   34.21
 5007.19   34.27  5007.3   34.34  5011.2   37.05  5059.1   38.43  5090.2   39.76
  5129.2   38.87    5180   39.53  5275.5   38.96  5300.5   39.93  5340.5   39.84
  5440.5    40.7  5460.5   40.18  5490.5   40.52  5520.5   40.24  5560.5   39.93
    5666   39.54  5814.2    39.3  5972.2   39.04    5986   39.02  6017.3   39.76
  6177.3   38.37  6307.3   38.79  6457.3   38.77  6507.3   39.61  6597.3   39.84
  6633.4   41.15  6697.3   43.48
BR U #Mann= 7
  4654.1      .2  4674.5      .1  4769.8     .14  4991.6    .035  5011.2     .14
  5814.2      .1  5972.2      .2
BR U Banks=4991.6,5011.2
BR D #Sta/Elev= 52
  4654.1   41.51  4674.5   40.49  4704.5   39.49  4724.5   39.06  4754.5   38.76
  4769.8   38.84  4794.5   38.96  4804.1   39.18  4804.5   39.19  4823.9   38.89
  4866.5   37.88  4869.3   37.93  4915.8    38.8  4918.9   38.36  4924.8   38.05
  4991.6   34.59 4992.81   33.64  4992.9   33.57    4993   33.49  4996.7   30.59
  4998.5   30.52  5000.6   30.77  5002.1    30.5  5003.2   30.85  5007.1   33.56
 5007.19   33.62  5007.3   33.69  5011.2    36.4  5059.1   37.78  5090.2   39.11
  5129.2   38.22    5180   38.88  5275.5   38.31  5300.5   39.28  5340.5   39.19
  5440.5   40.05  5460.5   39.53  5490.5   39.87  5520.5   39.59  5560.5   39.28
    5666   38.89  5814.2   38.65  5972.2   38.39    5986   38.37  6017.3   39.11
  6177.3   37.72  6307.3   38.14  6457.3   38.12  6507.3   38.96  6597.3   39.19
  6633.4    40.5  6697.3   42.83
BR D #Mann= 7
  4654.1      .2  4674.5      .1  4769.8     .14  4991.6    .035  5011.2     .14
  5814.2      .1  5972.2      .2
BR D Banks=4991.6,5011.2
BC Design=,, 0 ,, 0 ,,,,,,
BC HTab HWMax=43.49
BC Use User HTab Curves=0
BC User HTab FreeFlow(D)= 0