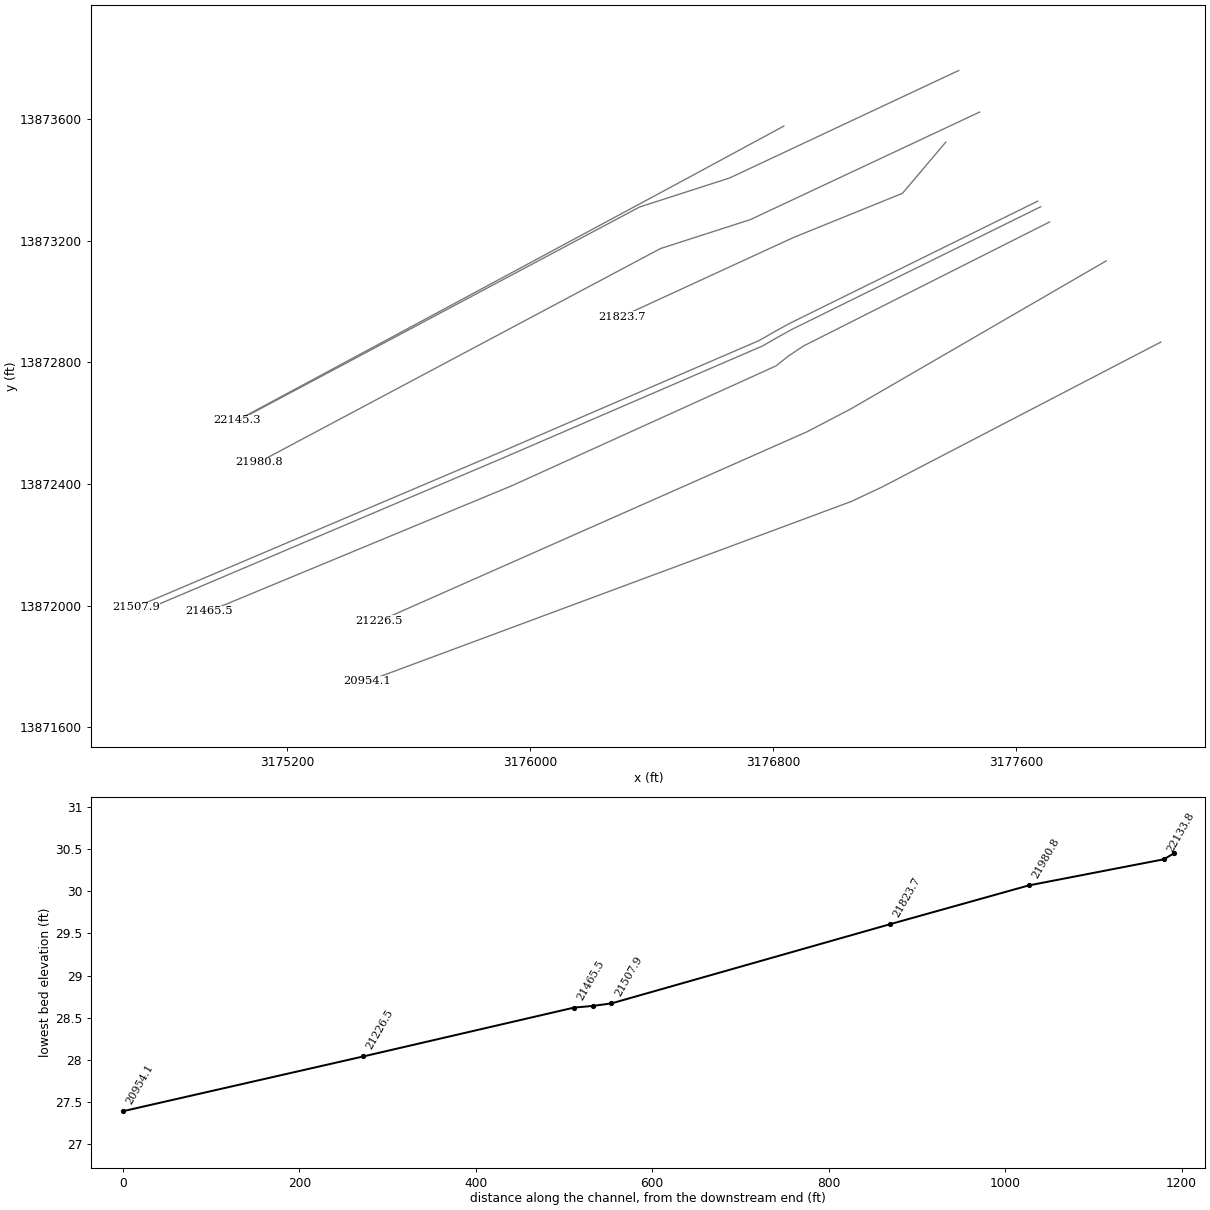
HEC-RAS study P107-00-00.prj: P107-00-00

--- P107-00-00.g01 (geometry) --- (continued)

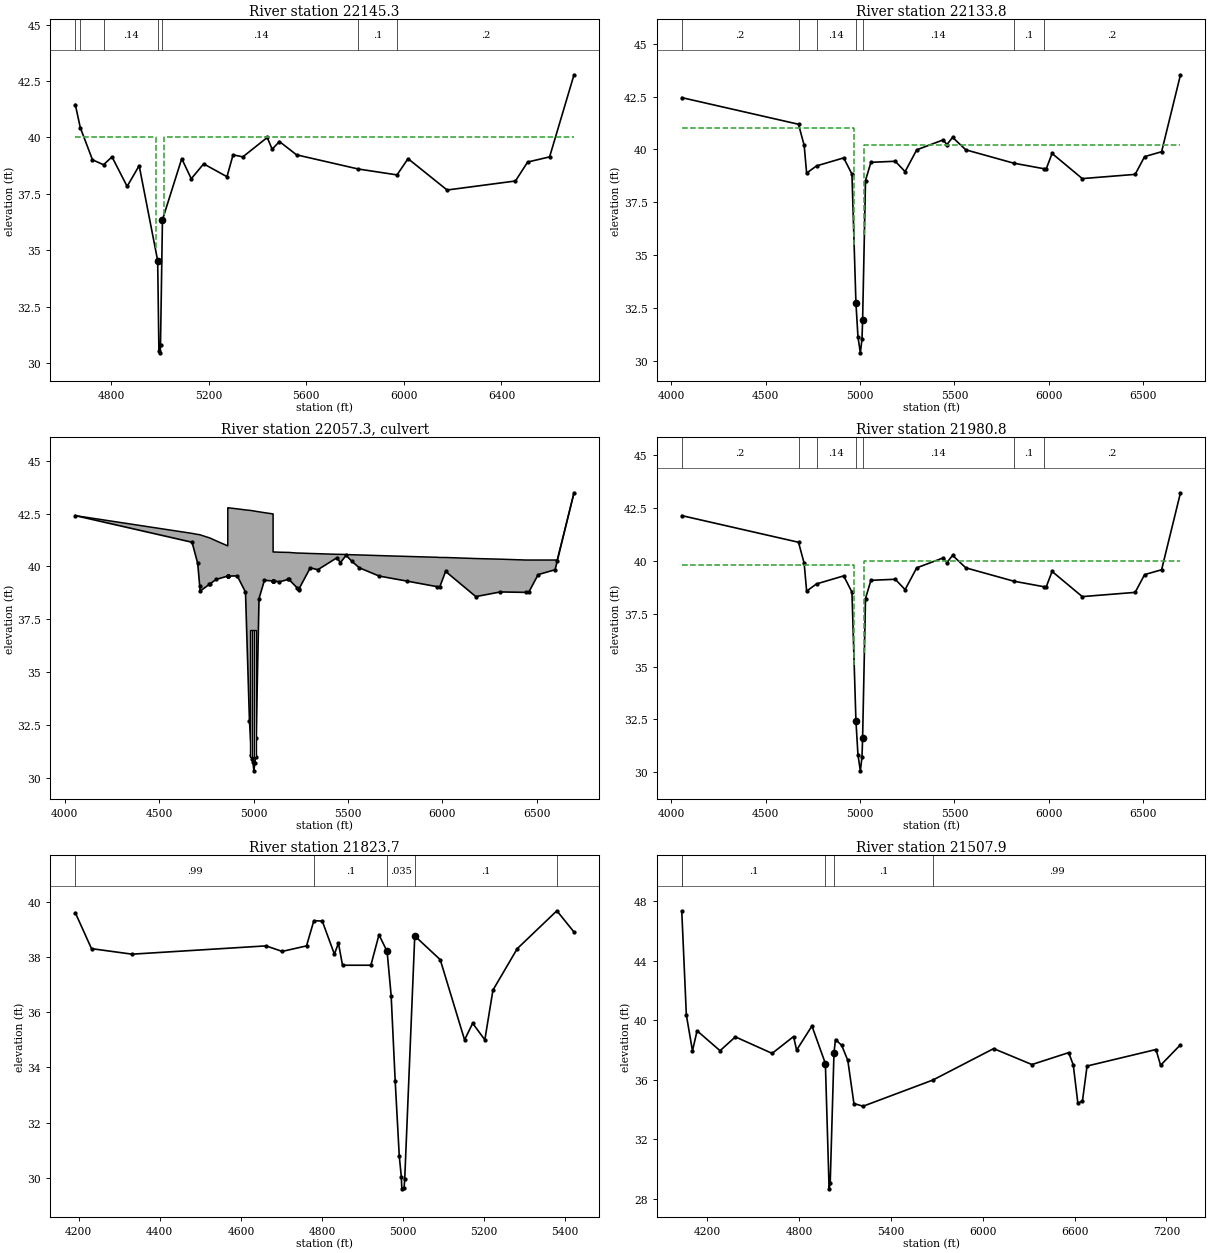
Type RM Length L Ch R = 1 ,22145.3 ,11.5,11.5,11.5
BEGIN DESCRIPTION:
Downstream Section of Bridge/Culvert/Weir
END DESCRIPTION:
XS GIS Cut Line= 3
       3176834.1     13873576.94      3176524.18     13873409.53
      3175034.49     13872609.42
#Sta/Elev= 30
  4654.1   41.46  4674.5   40.44  4724.5   39.01  4769.8   38.79  4804.5   39.14
  4866.5   37.83  4915.8   38.75  4991.6   34.54  4996.7   30.54  5002.1   30.45
  5003.2    30.8  5011.2   36.35  5090.2   39.06  5129.2   38.17    5180   38.83
  5275.5   38.26  5300.5   39.23  5340.5   39.14  5440.5      40  5460.5   39.48
  5490.5   39.82  5560.5   39.23  5814.2    38.6  5972.2   38.34  6017.3   39.06
  6177.3   37.67  6457.3   38.07  6507.3   38.91  6597.3   39.14  6697.3   42.78
#Mann= 7 , 1 , 0
  4654.1      .2       0  4674.5      .1       0  4769.8     .14       0
  4991.6    .035       0  5011.2     .14       0  5814.2      .1       0
  5972.2      .2       0
#XS Ineff= 2 , 0
       0  4982.8      40    5017       0      40
Permanent Ineff=
       F       F
Bank Sta=4991.6,5011.2
XS Rating Curve= 0 ,0
Exp/Cntr=0.5,0.3

Type RM Length L Ch R = 1 ,22133.8 ,153,153,153
BEGIN DESCRIPTION:
Upstream Section of Bridge/Culvert/Weir
END DESCRIPTION:
XS GIS Cut Line= 4
      3177409.83     13873759.65      3176654.93     13873405.96
       3176359.3     13873310.93       3175037.4     13872608.56
#Sta/Elev= 30
  4056.2   42.45  4674.5   41.19  4704.5   40.19  4717.5   38.88  4769.8   39.22
  4913.9    39.6  4957.5   38.83  4978.6   32.74  4989.3   31.14    5002   30.38
  5010.7   31.03  5013.9   31.92  5029.3   38.53  5057.9   39.39  5186.8   39.44
  5238.9   38.95  5300.5   39.98  5440.5   40.45  5460.5   40.23  5490.5   40.57
  5560.5   39.98  5814.2   39.35  5972.2   39.09    5986   39.07  6017.3   39.81
  6177.3   38.62  6457.3   38.82  6507.3   39.66  6597.3   39.89  6697.3   43.53
#Mann= 7 , 1 , 0
  4056.2      .2       0  4674.5      .1       0  4769.8     .14       0
  4978.6     .04       0  5013.9     .14       0  5814.2      .1       0
  5972.2      .2       0
#XS Ineff= 2 , 0
       0  4969.5      41  5023.3       0    40.2
Permanent Ineff=
       F       F
Bank Sta=4978.6,5013.9
XS Rating Curve= 0 ,0
Exp/Cntr=0.5,0.3

Type RM Length L Ch R = 2 ,22057.3 ,,,
BEGIN DESCRIPTION:
BEAUMONT HWY
Structure ID: P07-12,,,,
END DESCRIPTION:
Bridge Culvert--1,0,-1,-1, 0
Deck Dist Width WeirC Skew NumUp NumDn MinLoCord MaxHiCord MaxSubmerge Is_Ogee
10,133,3,0, 56, 56, , , 0.95, 0, 1,1,,
  4056.2  4674.5  4704.5    4715  4717.5  4766.2  4769.8  4801.5  4863.3 4863.69
  4863.8 4863.91  4864.9  4913.9  4957.5  4978.6  4989.3  4994.3  4996.7    5002
  5006.7  5010.7  5013.9  5029.3  5057.9 5103.59  5103.7 5103.81  5104.2    5106
  5137.2  5183.2  5186.8  5230.2  5238.8  5238.9  5300.5  5340.5  5440.5  5460.5
  5490.5  5520.5  5560.5    5666  5814.2  5972.2    5986  6017.3  6177.3  6307.3
  6442.9  6457.3  6507.3  6597.3  6608.2  6697.3
    42.4   41.56   41.51    41.5   41.49   41.35   41.34   41.21   40.97   40.97
   42.77   42.77   42.77   42.72   42.67   42.65   42.64   42.63   42.63   42.62
   42.61   42.61    42.6   42.58   42.54   42.48   42.48   40.68   40.68   40.68
   40.67   40.66   40.66   40.63   40.63   40.63   40.61    40.6   40.57   40.57
   40.56   40.55   40.54   40.51   40.47   40.43   40.42   40.42   40.37   40.34
    40.3    40.3    40.3    40.3    40.3   43.48
    42.4   41.14   40.14   39.08   38.83   39.15   39.17   39.38   39.54   39.54
   39.54   39.54   39.54   39.55   38.78   32.69   31.09   30.87   30.76   30.33
   30.68   30.98   31.87   38.48   39.34   39.31   39.31   39.31   39.31   39.31
   39.27   39.38   39.39   38.99   38.91    38.9   39.93   39.84    40.4   40.18
   40.52   40.24   39.93   39.54    39.3   39.04   39.02   39.76   38.57   38.79
   38.77   38.77   39.61   39.84   40.24   43.48
  4056.2  4674.5  4704.5    4715  4717.5  4766.2  4769.8  4801.5  4863.3 4863.69
  4863.8 4863.91  4864.9  4913.9  4957.5  4978.6  4989.3  4994.3  4996.7    5002
  5006.7  5010.7  5013.9  5029.3  5057.9 5103.59  5103.7 5103.81  5104.2    5106
  5137.2  5183.2  5186.8  5230.2  5238.8  5238.9  5300.5  5340.5  5440.5  5460.5
  5490.5  5520.5  5560.5    5666  5814.2  5972.2    5986  6017.3  6177.3  6307.3
  6442.9  6457.3  6507.3  6597.3  6608.2  6697.3
    42.4   41.56   41.51    41.5   41.49   41.35   41.34   41.21   40.97   40.97
   42.77   42.77   42.77   42.72   42.67   42.65   42.64   42.63   42.63   42.62
   42.61   42.61    42.6   42.58   42.54   42.48   42.48   40.68   40.68   40.68
   40.67   40.66   40.66   40.63   40.63   40.63   40.61    40.6   40.57   40.57
   40.56   40.55   40.54   40.51   40.47   40.43   40.42   40.42   40.37   40.34
    40.3    40.3    40.3    40.3    40.3   43.48
   42.17   40.91   39.91   38.85    38.6   38.92   38.94   39.15   39.31   39.31
   39.31   39.31   39.31   39.32   38.55   32.46   30.86   30.64   30.53    30.1
   30.45   30.75   31.64   38.25   39.11   39.08   39.08   39.08   39.08   39.08
   39.04   39.15   39.16   38.76   38.68   38.67    39.7   39.61   40.17   39.95
   40.29   40.01    39.7   39.31   39.07   38.81   38.79   39.53   38.34   38.56
   38.54   38.54   39.38   39.61   40.01   43.25
BR Coef= 1 , 0 , 0 ,1.25, 0 ,,,0.8,-1,2,0,
WSPro=,,,, 1 ,,,, 0 ,,,, 0 ,,,,-1 ,-1 ,-1 , 0 , 0 , 0 , 0 , 0
Culvert=2,6,10,133,0.015,0.4,1,8,1,31,4984.5,30.98,4984.5,Culvert #1  , 0 ,10
Culvert Bottom n=0.015
Culvert=2,6,10,133,0.015,0.4,1,8,1,31,4996.2,30.98,4996.2,Culvert #2  , 0 ,10
Culvert Bottom n=0.015
Culvert=2,6,10,133,0.015,0.4,1,8,1,31,5008.2,30.98,5008.2,Culvert #3  , 0 ,10
Culvert Bottom n=0.015
BR U #Sta/Elev= 56
  4056.2    42.4  4674.5   41.14  4704.5   40.14    4715   39.08  4717.5   38.83
  4766.2   39.15  4769.8   39.17  4801.5   39.38  4863.3   39.54 4863.69   39.54
  4863.8   39.54 4863.91   39.54  4864.9   39.54  4913.9   39.55  4957.5   38.78
  4978.6   32.69  4989.3   31.09  4994.3   30.87  4996.7   30.76    5002   30.33
  5006.7   30.68  5010.7   30.98  5013.9   31.87  5029.3   38.48  5057.9   39.34
 5103.59   39.31  5103.7   39.31 5103.81   39.31  5104.2   39.31    5106   39.31
  5137.2   39.27  5183.2   39.38  5186.8   39.39  5230.2   38.99  5238.8   38.91
  5238.9    38.9  5300.5   39.93  5340.5   39.84  5440.5    40.4  5460.5   40.18
  5490.5   40.52  5520.5   40.24  5560.5   39.93    5666   39.54  5814.2    39.3
  5972.2   39.04    5986   39.02  6017.3   39.76  6177.3   38.57  6307.3   38.79
  6442.9   38.77  6457.3   38.77  6507.3   39.61  6597.3   39.84  6608.2   40.24
  6697.3   43.48
BR U #Mann= 7
  4056.2      .2  4674.5      .1  4769.8     .14  4978.6     .04  5013.9     .14
  5814.2      .1  5972.2      .2
BR U Banks=4978.6,5013.9
BR D #Sta/Elev= 56
  4056.2   42.17  4674.5   40.91  4704.5   39.91    4715   38.85  4717.5    38.6
  4766.2   38.92  4769.8   38.94  4801.5   39.15  4863.3   39.31 4863.69   39.31
  4863.8   39.31 4863.91   39.31  4864.9   39.31  4913.9   39.32  4957.5   38.55
  4978.6   32.46  4989.3   30.86  4994.3   30.64  4996.7   30.53    5002    30.1
  5006.7   30.45  5010.7   30.75  5013.9   31.64  5029.3   38.25  5057.9   39.11
 5103.59   39.08  5103.7   39.08 5103.81   39.08  5104.2   39.08    5106   39.08
  5137.2   39.04  5183.2   39.15  5186.8   39.16  5230.2   38.76  5238.8   38.68
  5238.9   38.67  5300.5    39.7  5340.5   39.61  5440.5   40.17  5460.5   39.95
  5490.5   40.29  5520.5   40.01  5560.5    39.7    5666   39.31  5814.2   39.07
  5972.2   38.81    5986   38.79  6017.3   39.53  6177.3   38.34  6307.3   38.56
  6442.9   38.54  6457.3   38.54  6507.3   39.38  6597.3   39.61  6608.2   40.01
  6697.3   43.25
BR D #Mann= 7
  4056.2      .2  4674.5      .1  4769.8     .14  4978.6     .04  5013.9     .14
  5814.2      .1  5972.2      .2
BR D Banks=4978.6,5013.9
BC Design=,, 0 ,, 0 ,,,,,,
BC HTab HWMax=43.53
BC Use User HTab Curves=0
BC User HTab FreeFlow(D)= 0

Type RM Length L Ch R = 1 ,21980.8 ,157.1,157.1,157.1
BEGIN DESCRIPTION:
Downstream Section of Bridge/Culvert/Weir
END DESCRIPTION:
XS GIS Cut Line= 4
      3177478.73     13873623.03      3176723.83     13873269.34
       3176428.2     13873174.31       3175106.3     13872471.95
#Sta/Elev= 30
  4056.2   42.14  4674.5   40.88  4704.5   39.88  4717.5   38.57  4769.8   38.91
  4913.9   39.29  4957.5   38.52  4978.6   32.43  4989.3   30.83    5002   30.07
  5010.7   30.72  5013.9   31.61  5029.3   38.22  5057.9   39.08  5186.8   39.13
  5238.9   38.64  5300.5   39.67  5440.5   40.14  5460.5   39.92  5490.5   40.26
  5560.5   39.67  5814.2   39.04  5972.2   38.78    5986   38.76  6017.3    39.5
  6177.3   38.31  6457.3   38.51  6507.3   39.35  6597.3   39.58  6697.3   43.22
#Mann= 7 , 1 , 0
  4056.2      .2       0  4674.5      .1       0  4769.8     .14       0
  4978.6     .04       0  5013.9     .14       0  5814.2      .1       0
  5972.2      .2       0
#XS Ineff= 2 , 0
       0  4969.5    39.8  5023.3       0      40
Permanent Ineff=
       F       F
Bank Sta=4978.6,5013.9
XS Rating Curve= 0 ,0
Exp/Cntr=0.5,0.3

Type RM Length L Ch R = 1 ,21823.7 ,211.8,315.8,341.7
BEGIN DESCRIPTION:
Cross Section 21823.7-Interpolated
END DESCRIPTION:
XS GIS Cut Line= 5
      3177367.41     13873524.18      3177224.89     13873355.96
      3176864.55     13873209.99      3176636.48     13873105.08
      3176300.29     13872950.57
#Sta/Elev= 30
  4191.5    39.6  4231.5    38.3  4331.5    38.1  4661.9    38.4  4701.9    38.2
  4761.9    38.4    4780   39.31  4800.7    39.3  4830.7    38.1  4840.7    38.5
  4850.7    37.7  4920.7    37.7  4940.7    38.8  4960.7    38.2  4970.7    36.6
  4980.7    33.5  4990.7    30.8 4995.83   30.04 4997.03   29.61 5002.63   29.65
 5004.23   29.98 5028.93   38.76  5091.8    37.9  5151.8      35  5171.8    35.6
  5201.8      35  5221.8    36.8  5281.8    38.3  5379.5   39.67  5421.8    38.9
#Mann= 5 , 1 , 0
  4191.5     .99       0    4780      .1       0  4960.7    .035       0
 5028.93      .1       0  5379.5     .99       0
#XS Ineff= 2 , 0
       0  4940.7    38.8  5325.7       0    38.9
Permanent Ineff=
       F       F
Bank Sta=4960.7,5028.93
XS Rating Curve= 0 ,0
Exp/Cntr=0.5,0.3

Type RM Length L Ch R = 1 ,21507.9 ,21,21,21
BEGIN DESCRIPTION:
Upstream Section of Bridge/Culvert/Weir
END DESCRIPTION:
XS GIS Cut Line= 6
      3177669.74     13873330.08      3176852.04     13872927.56
       3176804.9     13872901.59      3176753.61     13872872.21
      3175899.34     13872504.03      3174700.84     13871995.47
#Sta/Elev= 30
  4034.9   47.35  4064.9   40.35  4104.9   37.94  4134.9   39.29  4284.9   37.95
  4384.9   38.88  4624.9   37.77  4764.9    38.9  4784.9   37.99  4884.9   39.61
 4972.73   37.09 4997.03   28.67 5004.23   29.04 5028.93   37.82  5038.8    38.7
  5079.1   38.31  5119.1    37.3  5159.1    34.4  5219.1   34.22  5674.9   35.98
  6071.4   38.09  6321.4   37.02  6561.4   37.82  6591.4   36.99  6621.4   34.42
  6651.4   34.58  6681.4   36.92  7131.4   38.03  7161.4   36.97  7291.4   38.35
#Mann= 5 , 1 , 0
  4034.9      .2       0  4034.9      .1       0 4972.73    .035       0
 5028.93      .1       0  5674.9     .99       0
#XS Ineff= 2 , 0
       0  4884.9   39.58  5038.8       0   33.57
Permanent Ineff=
       F       F
Bank Sta=4972.73,5028.93
XS Rating Curve= 0 ,0
Exp/Cntr=0.5,0.3

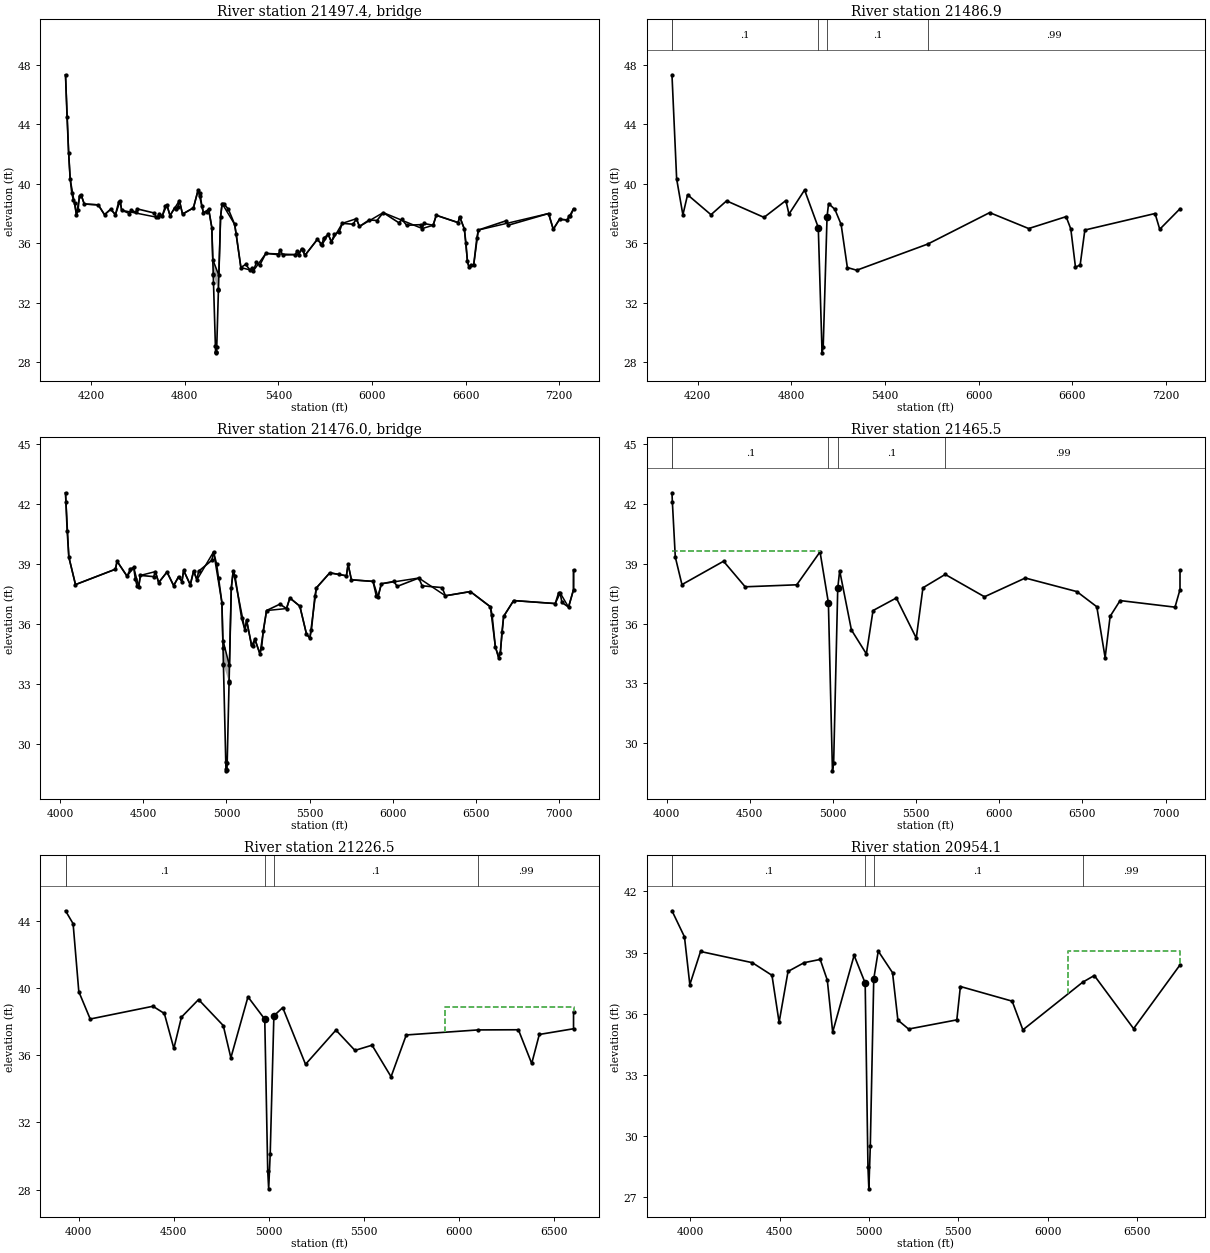
Type RM Length L Ch R = 3 ,21497.4 ,,,
BEGIN DESCRIPTION:
12" PIPELINE
END DESCRIPTION:
Bridge Culvert--1,0,-1,-1, 0
Deck Dist Width WeirC Skew NumUp NumDn MinLoCord MaxHiCord MaxSubmerge Is_Ogee
10,1,2.6,0, 60, 60, , , 0.95, 0, 1,1,,
  4034.9  4054.9  4064.9  4104.9  4124.9  4134.9  4154.9  4244.9  4284.9  4324.9
  4354.9  4384.9  4394.9  4624.9  4654.9  4684.9  4704.9  4764.9  4784.9  4854.9
  4884.9  4918.8 4952.63 4972.73 4979.13 4981.93 5015.13 5017.93 5028.93  5038.8
  5119.1  5159.1  5239.1  5319.1  5529.1  5549.1  5569.1  5649.1  5679.1  5719.1
  5739.1  5809.1  5899.1  5919.1  6071.4  6321.4  6391.4  6411.4  6551.4  6561.4
  6591.4  6611.4  6621.4  6651.4  6681.4  7131.4  7161.4  7201.4  7251.4  7291.4
   47.32   42.08   40.32   37.91   39.18   39.26   38.64   38.58   37.92   38.29
   37.92   38.85   38.22   37.74   37.83   38.57   37.86   38.87   37.96   38.38
   39.58   38.06   38.28   37.06   34.86   34.82   33.92   33.91   37.79   38.67
   37.27   34.37   34.15   35.32   35.23   35.64   35.18   36.26    35.9    36.6
   36.09   37.34   37.65   37.13   38.06   36.99   37.21   37.88   37.39   37.79
   36.96   34.78   34.39   34.55   36.89      38   36.94   37.61   37.57   38.32
   47.32   42.08   40.32   37.91   39.18   39.26   38.64   38.58   37.92   38.29
   37.92   38.85   38.22   37.74   37.83   38.57   37.86   38.87   37.96   38.38
   39.58   38.06   38.28   37.06   34.85   33.88   32.88   33.88   37.79   38.67
   37.27   34.37   34.15   35.32   35.23   35.64   35.18   36.26    35.9    36.6
   36.09   37.34   37.65   37.13   38.06   36.99   37.21   37.88   37.39   37.79
   36.96   34.78   34.39   34.55   36.89      38   36.94   37.61   37.57   38.32
  4034.9  4054.9  4064.9  4104.9  4124.9  4134.9  4154.9  4244.9  4284.9  4324.9
  4354.9  4384.9  4394.9  4624.9  4654.9  4684.9  4704.9  4764.9  4784.9  4854.9
  4884.9  4918.8 4952.63 4972.73 4979.13 4981.93 5015.13 5017.93 5028.93  5038.8
  5119.1  5159.1  5239.1  5319.1  5529.1  5549.1  5569.1  5649.1  5679.1  5719.1
  5739.1  5809.1  5899.1  5919.1  6071.4  6321.4  6391.4  6411.4  6551.4  6561.4
  6591.4  6611.4  6621.4  6651.4  6681.4  7131.4  7161.4  7201.4  7251.4  7291.4
   47.32   42.08   40.32   37.91   39.18   39.26   38.64   38.58   37.92   38.29
   37.92   38.85   38.22   37.74   37.83   38.57   37.86   38.87   37.96   38.38
   39.58   38.06   38.28   37.06   34.86   34.82   33.92   33.91   37.79   38.67
   37.27   34.37   34.15   35.32   35.23   35.64   35.18   36.26    35.9    36.6
   36.09   37.34   37.65   37.13   38.06   36.99   37.21   37.88   37.39   37.79
   36.96   34.78   34.39   34.55   36.89      38   36.94   37.61   37.57   38.32
   47.32   42.08   40.32   37.91   39.18   39.26   38.64   38.58   37.92   38.29
   37.92   38.85   38.22   37.74   37.83   38.57   37.86   38.87   37.96   38.38
   39.58   38.06   38.28   37.06   34.85   33.88   32.88   33.88   37.79   38.67
   37.27   34.37   34.15   35.32   35.23   35.64   35.18   36.26    35.9    36.6
   36.09   37.34   37.65   37.13   38.06   36.99   37.21   37.88   37.39   37.79
   36.96   34.78   34.39   34.55   36.89      38   36.94   37.61   37.57   38.32
BR Coef= 1 , 1 , 0 ,1.25, 0 ,,,0.8,0,2,0,
WSPro=,,,, 1 ,,,, 0 ,,,, 0 ,,,,-1 ,-1 ,-1 , 0 , 0 , 0 , 0 , 0
BR U #Sta/Elev= 123
  4034.9   47.32  4044.9    44.5  4054.9   42.08  4064.9   40.32  4074.9   39.41
  4084.9   38.92  4094.9    38.7  4104.9   37.91  4114.9   38.23  4124.9   39.18
  4134.9   39.26  4154.9   38.64  4244.9   38.58  4284.9   37.92  4324.9   38.29
  4354.9   37.92  4374.9   38.74  4384.9   38.85  4394.9   38.22  4444.9      38
  4454.9   38.23  4484.9   38.09  4494.9   38.31  4604.9   38.03  4614.9   37.76
  4624.9   37.74  4634.9   37.99  4654.9   37.83  4674.9   38.51  4684.9   38.57
  4704.9   37.86  4734.9   38.39  4744.9   38.31  4754.9   38.47  4764.9   38.87
  4784.9   37.96  4854.9   38.38  4884.9   39.58  4894.9   39.39  4898.8    39.2
  4908.8   38.51  4918.8   38.06  4938.8   38.09 4952.63   38.28 4972.73   37.06
 4979.13   34.85 4981.84   33.91 4981.93   33.88 4983.43   33.36 4995.83   29.07
 4997.03   28.64 4999.43   28.71 5002.63   28.68 5004.23   29.01 5015.02   32.85
 5015.13   32.88 5015.23   32.92 5017.93   33.88 5028.93   37.79  5038.8   38.67
  5048.8   38.67  5079.1   38.28  5119.1   37.27  5129.1   36.62  5159.1   34.37
  5189.1   34.58  5219.1   34.19  5229.1   34.31  5239.1   34.15  5259.1   34.72
  5279.1   34.52  5319.1   35.32  5399.1   35.24  5409.1   35.54  5429.1   35.21
  5509.1   35.24  5519.1   35.49  5529.1   35.23  5549.1   35.64  5559.1   35.53
  5569.1   35.18  5649.1   36.26  5674.9   35.95  5679.1    35.9  5689.1   36.34
  5719.1    36.6  5739.1   36.09  5759.1   36.61  5789.1   36.75  5809.1   37.34
  5879.1   37.28  5899.1   37.65  5919.1   37.13  5981.4   37.57  6031.4   37.53
  6071.4   38.06  6171.4   37.38  6191.4    37.6  6221.4   37.21  6311.4   37.25
  6321.4   36.99  6331.4   37.33  6391.4   37.21  6411.4   37.88  6551.4   37.39
  6561.4   37.79  6591.4   36.96  6601.4   36.04  6611.4   34.78  6621.4   34.39
  6631.4   34.54  6651.4   34.55  6671.4   36.35  6681.4   36.89  6861.4   37.52
  6871.4   37.21  7131.4      38  7161.4   36.94  7201.4   37.61  7251.4   37.57
  7261.4   37.81  7271.4   37.82  7291.4   38.32
BR U #Mann= 5
  4034.9      .2  4034.9      .1 4972.73    .035 5028.93      .1  5674.9     .99
BR U Banks=4972.73,5028.93
BR D #Sta/Elev= 123
  4034.9   47.32  4044.9    44.5  4054.9   42.08  4064.9   40.32  4074.9   39.41
  4084.9   38.92  4094.9    38.7  4104.9   37.91  4114.9   38.23  4124.9   39.18
  4134.9   39.26  4154.9   38.64  4244.9   38.58  4284.9   37.92  4324.9   38.29
  4354.9   37.92  4374.9   38.74  4384.9   38.85  4394.9   38.22  4444.9      38
  4454.9   38.23  4484.9   38.09  4494.9   38.31  4604.9   38.03  4614.9   37.76
  4624.9   37.74  4634.9   37.99  4654.9   37.83  4674.9   38.51  4684.9   38.57
  4704.9   37.86  4734.9   38.39  4744.9   38.31  4754.9   38.47  4764.9   38.87
  4784.9   37.96  4854.9   38.38  4884.9   39.58  4894.9   39.39  4898.8    39.2
  4908.8   38.51  4918.8   38.06  4938.8   38.09 4952.63   38.28 4972.73   37.06
 4979.13   34.85 4981.84   33.91 4981.93   33.88 4983.43   33.36 4995.83   29.07
 4997.03   28.64 4999.43   28.71 5002.63   28.68 5004.23   29.01 5015.02   32.85
 5015.13   32.88 5015.23   32.92 5017.93   33.88 5028.93   37.79  5038.8   38.67
  5048.8   38.67  5079.1   38.28  5119.1   37.27  5129.1   36.62  5159.1   34.37
  5189.1   34.58  5219.1   34.19  5229.1   34.31  5239.1   34.15  5259.1   34.72
  5279.1   34.52  5319.1   35.32  5399.1   35.24  5409.1   35.54  5429.1   35.21
  5509.1   35.24  5519.1   35.49  5529.1   35.23  5549.1   35.64  5559.1   35.53
  5569.1   35.18  5649.1   36.26  5674.9   35.95  5679.1    35.9  5689.1   36.34
  5719.1    36.6  5739.1   36.09  5759.1   36.61  5789.1   36.75  5809.1   37.34
  5879.1   37.28  5899.1   37.65  5919.1   37.13  5981.4   37.57  6031.4   37.53
  6071.4   38.06  6171.4   37.38  6191.4    37.6  6221.4   37.21  6311.4   37.25
  6321.4   36.99  6331.4   37.33  6391.4   37.21  6411.4   37.88  6551.4   37.39
  6561.4   37.79  6591.4   36.96  6601.4   36.04  6611.4   34.78  6621.4   34.39
  6631.4   34.54  6651.4   34.55  6671.4   36.35  6681.4   36.89  6861.4   37.52
  6871.4   37.21  7131.4      38  7161.4   36.94  7201.4   37.61  7251.4   37.57
  7261.4   37.81  7271.4   37.82  7291.4   38.32
BR D #Mann= 5
  4034.9      .2  4034.9      .1 4972.73    .035 5028.93      .1  5674.9     .99
BR D Banks=4972.73,5028.93
BC Design=,, 0 ,, 0 ,,,,,,
BC HTab HWMax=47.35
BC Use User HTab Curves=0
BC User HTab FreeFlow(D)= 0

Type RM Length L Ch R = 1 ,21486.9 ,21.4,21.4,21.4
BEGIN DESCRIPTION:
Downstream Section of Bridge/Culvert/Weir
END DESCRIPTION:
XS GIS Cut Line= 6
      3177679.81     13873311.66      3176862.12     13872909.14
      3176814.98     13872883.17      3176763.69     13872853.79
      3175909.42     13872485.61      3174710.92     13871977.05
#Sta/Elev= 30
  4034.9   47.32  4064.9   40.32  4104.9   37.91  4134.9   39.26  4284.9   37.92
  4384.9   38.85  4624.9   37.74  4764.9   38.87  4784.9   37.96  4884.9   39.58
 4972.73   37.06 4997.03   28.64 5004.23   29.01 5028.93   37.79  5038.8   38.67
  5079.1   38.28  5119.1   37.27  5159.1   34.37  5219.1   34.19  5674.9   35.95
  6071.4   38.06  6321.4   36.99  6561.4   37.79  6591.4   36.96  6621.4   34.39
  6651.4   34.55  6681.4   36.89  7131.4      38  7161.4   36.94  7291.4   38.32
#Mann= 5 , 1 , 0
  4034.9      .2       0  4034.9      .1       0 4972.73    .035       0
 5028.93      .1       0  5674.9     .99       0
#XS Ineff= 2 , 0
       0  4884.9   39.58  5038.8       0   33.57
Permanent Ineff=
       F       F
Bank Sta=4972.73,5028.93
XS Rating Curve= 0 ,0
Exp/Cntr=0.5,0.3

Type RM Length L Ch R = 3 ,21476.0 ,,,
BEGIN DESCRIPTION:
12" PIPELINE
END DESCRIPTION:
Bridge Culvert--1,0,-1,-1, 0
Deck Dist Width WeirC Skew NumUp NumDn MinLoCord MaxHiCord MaxSubmerge Is_Ogee
10,1,2.6,0, 60, 60, , , 0.95, 0, 1,1,,
  4032.5  4052.5  4092.5  4332.5  4342.5  4402.5  4442.5  4472.5  4482.5  4572.5
  4592.5  4642.5  4682.5  4712.5  4732.5  4742.5  4782.5  4802.5  4822.5  4922.5
 4972.73 4978.23 4981.64 5015.62 5018.03 5028.93  5040.5    5111    5121    5151
    5171    5201    5241    5361    5381    5441    5481    5501    5541    5621
    5721    5731    5751    5881    5911    5931  6156.1  6316.1  6466.1  6586.1
  6616.1  6636.1  6646.1  6666.1  6726.1  6976.1  7006.1  7056.1  7086.1  7086.2
   42.57   39.35   37.97   38.74   39.14   38.39   38.83   37.86   38.43   38.62
   38.07    38.6   37.92   38.37   38.12   38.68   37.96   38.65   38.21   39.61
   37.06   35.18    35.1   33.98      34   37.79   38.67    35.7   36.18   34.92
   35.23    34.5   36.67   36.77    37.3   36.89   35.49   35.29   37.81   38.56
   38.41   38.99   38.21   38.13   37.36   38.01    38.3   37.41   37.62   36.86
   34.86   34.31   34.55   36.38   37.17   37.02   37.55   36.84   37.72    38.7
   42.57   39.35   37.97   38.74   39.14   38.39   38.83   37.86   38.43   38.62
   38.07    38.6   37.92   38.37   38.12   38.68   37.96   38.65   38.21   39.61
   37.06   35.16   33.98   33.06   33.92   37.79   38.67    35.7   36.18   34.92
   35.23    34.5   36.67   36.77    37.3   36.89   35.49   35.29   37.81   38.56
   38.41   38.99   38.21   38.13   37.36   38.01    38.3   37.41   37.62   36.86
   34.86   34.31   34.55   36.38   37.17   37.02   37.55   36.84   37.72    38.7
  4032.5  4052.5  4092.5  4332.5  4342.5  4402.5  4442.5  4472.5  4482.5  4572.5
  4592.5  4642.5  4682.5  4712.5  4732.5  4742.5  4782.5  4802.5  4822.5  4922.5
 4972.73 4978.23 4981.64 5015.62 5018.03 5028.93  5040.5    5111    5121    5151
    5171    5201    5241    5361    5381    5441    5481    5501    5541    5621
    5721    5731    5751    5881    5911    5931  6156.1  6316.1  6466.1  6586.1
  6616.1  6636.1  6646.1  6666.1  6726.1  6976.1  7006.1  7056.1  7086.1  7086.2
   42.57   39.35   37.97   38.74   39.14   38.39   38.83   37.86   38.43   38.62
   38.07    38.6   37.92   38.37   38.12   38.68   37.96   38.65   38.21   39.61
   37.06   35.18    35.1   33.98      34   37.79   38.67    35.7   36.18   34.92
   35.23    34.5   36.67   36.77    37.3   36.89   35.49   35.29   37.81   38.56
   38.41   38.99   38.21   38.13   37.36   38.01    38.3   37.41   37.62   36.86
   34.86   34.31   34.55   36.38   37.17   37.02   37.55   36.84   37.72    38.7
   42.57   39.35   37.97   38.74   39.14   38.39   38.83   37.86   38.43   38.62
   38.07    38.6   37.92   38.37   38.12   38.68   37.96   38.65   38.21   39.61
   37.06   35.16   33.98   33.06   33.92   37.79   38.67    35.7   36.18   34.92
   35.23    34.5   36.67   36.77    37.3   36.89   35.49   35.29   37.81   38.56
   38.41   38.99   38.21   38.13   37.36   38.01    38.3   37.41   37.62   36.86
   34.86   34.31   34.55   36.38   37.17   37.02   37.55   36.84   37.72    38.7
BR Coef= 1 , 1 , 0 ,1.25, 0 ,,,0.8,0,2,0,
WSPro=,,,, 1 ,,,, 0 ,,,, 0 ,,,,-1 ,-1 ,-1 , 0 , 0 , 0 , 0 , 0
BR U #Sta/Elev= 97
  4032.5   42.57  4034.9   42.11  4042.5   40.66  4052.5   39.35  4092.5   37.97
  4332.5   38.74  4342.5   39.14  4402.5   38.39  4422.5   38.76  4442.5   38.83
  4452.5   38.24  4462.5   37.91  4472.5   37.86  4482.5   38.43  4562.5   38.37
  4572.5   38.62  4592.5   38.07  4642.5    38.6  4682.5   37.92  4712.5   38.37
  4732.5   38.12  4742.5   38.68  4782.5   37.96  4802.5   38.65  4822.5   38.21
  4832.5   38.64  4912.5   39.19  4922.5   39.61  4940.2   39.01 4952.63   38.28
 4972.73   37.06 4978.23   35.16 4979.33   34.78 4981.64   33.98 4981.73   33.95
 4995.83   29.07 4997.03   28.64 4999.43   28.71 5002.63   28.68 5004.23   29.01
 5015.62   33.06 5015.73    33.1 5015.83   33.13 5018.03   33.92 5028.93   37.79
  5040.5   38.67    5051   38.41    5091    36.3    5111    35.7    5121   36.18
    5151   34.92    5161   34.91    5171   35.23    5201    34.5    5211   34.79
    5221   35.66    5241   36.67    5321   36.99    5361   36.77    5381    37.3
    5441   36.89    5481   35.49    5501   35.29    5511   35.72    5531   37.38
    5541   37.81    5621   38.56  5674.9   38.48    5721   38.41    5731   38.99
    5751   38.21    5881   38.13    5901   37.39    5911   37.36    5931   38.01
  6006.1   38.13  6026.1   37.88  6156.1    38.3  6176.1   37.91  6296.1   37.82
  6316.1   37.41  6466.1   37.62  6586.1   36.86  6596.1   36.47  6616.1   34.86
  6636.1   34.31  6646.1   34.55  6656.1   35.62  6666.1   36.38  6726.1   37.17
  6976.1   37.02  6996.1   37.55  7006.1   37.55  7016.1   37.08  7056.1   36.84
  7086.1   37.72  7086.2    38.7
BR U #Mann= 5
  4032.5      .2  4034.9      .1 4972.73    .035 5028.93      .1  5674.9     .99
BR U Banks=4972.73,5028.93
BR D #Sta/Elev= 97
  4032.5   42.57  4034.9   42.11  4042.5   40.66  4052.5   39.35  4092.5   37.97
  4332.5   38.74  4342.5   39.14  4402.5   38.39  4422.5   38.76  4442.5   38.83
  4452.5   38.24  4462.5   37.91  4472.5   37.86  4482.5   38.43  4562.5   38.37
  4572.5   38.62  4592.5   38.07  4642.5    38.6  4682.5   37.92  4712.5   38.37
  4732.5   38.12  4742.5   38.68  4782.5   37.96  4802.5   38.65  4822.5   38.21
  4832.5   38.64  4912.5   39.19  4922.5   39.61  4940.2   39.01 4952.63   38.28
 4972.73   37.06 4978.23   35.16 4979.33   34.78 4981.64   33.98 4981.73   33.95
 4995.83   29.07 4997.03   28.64 4999.43   28.71 5002.63   28.68 5004.23   29.01
 5015.62   33.06 5015.73    33.1 5015.83   33.13 5018.03   33.92 5028.93   37.79
  5040.5   38.67    5051   38.41    5091    36.3    5111    35.7    5121   36.18
    5151   34.92    5161   34.91    5171   35.23    5201    34.5    5211   34.79
    5221   35.66    5241   36.67    5321   36.99    5361   36.77    5381    37.3
    5441   36.89    5481   35.49    5501   35.29    5511   35.72    5531   37.38
    5541   37.81    5621   38.56  5674.9   38.48    5721   38.41    5731   38.99
    5751   38.21    5881   38.13    5901   37.39    5911   37.36    5931   38.01
  6006.1   38.13  6026.1   37.88  6156.1    38.3  6176.1   37.91  6296.1   37.82
  6316.1   37.41  6466.1   37.62  6586.1   36.86  6596.1   36.47  6616.1   34.86
  6636.1   34.31  6646.1   34.55  6656.1   35.62  6666.1   36.38  6726.1   37.17
  6976.1   37.02  6996.1   37.55  7006.1   37.55  7016.1   37.08  7056.1   36.84
  7086.1   37.72  7086.2    38.7
BR D #Mann= 5
  4032.5      .2  4034.9      .1 4972.73    .035 5028.93      .1  5674.9     .99
BR D Banks=4972.73,5028.93
BC Design=,, 0 ,, 0 ,,,,,,
BC HTab HWMax=47.32
BC Use User HTab Curves=0
BC User HTab FreeFlow(D)= 0

Type RM Length L Ch R = 1 ,21465.5 ,239,239,239
BEGIN DESCRIPTION:
Downstream Section of Bridge/Culvert/Weir
END DESCRIPTION:
XS GIS Cut Line= 6
      3177709.15     13873261.71      3176898.31     13872853.63
      3176848.28     13872819.96      3176808.78     13872788.63
      3175938.74     13872394.43      3174940.89     13871981.22
#Sta/Elev= 30
  4032.5   42.55  4034.9   42.09  4052.5   39.33  4092.5   37.95  4342.5   39.12
  4472.5   37.84  4782.5   37.94  4922.5   39.59 4972.73   37.04 4997.03   28.62
 5004.23   28.99 5028.93   37.77  5040.5   38.65    5111   35.68    5201   34.48
    5241   36.65    5381   37.28    5501   35.27    5541   37.79  5674.9   38.46
    5911   37.34  6156.1   38.28  6466.1    37.6  6586.1   36.84  6636.1   34.29
  6666.1   36.36  6726.1   37.15  7056.1   36.82  7086.1    37.7  7086.2   38.68
#Mann= 5 , 1 , 0
  4032.5      .2       0  4034.9      .1       0 4972.73    .035       0
 5028.93      .1       0  5674.9     .99       0
#XS Ineff= 2 , 0
       0  4922.5   39.61  5040.5       0   33.67
Permanent Ineff=
       F       F
Bank Sta=4972.73,5028.93
XS Rating Curve= 0 ,0
Exp/Cntr=0.5,0.3

Type RM Length L Ch R = 1 ,21226.5 ,325.9,272.4,266.5
BEGIN DESCRIPTION:
Cross Section 21226.5-Interpolated
END DESCRIPTION:
XS GIS Cut Line= 4
      3177895.31     13873133.57      3177056.58     13872647.99
      3176911.54     13872572.31      3175502.88     13871949.65
#Sta/Elev= 30
  3930.5   44.61  3970.5   43.84  4000.5   39.79  4060.5   38.16  4390.5   38.92
  4450.5   38.49  4500.5   36.41  4540.5   38.27  4630.5   39.32  4760.5   37.77
  4800.5   35.85  4890.5   39.48  4978.8   38.15  4994.4   29.12  4999.4   28.04
  5007.5   30.14  5026.8   38.35  5073.3   38.84  5193.3   35.46  5353.3    37.5
  5453.3   36.29  5543.3    36.6  5643.3   34.72  5723.3   37.21  6100.5   37.51
  6313.3   37.52  6383.3   35.51  6423.3   37.24  6603.3   37.58  6603.4    38.6
#Mann= 5 , 1 , 0
  3930.5      .2       0  3930.5      .1       0  4978.8    .035       0
  5026.8      .1       0  6100.5     .99       0
#XS Ineff= 2 , 0
       0  4890.5   39.48  5925.7       0    38.9
Permanent Ineff=
       F       F
Bank Sta=4978.8,5026.8
XS Rating Curve= 0 ,0
Exp/Cntr=0.3,0.1

Type RM Length L Ch R = 1 ,20954.1 ,29.1,50,51.5
BEGIN DESCRIPTION:
Cross Section 20954.1-Interpolated
END DESCRIPTION:
XS GIS Cut Line= 4
      3178075.54     13872866.89      3177157.34     13872390.14
      3177057.28     13872343.05      3175463.39     13871751.78
#Sta/Elev= 30
  3896.8   41.05  3966.8   39.77  3996.8   37.42  4056.8   39.05  4346.8    38.5
  4456.8   37.88  4496.8   35.57  4546.8   38.07  4636.8    38.5  4726.8   38.66
  4766.8   37.64  4796.8   35.09  4916.8   38.86  4978.8    37.5  4994.4   28.47
  4999.4   27.39  5007.5   29.49  5026.8    37.7    5052   39.07    5132   38.01
    5162   35.68    5222   35.24    5492   35.69    5512   37.33    5802   36.61
    5862    35.2  6196.8   37.54    6262   37.87    6482   35.26    6742   38.39
#Mann= 5 , 1 , 0
  3896.8      .2       0  3896.8      .1       0  4978.8    .035       0
  5026.8      .1       0  6196.8     .99       0
#XS Ineff= 2 , 0
       0  4916.8   38.86 6115.56       0   39.07
Permanent Ineff=
       F       F
Bank Sta=4978.8,5026.8
XS Rating Curve= 0 ,0
Exp/Cntr=0.5,0.3