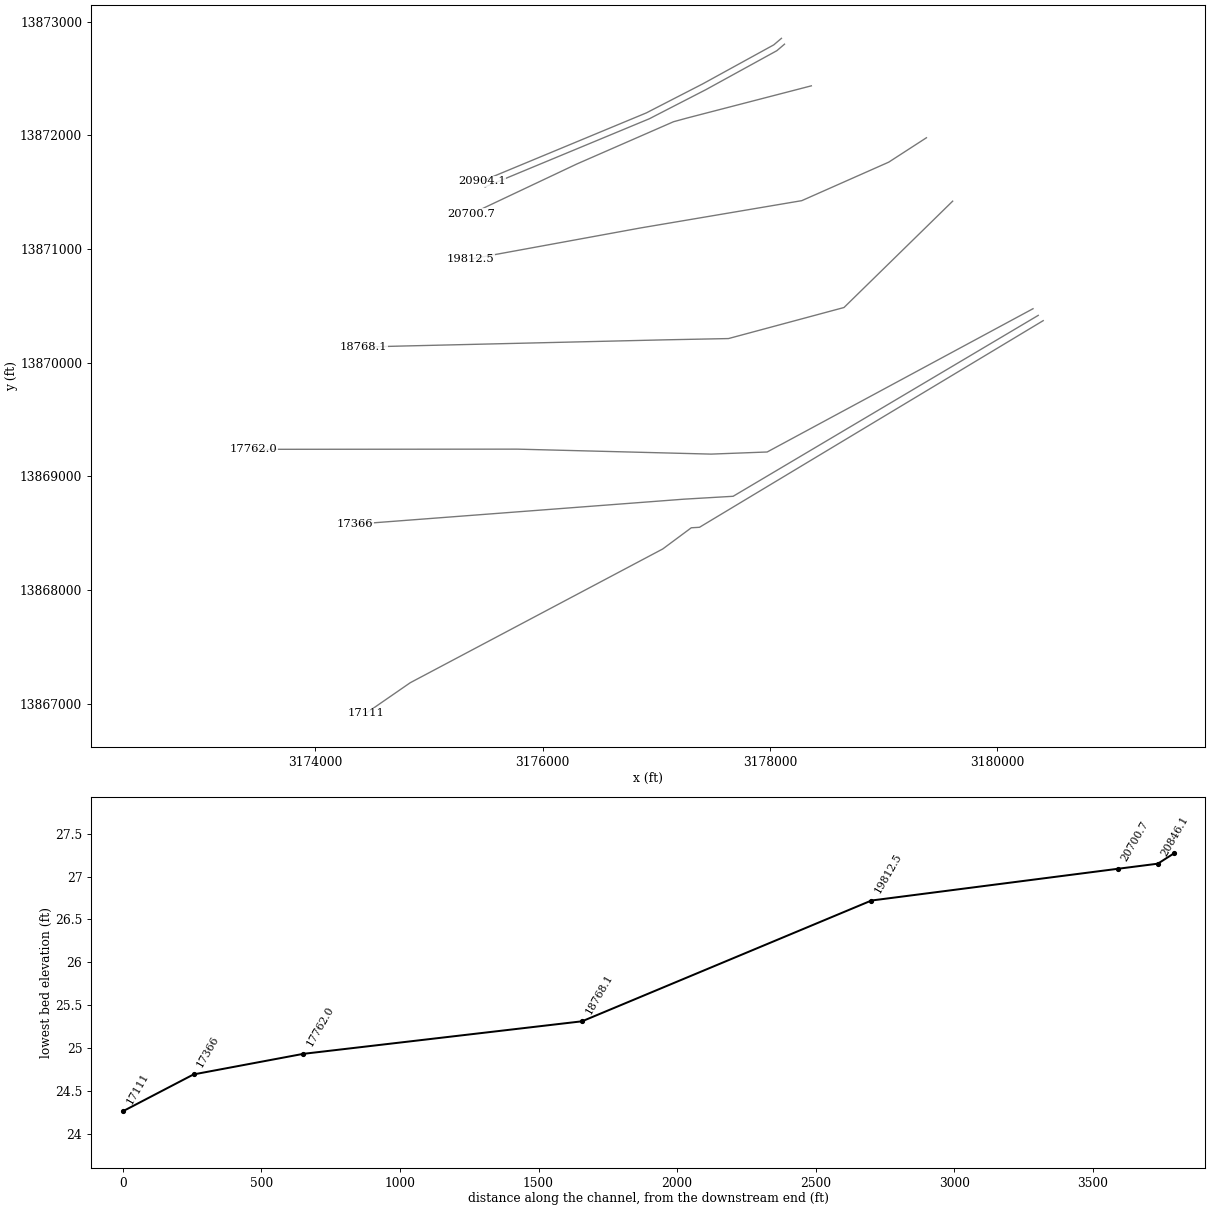
HEC-RAS study P107-00-00.prj: P107-00-00

--- P107-00-00.g01 (geometry) --- (continued)

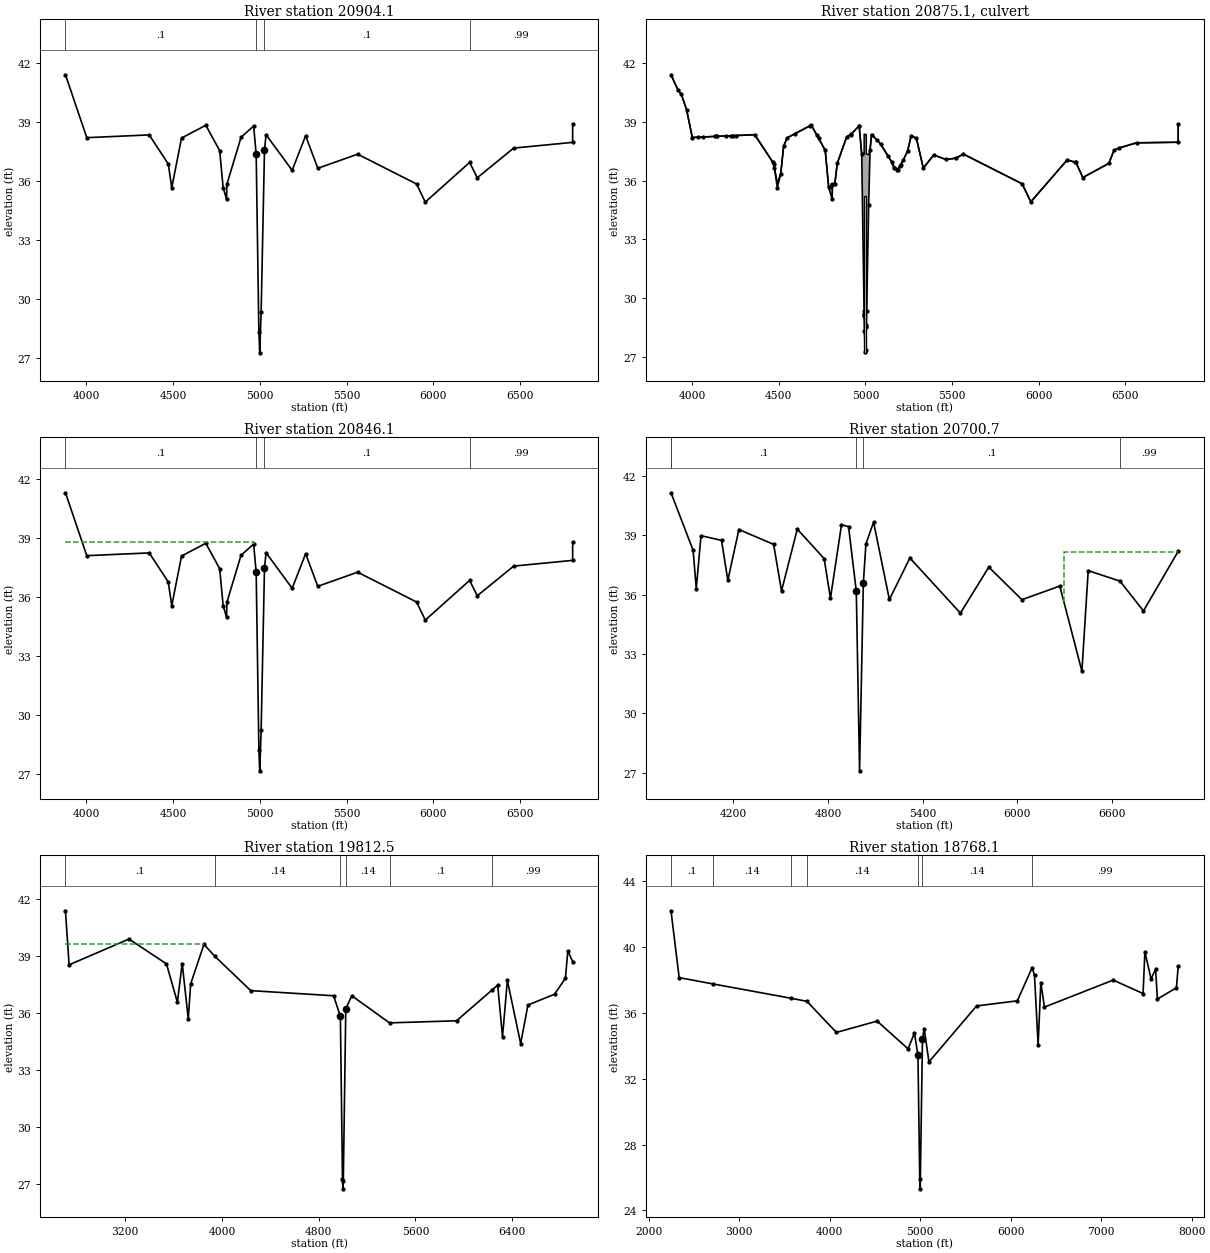
Type RM Length L Ch R = 1 ,20904.1 ,58,58,58
BEGIN DESCRIPTION:
Upstream Section of Bridge/Culvert/Weir
END DESCRIPTION:
XS GIS Cut Line= 6
      3178100.75     13872853.34      3178033.58     13872796.08
      3177408.73     13872452.94      3176961.71     13872222.95
      3176912.62     13872197.44      3175466.08     13871596.92
#Sta/Elev= 30
  3878.9   41.42  4001.9   38.22  4361.9   38.36  4471.9   36.88  4491.9   35.67
  4548.3    38.2  4688.3   38.85  4768.3   37.56  4788.3   35.68  4808.3   35.08
    4810   35.85  4891.6   38.24  4964.2   38.81  4978.8   37.38  4994.4   28.35
  4999.4   27.27  5007.5   29.37  5026.8   37.58  5035.7   38.37  5186.4   36.56
  5264.1   38.32  5334.1   36.66  5564.1   37.38  5904.1   35.86  5954.1   34.94
  6209.8   36.96  6254.1   36.18  6464.1   37.69  6804.1   37.98  6804.2   38.92
#Mann= 4 , 1 , 0
  3878.9      .1       0  4978.8    .035       0  5026.8      .1       0
  6209.8     .99       0
#XS Ineff= 2 , 0
       0  4964.2   38.79  5035.7       0      35
Permanent Ineff=
       F       F
Bank Sta=4978.8,5026.8
XS Rating Curve= 0 ,0
Exp/Cntr=0.5,0.3

Type RM Length L Ch R = 2 ,20875.1 ,,,
BEGIN DESCRIPTION:
VILLAGROVE
Structure ID: P07-10
END DESCRIPTION:
Bridge Culvert--1,0,-1,-1, 0
Deck Dist Width WeirC Skew NumUp NumDn MinLoCord MaxHiCord MaxSubmerge Is_Ogee
10,38,3,0, 57, 57, , , 0.95, 0, 1,1,,
  3878.9  3918.9  3938.9  3968.9  4001.9  4361.9  4471.9  4491.9  4511.9  4528.3
  4548.3  4688.3  4768.3  4788.3  4808.3    4810  4823.9  4837.9  4891.6  4918.2
  4964.2  4978.8 4992.79  4992.9  4994.4  4999.4  5001.5  5005.2 5005.31  5007.5
  5018.9  5026.8  5035.7  5087.5  5151.8  5163.9  5186.4  5218.3  5244.1  5264.1
  5294.1  5334.1  5394.1  5464.1  5524.1  5564.1  5904.1  5954.1  6164.1  6214.1
  6254.1  6404.1  6434.1  6464.1  6564.1  6804.1  6804.2
    41.4   40.63    40.4   39.61    38.2   38.35   36.87   35.87   36.36   37.76
   38.19   38.84   37.55   35.67   35.59   35.84   35.86   36.89   38.23   38.38
    38.8   37.39   37.37   38.37   38.37   38.36   38.36   38.35   37.35   37.35
   37.33   37.57   38.36   37.88   36.96   36.74   36.59   37.04   37.53    38.3
   38.16   36.64   37.31   37.08   37.15   37.36   35.84   34.92   37.06   36.93
   36.16   36.88   37.55   37.67   37.93   37.96    38.9
    41.4   40.63    40.4   39.61    38.2   38.34   36.86   35.65   36.35   37.75
   38.18   38.83   37.54   35.66   35.06   35.83   35.85   36.88   38.22   38.37
   38.79   37.36   29.21   29.15   28.33   27.25   27.34   28.58   28.62   29.35
   34.75   37.56   38.35   37.87   36.95   36.65   36.54   37.04   37.53    38.3
   38.16   36.64   37.31   37.08   37.15   37.36   35.84   34.92   37.06   36.93
   36.16   36.88   37.55   37.67   37.93   37.96    38.9
  3878.9  3918.9  3938.9  3968.9  4001.9  4361.9  4471.9  4491.9  4511.9  4528.3
  4548.3  4688.3  4768.3  4788.3  4808.3    4810  4823.9  4837.9  4891.6  4918.2
  4964.2  4978.8 4992.79  4992.9  4994.4  4999.4  5001.5  5005.2 5005.31  5007.5
  5018.9  5026.8  5035.7  5087.5  5151.8  5163.9  5186.4  5218.3  5244.1  5264.1
  5294.1  5334.1  5394.1  5464.1  5524.1  5564.1  5904.1  5954.1  6164.1  6214.1
  6254.1  6404.1  6434.1  6464.1  6564.1  6804.1  6804.2
    41.4   40.63    40.4   39.61    38.2   38.35   36.87   35.87   36.36   37.76
   38.19   38.84   37.55   35.67   35.59   35.84   35.86   36.89   38.23   38.38
    38.8   37.39   37.37   38.37   38.37   38.36   38.36   38.35   37.35   37.35
   37.33   37.57   38.36   37.88   36.96   36.74   36.59   37.04   37.53    38.3
   38.16   36.64   37.31   37.08   37.15   37.36   35.84   34.92   37.06   36.93
   36.16   36.88   37.55   37.67   37.93   37.96    38.9
    41.3   40.53    40.3   39.51    38.1   38.24   36.76   35.55   36.25   37.65
   38.08   38.73   37.44   35.56   34.96   35.73   35.75   36.78   38.12   38.27
   38.69   37.26   29.11   29.05   28.23   27.15   27.24   28.48   28.52   29.25
   34.65   37.46   38.25   37.77   36.85   36.55   36.44   36.94   37.43    38.2
   38.06   36.54   37.21   36.98   37.05   37.26   35.74   34.82   36.96   36.83
   36.06   36.78   37.45   37.57   37.83   37.86    38.8
BR Coef= 1 , 0 , 0 ,1.25, 0 ,,,0.8,-1,2,0,
WSPro=,,,, 1 ,,,, 0 ,,,, 0 ,,,,-1 ,-1 ,-1 , 0 , 0 , 0 , 0 , 0
Culvert=2,8,8,38,0.015,0.4,1,8,1,27.22,4998.8,27.28,4998.8,Culvert #1  , 0 ,10
Culvert Bottom n=0.015
BR U #Sta/Elev= 84
  3878.9    41.4  3918.9   40.63  3938.9    40.4  3968.9   39.61  4001.9    38.2
  4035.7   38.22  4065.7   38.23  4131.9   38.26  4135.7   38.26  4145.7   38.26
  4195.7   38.28  4225.7   38.29  4235.7    38.3  4255.7    38.3  4361.9   38.34
  4465.7   36.94  4471.9   36.86  4475.7   36.63  4491.9   35.65  4511.9   36.35
  4528.3   37.75  4548.3   38.18  4595.7    38.4    4680   38.79  4688.3   38.83
    4720   38.32    4730   38.16  4768.3   37.54  4788.3   35.66  4808.3   35.06
  4809.9   35.78    4810   35.83  4823.9   35.85  4837.9   36.88  4891.6   38.22
  4914.3   38.35  4918.2   38.37  4963.8   38.79  4964.2   38.79  4978.8   37.36
  4992.5   29.37 4992.79   29.21  4992.9   29.15 4993.01   29.09  4994.4   28.33
  4999.4   27.25  5001.5   27.34 5005.09   28.54  5005.2   28.58 5005.31   28.62
  5007.5   29.35  5018.9   34.75  5026.8   37.56  5035.7   38.35  5066.3   38.07
  5087.5   37.87  5130.1   37.26  5151.8   36.95  5163.9   36.65  5185.1   36.55
  5186.4   36.54    5200   36.75  5204.3   36.82  5218.3   37.04  5244.1   37.53
  5264.1    38.3  5294.1   38.16  5334.1   36.64  5394.1   37.31  5464.1   37.08
  5524.1   37.15  5564.1   37.36  5904.1   35.84  5954.1   34.92  6164.1   37.06
  6209.8   36.94  6214.1   36.93  6254.1   36.16  6404.1   36.88  6434.1   37.55
  6464.1   37.67  6564.1   37.93  6804.1   37.96  6804.2    38.9
BR U #Mann= 4
  3878.9      .1  4978.8    .035  5026.8      .1  6209.8     .99
BR U Banks=4978.8,5026.8
BR D #Sta/Elev= 84
  3878.9    41.3  3918.9   40.53  3938.9    40.3  3968.9   39.51  4001.9    38.1
  4035.7   38.12  4065.7   38.13  4131.9   38.16  4135.7   38.16  4145.7   38.16
  4195.7   38.18  4225.7   38.19  4235.7    38.2  4255.7    38.2  4361.9   38.24
  4465.7   36.84  4471.9   36.76  4475.7   36.53  4491.9   35.55  4511.9   36.25
  4528.3   37.65  4548.3   38.08  4595.7    38.3    4680   38.69  4688.3   38.73
    4720   38.22    4730   38.06  4768.3   37.44  4788.3   35.56  4808.3   34.96
  4809.9   35.68    4810   35.73  4823.9   35.75  4837.9   36.78  4891.6   38.12
  4914.3   38.25  4918.2   38.27  4963.8   38.69  4964.2   38.69  4978.8   37.26
  4992.5   29.27 4992.79   29.11  4992.9   29.05 4993.01   28.99  4994.4   28.23
  4999.4   27.15  5001.5   27.24 5005.09   28.44  5005.2   28.48 5005.31   28.52
  5007.5   29.25  5018.9   34.65  5026.8   37.46  5035.7   38.25  5066.3   37.97
  5087.5   37.77  5130.1   37.16  5151.8   36.85  5163.9   36.55  5185.1   36.45
  5186.4   36.44    5200   36.65  5204.3   36.72  5218.3   36.94  5244.1   37.43
  5264.1    38.2  5294.1   38.06  5334.1   36.54  5394.1   37.21  5464.1   36.98
  5524.1   37.05  5564.1   37.26  5904.1   35.74  5954.1   34.82  6164.1   36.96
  6209.8   36.84  6214.1   36.83  6254.1   36.06  6404.1   36.78  6434.1   37.45
  6464.1   37.57  6564.1   37.83  6804.1   37.86  6804.2    38.8
BR D #Mann= 4
  3878.9      .1  4978.8    .035  5026.8      .1  6209.8     .99
BR D Banks=4978.8,5026.8
BC Design=,, 0 ,, 0 ,,,,,,
BC HTab HWMax=41.42
BC Use User HTab Curves=0
BC User HTab FreeFlow(D)= 0

Type RM Length L Ch R = 1 ,20846.1 ,145.4,145.4,145.4
BEGIN DESCRIPTION:
Downstream Section of Bridge/Culvert/Weir
END DESCRIPTION:
XS GIS Cut Line= 6
      3178127.93      13872802.1      3178060.76     13872744.84
      3177435.91      13872401.7      3176988.89     13872171.71
       3176939.8      13872146.2      3175493.26     13871545.68
#Sta/Elev= 30
  3878.9    41.3  4001.9    38.1  4361.9   38.24  4471.9   36.76  4491.9   35.55
  4548.3   38.08  4688.3   38.73  4768.3   37.44  4788.3   35.56  4808.3   34.96
    4810   35.73  4891.6   38.12  4964.2   38.69  4978.8   37.26  4994.4   28.23
  4999.4   27.15  5007.5   29.25  5026.8   37.46  5035.7   38.25  5186.4   36.44
  5264.1    38.2  5334.1   36.54  5564.1   37.26  5904.1   35.74  5954.1   34.82
  6209.8   36.84  6254.1   36.06  6464.1   37.57  6804.1   37.86  6804.2    38.8
#Mann= 4 , 1 , 0
  3878.9      .1       0  4978.8    .035       0  5026.8      .1       0
  6209.8     .99       0
#XS Ineff= 2 , 0
       0  4964.2   38.79  5035.7       0      35
Permanent Ineff=
       F       F
Bank Sta=4978.8,5026.8
XS Rating Curve= 0 ,0
Exp/Cntr=0.5,0.3

Type RM Length L Ch R = 1 ,20700.7 ,929.4,888.2,741.6
BEGIN DESCRIPTION:
Cross Section 20700.7-Interpolated
END DESCRIPTION:
XS GIS Cut Line= 5
      3178363.89     13872435.36      3177275.17     13872153.31
      3177151.06     13872119.46      3176299.27     13871747.15
      3175367.97     13871307.04
#Sta/Elev= 30
  3805.9   41.16  3945.9   38.25  3965.9   36.31  3995.9   38.99  4125.9   38.75
  4165.9   36.73  4235.9    39.3  4455.9   38.55  4505.9   36.19  4605.9   39.32
  4775.9   37.83  4815.9   35.82  4885.9   39.54  4930.6   39.45  4979.6   36.18
  5000.4   27.09  5024.3   36.58  5040.6   38.57  5089.2   39.67  5189.2   35.76
  5319.2   37.86  5639.2   35.07  5819.2    37.4  6028.8   35.75  6268.8   36.44
  6408.8   32.13  6448.8   37.22  6649.9   36.69  6798.8   35.18  7018.9    38.2
#Mann= 5 , 1 , 0
  3805.9      .2       0  3805.9      .1       0  4979.6    .035       0
  5024.3      .1       0  6649.9     .99       0
#XS Ineff= 2 , 0
       0  4885.9   39.54  6295.2       0   38.15
Permanent Ineff=
       F       F
Bank Sta=4979.6,5024.3
XS Rating Curve= 0 ,0
Exp/Cntr=0.3,0.1

Type RM Length L Ch R = 1 ,19812.5 ,1054.7,1044.4,1034.8
BEGIN DESCRIPTION:
Cross Section 19812.5
END DESCRIPTION:
XS GIS Cut Line= 6
      3179376.75     13871978.57      3179044.91     13871763.85
      3178279.64     13871424.95       3177426.7      13871280.6
      3176858.43     13871184.43      3175363.18     13870910.81
#Sta/Elev= 30
  2706.5   41.38  2736.5   38.53  3231.8   39.89  3541.8   38.58  3631.8   36.56
  3671.8    38.6  3721.8   35.68  3741.8   37.53  3851.8   39.61  3939.9   38.99
  4238.7   37.17  4923.8    36.9  4979.6   35.81  4996.9   27.26  5000.4   26.72
  5003.9   27.15  5024.3   36.21  5073.8    36.9  5385.8   35.47  5940.2   35.58
  6236.5   37.22  6280.2   37.46  6320.2   34.73  6360.2   37.71  6470.2   34.38
  6530.2   36.41  6750.2   36.98  6840.2   37.82  6860.2   39.26  6900.2    38.7
#Mann= 6 , 1 , 0
  2706.5      .1       0  3939.9     .14       0  4979.6    .035       0
  5024.3     .14       0  5385.8      .1       0  6236.5     .99       0
#XS Ineff= 2 , 0
       0    3852   39.65               0
Permanent Ineff=
       F       F
Bank Sta=4979.6,5024.3
XS Rating Curve= 0 ,0
Exp/Cntr=0.3,0.1

Type RM Length L Ch R = 1 ,18768.1 ,1136.7,1006.1,993.7
BEGIN DESCRIPTION:
Cross Section 18768.1
END DESCRIPTION:
XS GIS Cut Line= 6
      3179607.55     13871420.62      3178651.34     13870484.76
      3177634.63     13870211.45      3177088.01     13870200.51
      3174770.33     13870145.85      3174420.47     13870136.95
#Sta/Elev= 30
  2245.8    42.2  2335.8   38.14  2706.2   37.76  3569.3   36.89  3747.9    36.7
  4073.7   34.81  4523.7    35.5  4866.5   33.81  4936.5   34.78  4975.2   33.41
  4994.8   25.93  4999.9   25.31  5025.2   34.44  5044.2   35.03  5096.5   33.02
  5623.3   36.42  6073.3   36.73  6237.5   38.75  6263.3   38.27  6303.3   34.06
  6333.3   37.83  6373.3   36.35  7133.3   37.99  7463.3   37.17  7483.3   39.71
  7551.6   38.06  7601.6   38.65  7621.6   36.84  7831.6   37.52  7851.6   38.82
#Mann= 7 , 1 , 0
  2245.8      .1       0  2706.2     .14       0  3569.3      .1       0
  3747.9     .14       0  4975.2    .035       0  5025.2     .14       0
  6237.5     .99       0
Bank Sta=4975.2,5025.2
XS Rating Curve= 0 ,0
Exp/Cntr=0.3,0.1

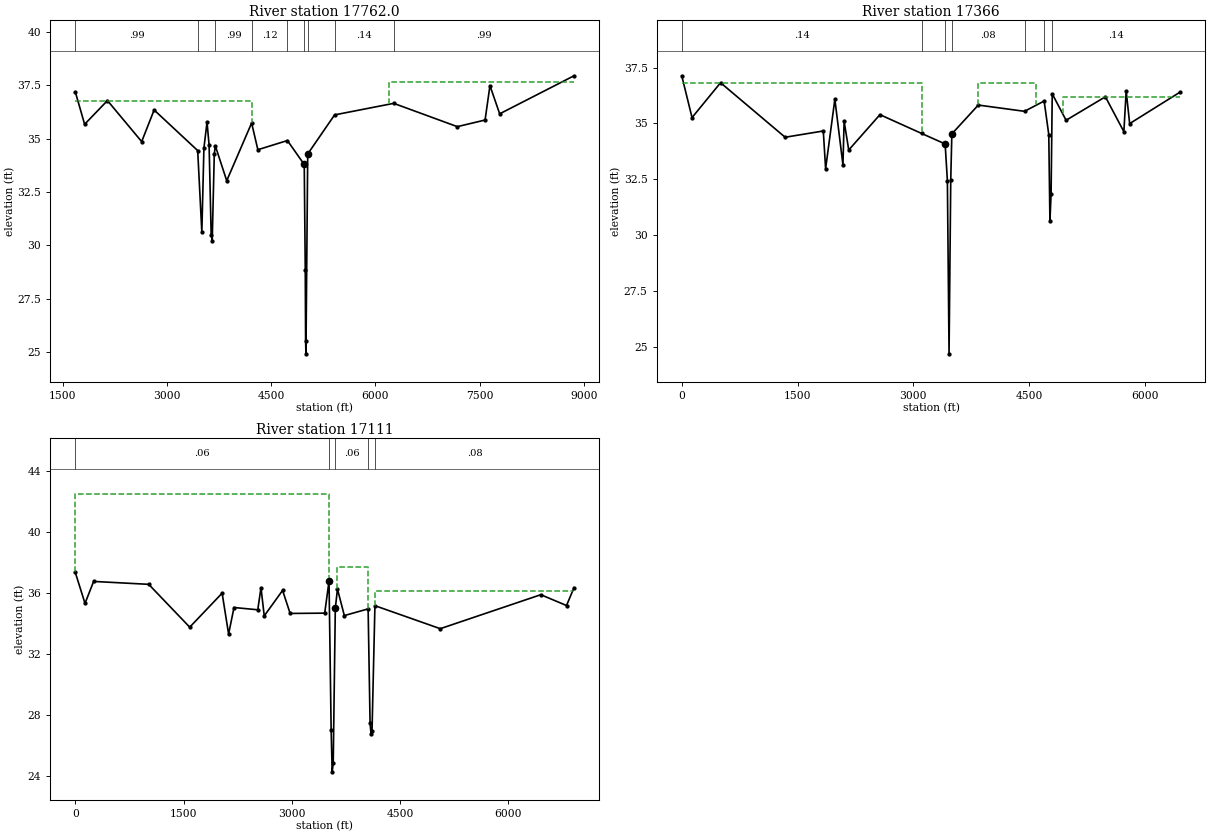
Type RM Length L Ch R = 1 ,17762.0 ,261,396,451
BEGIN DESCRIPTION:
Cross Section 17762.0 - Revised left overbank to align with US 90 embankment
END DESCRIPTION:
XS GIS Cut Line= 6
   3180314.58148 13870474.180481  3177975.118967 13869213.333922
  3177481.570086 13869194.729956  3175776.120085 13869238.459856
  3173880.724269 13869237.128493  3173456.069935 13869236.829938
#Sta/Elev= 30
  1680.3   37.19 1814.67   35.67 2143.14   36.78 2635.84   34.86    2815   36.34
 3442.08   34.44  3501.8   30.62 3531.66   34.56 3576.45   35.77 3606.31   34.69
 3636.17    30.5  3651.1   30.23 3680.96   34.28 3695.89   34.66 3860.13   33.03
 4218.45   35.73 4308.04   34.48  4733.2   34.91  4975.7   33.79  4990.5   28.85
  4995.2   25.55  5000.2   24.93  5025.7   34.28  5412.5   36.11  6263.1   36.65
  7178.6   35.56  7578.6   35.87  7648.6   37.48  7788.6   36.16  8858.6   37.94
#Mann= 9 ,-1 , 0
  1680.3     .99       0 3442.08      .1       0 3695.89     .99       0
 4218.45     .12       0  4733.2     .08       0  4975.7     .04       0
  5025.7     .08       0  5412.5     .14       0  6263.1     .99       0
#XS Ineff= 2 , 0
       0 4218.45   36.78  6202.5       0   37.67
Permanent Ineff=
       F       F
Bank Sta=4975.7,5025.7
XS Rating Curve= 0 ,0
Exp/Cntr=0.3,0.1

Type RM Length L Ch R = 1 ,17366   ,94,255,495
XS GIS Cut Line= 5
  3180360.545299 13870415.502777 3179775.532361413870068.6389694
 3177675.702899613868823.6155408  3177241.10271913868798.0568649
 3174346.452616813868577.4884869
#Sta/Elev= 30
       0   37.13  133.07   35.26  502.69   36.82 1339.08   34.38 1833.31   34.66
 1863.26   32.97 1983.08   36.08 2087.91   33.14 2102.89    35.1 2162.79   33.81
 2567.16   35.39 3106.31   34.55 3411.53   34.08 3440.55   32.44 3462.11   24.69
 3484.08   32.46 3498.32   34.53 3840.96   35.82 4439.53   35.54 4693.92      36
 4753.78    34.5 4768.74   30.62 4783.71   31.85 4798.67   36.32 4978.24   35.14
 5487.03   36.19 5726.46   34.63 5756.39   36.45 5801.28   34.99 6459.71   36.41
#Mann= 7 ,-1 , 0
       0     .14       0 3106.31     .08       0 3411.53     .04       0
 3498.32     .08       0 4439.53     .14       0 4693.92     .04       0
 4798.67     .14       0
#XS Ineff= 3 ,-1
       0 3106.31   36.82 3840.96 4589.17   36.82 4933.35 6459.71    36.2
Permanent Ineff=
       F       F       F
Bank Sta=3411.53,3498.32
XS Rating Curve= 0 ,0
Exp/Cntr=0.5,0.3

Type RM Length L Ch R = 1 ,17111   ,112,127,84
BEGIN DESCRIPTION:
New section cut to align with US 90 embankment
END DESCRIPTION:
XS GIS Cut Line= 6
 3180404.425460513870369.2230139 3177379.6687148 13868550.742727
 3177307.719383613868546.5114363 3177056.448888813868360.1502604
 3174834.5940805 13867183.084045 3174444.050911513866913.2909523
#Sta/Elev= 30
       0   37.34  134.56   35.31  254.16   36.75 1016.76   36.56 1585.08   33.75
 2033.75   35.98 2123.48    33.3 2198.26   35.04 2527.28   34.89 2572.15   36.34
 2617.01   34.49 2871.26   36.16 2975.95   34.65 3454.53   34.67 3514.35   36.77
 3543.72   27.03 3558.13   24.26 3572.55   24.82 3601.38   34.98 3631.14   36.25
 3726.39   34.51 4055.93   34.95 4082.85   27.46 4096.31   26.74 4109.78   26.91
 4150.17   35.16 5054.94   33.65 6447.77   35.88 6803.77   35.17  6907.6   36.34
#Mann= 5 ,-1 , 0
       0     .06       0 3514.35     .04       0 3601.38     .06       0
 4055.93     .04       0 4150.17     .08       0
#XS Ineff= 3 ,-1
       0 3514.35    42.5 3631.14 4055.93    37.7 4151.17  6907.6    36.1
Permanent Ineff=
       F       F       F
Bank Sta=3514.35,3601.38
XS Rating Curve= 0 ,0
Exp/Cntr=0.5,0.3