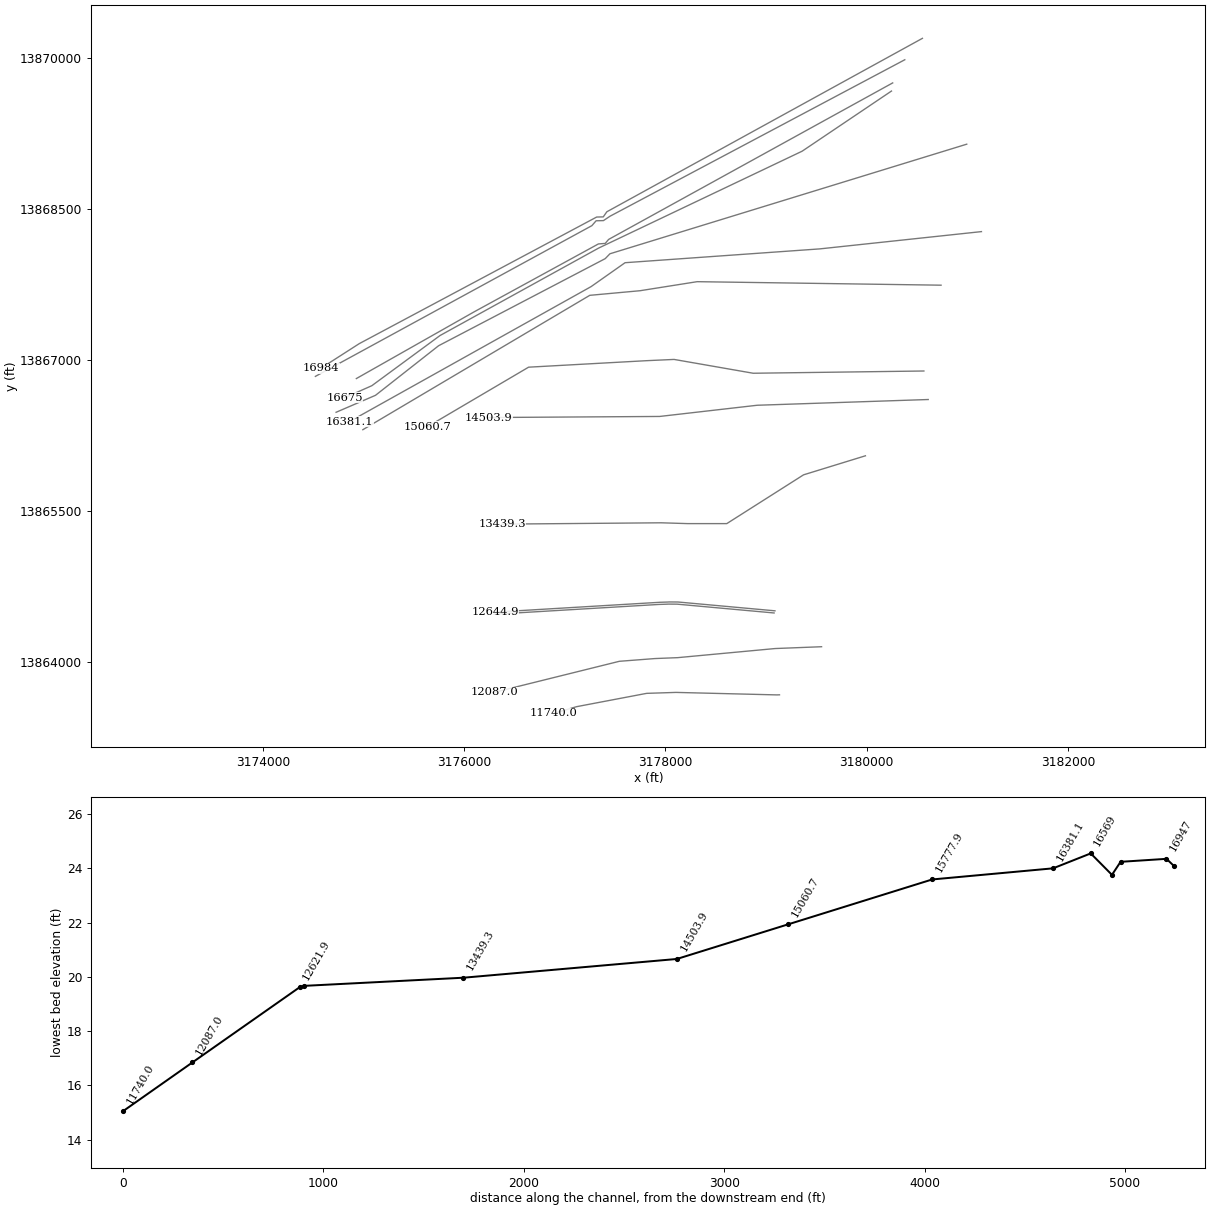
HEC-RAS study P107-00-00.prj: P107-00-00

--- P107-00-00.g01 (geometry) --- (continued)

Type RM Length L Ch R = 4 ,17048   ,,,
BEGIN DESCRIPTION:
Westbound Feeder US 90 - two culverts that both contribute to conveyance
END DESCRIPTION:
Bridge Culvert--1,0,-1,-1, 0
Deck Dist Width WeirC Skew NumUp NumDn MinLoCord MaxHiCord MaxSubmerge Is_Ogee
34,79.5,2.6,0, 124, 124, , , 0.98, 0, 0,0,,
       0   49.15     100     200  252.48     300  372.61     400  472.42     500
  559.33     600  642.45     700  700.58   777.2     800  804.59  863.27     900
  938.03    1000 1045.47    1100 1163.16    1200 1238.52    1300 1357.12    1400
 1440.78    1500 1500.83    1600    1700 1759.46    1800    1900    2000 2000.27
    2100    2200  2308.4 2445.09 2462.98 2484.35 2484.35 2673.91 2850.73  3032.8
 3061.38  3187.8 3232.45 3411.97 3595.43 3783.34 3967.72  4156.2 4342.14 4342.14
  4527.1 4555.95 4710.23 4841.11 4900.36 5063.74 5082.57 5262.35 5262.35 5441.51
    5583 5586.71 5609.95 5611.86 5613.54 5655.47 5740.94 5759.31 5759.44 5759.54
 5905.47 5905.54 5905.57 5943.96  6052.9 6053.34 6053.75 6081.58 6086.53    6097
 6194.91 6195.58 6207.88 6340.57 6341.15 6342.33 6439.62 6483.23 6483.77 6484.38
 6562.77 6628.24  6628.7 6665.59  6676.6 6697.17 6774.33 6774.91  6775.6 6796.76
 6896.84 6923.45 6924.21 7002.64 7072.23 7073.01 7106.33 7184.33 7223.62 7224.58
 7225.78 7262.41 7317.13 7369.32
   36.96   36.63   36.28   35.73   36.02   35.97   36.15    36.2   36.34    36.4
   36.44   36.46   36.59    36.4    36.4   36.21   36.13   36.16      36   35.75
    35.8   35.35   35.57   35.79   35.65   35.58    35.5   35.41   35.32   35.27
   35.19   35.11   35.11   34.69   34.85   35.04   35.13   35.69   35.83   35.83
   35.92   35.41   35.79   36.27   36.33    36.4    36.4   36.94   36.36    36.7
   36.78   37.17   37.31   38.63   40.51   40.05   38.01   37.24   36.49   36.49
   36.01    36.1   36.59   36.81   36.91   36.18    36.1   36.47   36.47   37.04
   37.64   37.65   37.75   37.76   37.76   37.86   38.04    38.1    38.1    38.1
    37.7    37.7    37.7   37.59   37.29   37.29    37.3   37.25   37.24   37.23
   37.06   37.06   37.11   37.63   37.63   37.63   37.99   38.14   38.14   38.14
   38.11   38.06   38.06   37.91   37.86   37.77   37.44   37.43   37.43   37.38
   37.15   37.09   37.09   37.21   37.32   37.32    37.4   37.61   37.73   37.72
   37.72   37.62    37.5    37.4
                                                                                
                                                                                
                                                                                
                                                                                
                                                                                
                                                                                
                                                                                
                                                                                
                                                                                
                                                                                
                                                                                
                                                                                
                                
       0   49.15     100     200  252.48     300  372.61     400  472.42     500
  559.33     600  642.45     700  700.58   777.2     800  804.59  863.27     900
  938.03    1000 1045.47    1100 1163.16    1200 1238.52    1300 1357.12    1400
 1440.78    1500 1500.83    1600    1700 1759.46    1800    1900    2000 2000.27
    2100    2200  2308.4 2445.09 2462.98 2484.35 2484.35 2673.91 2850.73  3032.8
 3061.38  3187.8 3232.45 3411.97 3595.43 3783.34 3967.72  4156.2 4342.14 4342.14
  4527.1 4555.95 4710.23 4841.11 4900.36 5063.74 5082.57 5262.35 5262.35 5441.51
    5583 5586.71 5609.95 5611.86 5613.54 5655.47 5740.94 5759.31 5759.44 5759.54
 5905.47 5905.54 5905.57 5943.96  6052.9 6053.34 6053.75 6081.58 6086.53    6097
 6194.91 6195.58 6207.88 6340.57 6341.15 6342.33 6439.62 6483.23 6483.77 6484.38
 6562.77 6628.24  6628.7 6665.59  6676.6 6697.17 6774.33 6774.91  6775.6 6796.76
 6896.84 6923.45 6924.21 7002.64 7072.23 7073.01 7106.33 7184.33 7223.62 7224.58
 7225.78 7262.41 7317.13 7369.32
   36.96   36.63   36.28   35.73   36.02   35.97   36.15    36.2   36.34    36.4
   36.44   36.46   36.59    36.4    36.4   36.21   36.13   36.16      36   35.75
    35.8   35.35   35.57   35.79   35.65   35.58    35.5   35.41   35.32   35.27
   35.19   35.11   35.11   34.69   34.85   35.04   35.13   35.69   35.83   35.83
   35.92   35.41   35.79   36.27   36.33    36.4    36.4   36.94   36.36    36.7
   36.78   37.17   37.31   38.63   40.51   40.05   38.01   37.24   36.49   36.49
   36.01    36.1   36.59   36.81   36.91   36.18    36.1   36.47   36.47   37.04
   37.64   37.65   37.75   37.76   37.76   37.86   38.04    38.1    38.1    38.1
    37.7    37.7    37.7   37.59   37.29   37.29    37.3   37.25   37.24   37.23
   37.06   37.06   37.11   37.63   37.63   37.63   37.99   38.14   38.14   38.14
   38.11   38.06   38.06   37.91   37.86   37.77   37.44   37.43   37.43   37.38
   37.15   37.09   37.09   37.21   37.32   37.32    37.4   37.61   37.73   37.72
   37.72   37.62    37.5    37.4
                                                                                
                                                                                
                                                                                
                                                                                
                                                                                
                                                                                
                                                                                
                                                                                
                                                                                
                                                                                
                                                                                
                                                                                
                                
BR Coef=-1 , 0 , 0 ,, 0 ,,,0.8,-1,,0,
WSPro=,,,, 1 ,,,, 0 ,,,, 0 ,,,,-1 ,-1 ,-1 , 0 , 0 , 0 , 0 , 0
Multiple Barrel Culv=2,12,12,79.5,0.012,0.2,1,11,2,23.97,24.11, 3,Culvert #1  , 0 ,34
    3546    3656    3562    3672    3578    3688
Culvert Bottom n=0.012
Culvert=2,8,8,81,0.012,0.2,1,11,2,26,4097,25.2,4087,Culvert #2  , 0 ,34
Culvert Bottom n=0.012
BC Mult= 2 ,0,4000,0,3960
BC Mult= 2 ,3670,6910,3800,6830
BC Design=,, 0 ,, 0 ,,,,,,
BC HTab HWMax=37.57
BC Use User HTab Curves=0
BC User HTab FreeFlow(D)= 0

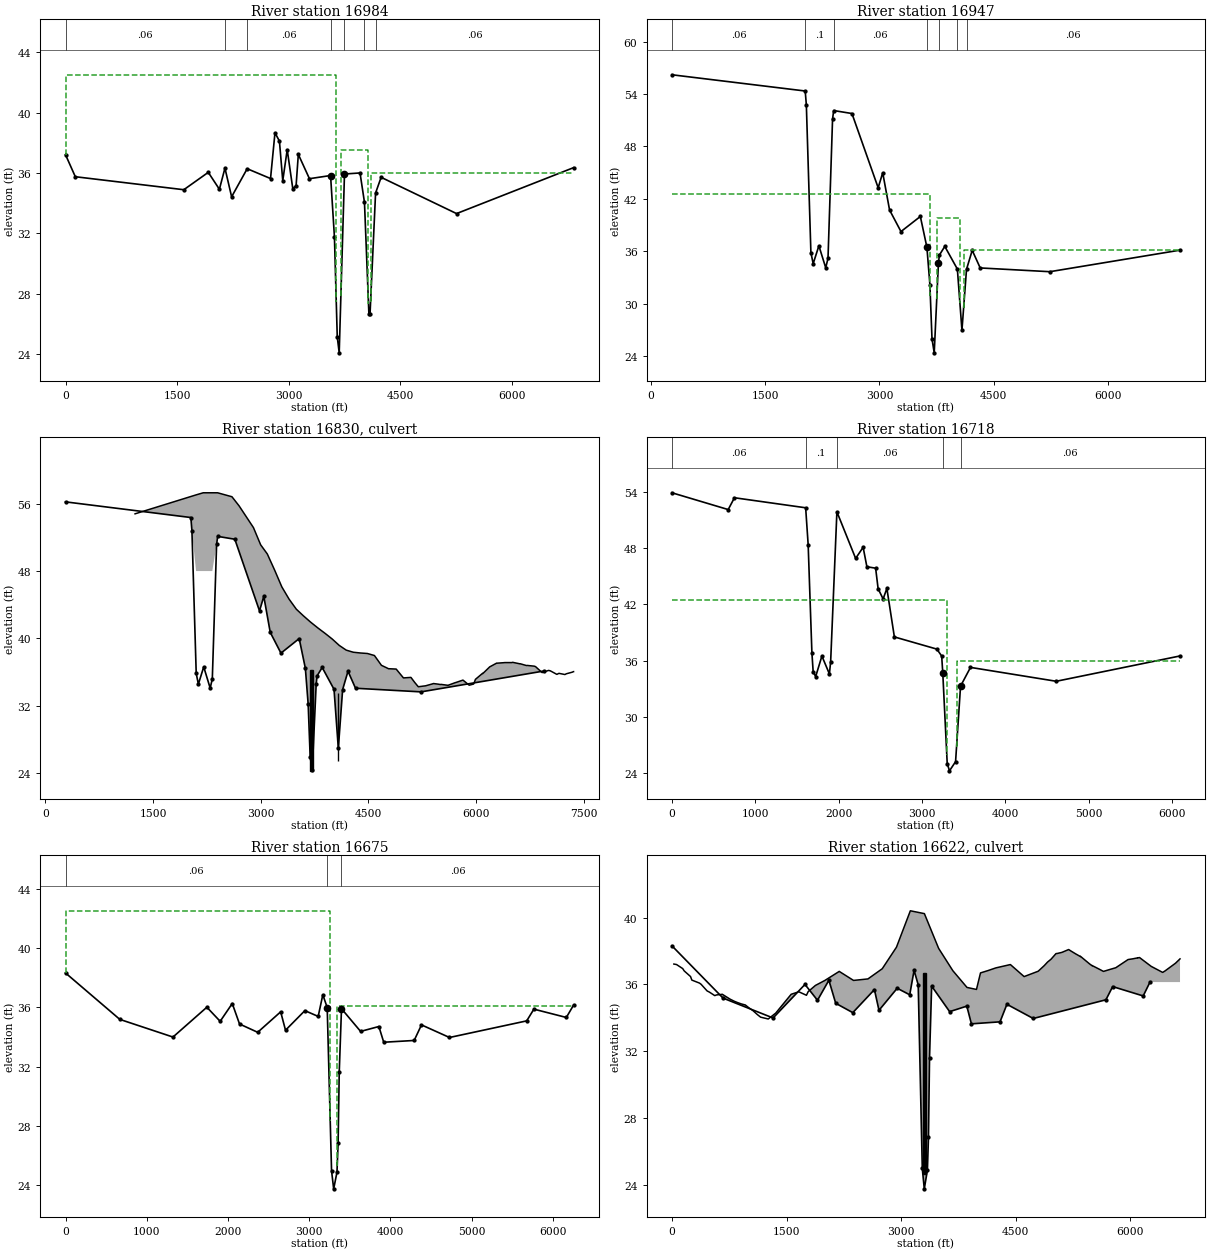
Type RM Length L Ch R = 1 ,16984   ,63,37,37
BEGIN DESCRIPTION:
New section cut to align with US 90 embankment
END DESCRIPTION:
XS GIS Cut Line= 6
 3180554.0980614 13870196.845734 3177418.290356713868473.3514776
 3177382.794364713868422.6914739 3177317.339443113868421.2147709
 3174958.140749413867163.0765391 3174579.698101413866920.2310252
#Sta/Elev= 30
       0   37.21  131.95   35.75  1590.4   34.89 1919.22   36.04 2068.68   34.92
 2143.41   36.32 2233.08   34.42 2442.33   36.28 2756.19   35.63 2815.98   38.66
 2875.76   38.11  2920.6   35.49 2980.39   37.54 3055.12   34.97 3099.95   35.16
 3129.85   37.23 3279.31   35.62 3563.28   35.83 3615.34   31.75 3653.18   25.15
 3679.37   24.09 3750.38   35.93 3959.52      36 4019.18   34.05 4078.83   26.63
 4093.75   26.65 4168.31   34.67 4242.88   35.71    5257   33.31 6829.74   36.35
#Mann= 7 ,-1 , 0
       0     .06       0 2143.41      .1       0 2442.33     .06       0
 3563.28     .04       0 3750.38     .06       0 4019.18     .04       0
 4168.31     .06       0
#XS Ineff= 3 ,-1
       0    3640    42.5    3702    4073    37.5    4101 6829.74      36
Permanent Ineff=
       F       F       F
Bank Sta=3563.28,3750.38
XS Rating Curve= 0 ,0
Exp/Cntr=0.5,0.3

Type RM Length L Ch R = 1 ,16947   ,187,229,196
BEGIN DESCRIPTION:
New section cut to align with US 90 embankment
END DESCRIPTION:
XS GIS Cut Line= 6
 3180378.888015313869984.0662667 3177449.924151713868429.2731537
 3177384.595870313868385.7210754 3177311.894900213868384.0806588
 3177269.537373413868335.4278689 3174522.413297813866837.9163408
#Sta/Elev= 30
  280.72   56.22 2027.41   54.36 2042.36   52.78 2102.14   35.84 2132.04   34.57
 2206.77   36.62 2296.45    34.1 2326.34   35.18 2386.13   51.16 2401.08   52.12
 2640.22   51.78    2984   43.27 3043.78   44.99 3133.46   40.72 3282.93   38.25
 3537.02   39.98 3622.98   36.45 3662.24   32.16 3689.87   25.95 3718.95   24.35
 3773.85   34.59 3786.43   35.55 3857.51   36.55 4022.38   33.95 4082.33   26.94
 4142.27   33.92 4217.11    36.1 4321.89   34.08 5234.96   33.65 6941.35   36.12
#Mann= 7 ,-1 , 0
  280.72     .06       0 2027.41      .1       0 2401.08     .06       0
 3622.98     .04       0 3786.43     .06       0 4022.38     .04       0
 4142.27     .06       0
#XS Ineff= 3 ,-1
  280.72    3668    42.5    3752    4056    39.8    4104 6941.35    36.1
Permanent Ineff=
       F       F       F
Bank Sta=3622.98,3773.85
XS Rating Curve= 0 ,0
Exp/Cntr=0.5,0.3

Type RM Length L Ch R = 2 ,16830   ,,,
BEGIN DESCRIPTION:
US 90 Mainlanes  Both culverts contribute to conveyance
END DESCRIPTION:
Bridge Culvert--1,0,-1,-1, 0
Deck Dist Width WeirC Skew NumUp NumDn MinLoCord MaxHiCord MaxSubmerge Is_Ogee
20,197,2.6,0, 86, 86, , , 0.98, 0, 0,0,,
    1250    2100    2200    2300    2400    2600    2700    2900    3000 3092.93
 3196.13  3295.2 3396.64 3497.21 3596.38 3695.42 3796.58 3796.58 3842.93 3866.56
 3897.84 3897.84 3997.05 4095.16 4192.19 4290.75    4389 4487.16 4487.16 4584.88
 4586.66 4592.93 4679.09 4683.86 4750.71 4784.22 4786.91 4888.34 4989.59 4992.19
 5093.95 5146.97 5196.25 5198.14 5297.79 5398.46 5407.11 5472.24 5505.77 5513.17
 5610.59 5712.67 5715.68 5819.12 5903.23  5905.8 5967.51 5978.58 5992.87 6091.66
  6096.2 6191.74 6289.29 6294.09 6393.59  6399.6 6497.89  6502.9 6511.96 6613.54
 6617.62 6702.33 6716.15 6807.16 6810.12  6830.5 6922.03 7012.35 7036.08 7127.21
 7156.74    7240 7259.47 7342.39 7359.54 7359.99
    54.8   57.05    57.3    57.3    57.3   56.83   55.74   53.16   51.12   50.03
   48.09   46.12   44.66   43.47   42.68   41.94   41.25   41.25   40.95    40.8
    40.6    40.6   39.93   39.17   38.61   38.36   38.27   38.21   38.21   37.97
   37.95   37.88   36.85    36.8   36.53   36.39    36.4   36.36   35.31   35.31
   35.37   34.77   34.26   34.26   34.37   34.61   34.64   34.57   34.52   34.54
   34.43   34.75   34.75   35.05   34.46   34.44   34.58   34.81   35.14   35.85
   35.83   36.62   37.07   37.06   37.12   37.13   37.13   37.14   37.16   36.98
   36.99   36.78   36.79   36.71   36.71   36.65   35.94    36.2   36.15   35.73
   35.85   35.71    35.8   35.99   36.06   36.06
      48      48      48      48      48
                                                                                
                                                                                
                                                                                
                                                                                
                                                                                
                                                                                
                                                                                
                                                
     750    2100    2200    2300    2400    2600    2700    2900    3000 3092.93
 3196.13  3295.2 3396.64 3497.21 3596.38 3695.42 3796.58 3796.58 3842.93 3866.56
 3897.84 3897.84 3997.05 4095.16 4192.19 4290.75    4389 4487.16 4487.16 4584.88
 4586.66 4592.93 4679.09 4683.86 4750.71 4784.22 4786.91 4888.34 4989.59 4992.19
 5093.95 5146.97 5196.25 5198.14 5297.79 5398.46 5407.11 5472.24 5505.77 5513.17
 5610.59 5712.67 5715.68 5819.12 5903.23  5905.8 5967.51 5978.58 5992.87 6091.66
  6096.2 6191.74 6289.29 6294.09 6393.59  6399.6 6497.89  6502.9 6511.96 6613.54
 6617.62 6702.33 6716.15 6807.16 6810.12  6830.5 6922.03 7012.35 7036.08 7127.21
 7156.74    7240 7259.47 7342.39 7359.54 7359.99
   53.36   57.05    57.3    57.3    57.3   56.83   55.74   53.16   51.12   50.03
   48.09   46.12   44.66   43.47   42.68   41.94   41.25   41.25   40.95    40.8
    40.6    40.6   39.93   39.17   38.61   38.36   38.27   38.21   38.21   37.97
   37.95   37.88   36.85    36.8   36.53   36.39    36.4   36.36   35.31   35.31
   35.37   34.77   34.26   34.26   34.37   34.61   34.64   34.57   34.52   34.54
   34.43   34.75   34.75   35.05   34.46   34.44   34.58   34.81   35.14   35.85
   35.83   36.62   37.07   37.06   37.12   37.13   37.13   37.14   37.16   36.98
   36.99   36.78   36.79   36.71   36.71   36.65   35.94    36.2   36.15   35.73
   35.85   35.71    35.8   35.99   36.06   36.06
      48      48
                                                                                
                                                                                
                                                                                
                                                                                
                                                                                
                                                                                
                                                                                
                                                
BR Coef=-1 , 0 , 0 ,, 0 ,,,0.8,-1,,0,
WSPro=,,,, 1 ,,,, 0 ,,,, 0 ,,,,-1 ,-1 ,-1 , 0 , 0 , 0 , 0 , 0
Multiple Barrel Culv=2,12,12,197,0.012,0.2,1,11,2,24.27,24.19, 3,Culvert #1  , 0 ,20
    3694    3313    3710    3329    3726    3345
Culvert Bottom n=0.012
Culvert=2,8,8,222,0.012,0.2,1,11,2,25.47,4080,25.26,3400,Culvert #2  , 0 ,3
Culvert Bottom n=0.012
BC Design=,, 0 ,, 0 ,,,,,,
BC HTab HWMax=56.64
BC Use User HTab Curves=0
BC User HTab FreeFlow(D)= 0

Type RM Length L Ch R = 1 ,16718   ,87,43,57
BEGIN DESCRIPTION:
New section cut to align with US 90 embankment
END DESCRIPTION:
XS GIS Cut Line= 6
 3180258.740384413869753.9781814  3177436.102657 13868198.759179
 3177402.060074213868159.1145733 3177334.573004413868153.9305285
 3176104.401908413867481.7747206 3174929.401352713866816.2253028
#Sta/Elev= 30
       0   53.89  674.52    52.1  749.47   53.36 1603.87   52.29 1633.85   48.36
 1678.82   36.82 1693.81   34.81 1723.79   34.29 1798.73   36.48 1888.67   34.57
 1903.66   35.88 1978.61   51.86 2203.45   46.89 2293.39   48.08 2338.36      46
 2443.28   45.85 2473.26   43.65 2533.22   42.57 2578.19   43.69 2668.12   38.52
 3177.77   37.22  3235.8   36.48 3248.86   34.66 3302.06   25.02 3329.14   24.24
 3402.33   25.22 3461.98   33.27 3581.28   35.27 4610.29   33.79 6094.91   36.49
#Mann= 5 ,-1 , 0
       0     .06       0 1603.87      .1       0 1978.61     .06       0
 3248.86     .04       0 3461.98     .06       0
#XS Ineff= 2 , 0
       0    3297    42.5    3414       0      36
Permanent Ineff=
       F       F
Bank Sta=3248.86,3461.98
XS Rating Curve= 0 ,0
Exp/Cntr=0.5,0.3

Type RM Length L Ch R = 1 ,16675   ,230,106,74
BEGIN DESCRIPTION:
New section cut to align with US 90 embankment
END DESCRIPTION:
XS GIS Cut Line= 6
 3180246.543558513869673.0849705 3179358.997105213869075.4841316
 3177338.036908313868113.3997697 3175761.107975513867243.9418629
 3175083.306837713866745.3139232 3174812.294924813866625.1160764
#Sta/Elev= 30
       0   38.31  668.74   35.18 1323.33   33.99  1740.6      36 1904.53   35.05
 2053.56   36.25 2142.98   34.87 2366.52   34.31 2649.67   35.69 2709.28   34.45
 2947.72   35.77 3111.65   35.38 3168.62   36.84 3222.62   35.98 3276.19   24.98
 3302.29   23.76 3343.07   24.88 3356.94   26.85 3370.81   31.61 3398.55    35.9
 3633.95   34.37 3858.85    34.7 3918.82   33.64 4293.66   33.76 4383.62   34.81
 4728.47   33.96 5679.27   35.08 5767.84   35.87 6167.28   35.31 6256.22   36.14
#Mann= 3 , 0 , 0
       0     .06       0 3222.62     .04       0 3398.55     .06       0
#XS Ineff= 2 , 0
       0    3260    42.5    3346       0    36.1
Permanent Ineff=
       T       T
Bank Sta=3222.62,3398.55
XS Rating Curve= 0 ,0
Exp/Cntr=0.5,0.3

Type RM Length L Ch R = 2 ,16622   ,,,
BEGIN DESCRIPTION:
Eastbound Feeder of US 90
END DESCRIPTION:
Bridge Culvert--1,0,-1,-1, 0
Deck Dist Width WeirC Skew NumUp NumDn MinLoCord MaxHiCord MaxSubmerge Is_Ogee
21,74,2.6,0, 140, 154, , , 0.98, 0, 0,0,,
   25.02      60  140.07     160  243.29     260     360  380.96     460  489.68
     560  582.59     660  665.69  737.62     760  812.31     860  909.32     960
 1006.67    1060 1118.85    1160    1260    1360 1362.73    1460 1499.69    1560
    1660    1760 1782.86 1877.45 1877.45 1877.45 2001.58 2001.58 2189.13 2189.13
 2189.13 2376.17 2376.17 2376.17 2398.63 2511.09 2564.78 2751.98 2751.98 2938.04
 2938.04 3119.72 3119.72 3303.58 3490.04 3676.39 3676.39 3861.24 3893.44 3984.74
 3985.07 3985.19  4037.9 4136.22 4238.56  4417.7 4429.07 4608.25 4608.63 4778.95
 4779.05 4779.06 4792.34 4792.95 4799.84 4873.06 4915.08 4915.38 4915.67 4961.14
 5017.38 5024.08 5024.72 5029.33 5038.72 5103.72 5151.03 5189.99 5191.08 5191.76
 5215.09 5283.33  5345.6 5345.75 5346.27 5357.42 5465.33 5497.07 5498.17 5499.15
 5586.42 5597.68 5606.27 5646.64 5647.23 5688.87 5740.33 5741.24 5770.18 5808.43
 5833.48 5854.37 5903.06    5920 5927.84 5927.98 5964.93 5968.97 5969.16 6027.15
 6093.83 6094.34 6096.61 6119.35 6196.81 6205.28  6271.9  6272.4 6284.85 6336.55
  6421.7  6422.1 6453.34  6552.9 6575.74 6575.88 6590.02 6633.04 6633.48 6649.13
   37.22   37.19   36.95   36.81   36.47   36.26   36.08   36.01   35.61   35.54
   35.33   35.37   35.41   35.39   35.19   35.12      35   34.91   34.83   34.77
    34.6   34.43   34.19   34.04   33.93   34.29   34.31   34.85   35.06   35.41
   35.56   35.35   35.57   35.94   35.94   35.94   36.24   36.24   36.78   36.78
   36.78   36.24   36.24   36.24   36.25    36.3   36.33   36.94   36.94   38.23
   38.23   40.41   40.41   40.24   38.16   36.82   36.82   35.82   35.79    35.7
    35.7    35.7   36.69   36.83   36.99   37.18   37.19   36.47   36.47   36.77
   36.77   36.77   36.79   36.79   36.82   37.13   37.34   37.34   37.34   37.51
   37.81   37.84   37.84   37.85   37.85   37.92   38.01   38.09   38.09   38.09
   38.02   37.83   37.67   37.68   37.68   37.64   37.23   37.12   37.12   37.13
   36.92    36.9   36.88   36.78   36.78   36.84   36.91   36.91   36.95      37
   37.08   37.14   37.29   37.34   37.36   37.36   37.48   37.49   37.49   37.53
   37.59   37.58   37.59   37.61   37.34   37.31   37.08   37.08   37.05   36.92
   36.72   36.72   36.81   37.14   37.22   37.22   37.27   37.46   37.46   37.53
                                                                                
                                                                                
                                                                                
                                                                                
                                                                                
                                                                                
                                                                                
                                                                                
                                                                                
                                                                                
                                                                                
                                                                                
                                                                                
                                                                                
       0   58.38     100     200  261.23     300   312.4     400   437.9     500
  548.63     600  635.71     700  765.02     800  880.07     900  983.29    1000
    1100 1120.96    1200 1229.68    1300 1322.59    1400 1405.69 1477.62    1500
 1552.31    1600 1649.32    1700 1746.67    1800 1858.85    1900    2000    2100
 2102.73    2200 2239.69    2300    2400    2500 2522.86 2617.45 2617.45 2617.45
 2741.58 2741.58 2929.13 2929.13 2929.13 3116.17 3116.17 3116.17 3138.63 3251.09
 3304.78 3491.98 3491.98 3678.04 3678.04 3859.72 3859.72 4043.58 4230.04 4416.39
 4416.39 4601.24 4633.44 4724.74 4725.07 4725.19  4777.9 4876.22 4978.56  5157.7
 5169.07 5348.25 5348.63 5518.95 5519.05 5519.06 5532.34 5532.95 5539.84 5613.06
 5655.08 5655.38 5655.67 5701.14 5757.38 5764.08 5764.72 5769.33 5778.72 5843.72
 5891.03 5929.99 5931.08 5931.76 5955.09 6023.33  6085.6 6085.75 6086.27 6097.42
 6205.33 6237.07 6238.17 6239.15 6326.42 6337.68 6346.27 6386.64 6387.23 6428.87
 6480.33 6481.24 6510.18 6548.43 6573.48 6594.37 6643.06    6660 6667.84 6667.98
 6704.93 6708.97 6709.16 6767.15 6833.83 6834.34 6836.61 6859.35 6936.81 6945.28
  7011.9  7012.4 7024.85 7076.55  7161.7  7162.1 7193.34  7292.9 7315.74 7315.88
 7330.02 7373.04 7373.48 7389.13
   36.98   36.64   36.43    36.4   36.88   36.62   36.66    36.9   37.01   36.83
   36.93   37.04   37.07   37.09   37.22   37.19   36.95   36.81   36.47   36.26
   36.08   36.01   35.61   35.54   35.33   35.37   35.41   35.39   35.19   35.12
      35   34.91   34.83   34.77    34.6   34.43   34.19   34.04   33.93   34.29
   34.31   34.85   35.06   35.41   35.56   35.35   35.57   35.94   35.94   35.94
   36.24   36.24   36.78   36.78   36.78   36.24   36.24   36.24   36.25    36.3
   36.33   36.94   36.94   38.23   38.23   40.41   40.41   40.24   38.16   36.82
   36.82   35.82   35.79    35.7    35.7    35.7   36.69   36.83   36.99   37.18
   37.19   36.47   36.47   36.77   36.77   36.77   36.79   36.79   36.82   37.13
   37.34   37.34   37.34   37.51   37.81   37.84   37.84   37.85   37.85   37.92
   38.01   38.09   38.09   38.09   38.02   37.83   37.67   37.68   37.68   37.64
   37.23   37.12   37.12   37.13   36.92    36.9   36.88   36.78   36.78   36.84
   36.91   36.91   36.95      37   37.08   37.14   37.29   37.34   37.36   37.36
   37.48   37.49   37.49   37.53   37.59   37.58   37.59   37.61   37.34   37.31
   37.08   37.08   37.05   36.92   36.72   36.72   36.81   37.14   37.22   37.22
   37.27   37.46   37.46   37.53
                                                                                
                                                                                
                                                                                
                                                                                
                                                                                
                                                                                
                                                                                
                                                                                
                                                                                
                                                                                
                                                                                
                                                                                
                                                                                
                                                                                
                                                                                
                                
BR Coef=-1 , 0 , 0 ,, 0 ,,,0.8,-1,,0,
WSPro=,,,, 1 ,,,, 0 ,,,, 0 ,,,,-1 ,-1 ,-1 , 0 , 0 , 0 , 0 , 0
Multiple Barrel Culv=2,12,12,74,0.012,0.2,1,11,2,24.67,24.54, 3,Culvert #1  , 0 ,21
    3287    4034    3303    4050    3319    4066
Culvert Bottom n=0.012
BC Design=,, 0 ,, 0 ,,,,,,
BC HTab HWMax=38.31
BC Use User HTab Curves=0
BC User HTab FreeFlow(D)= 0

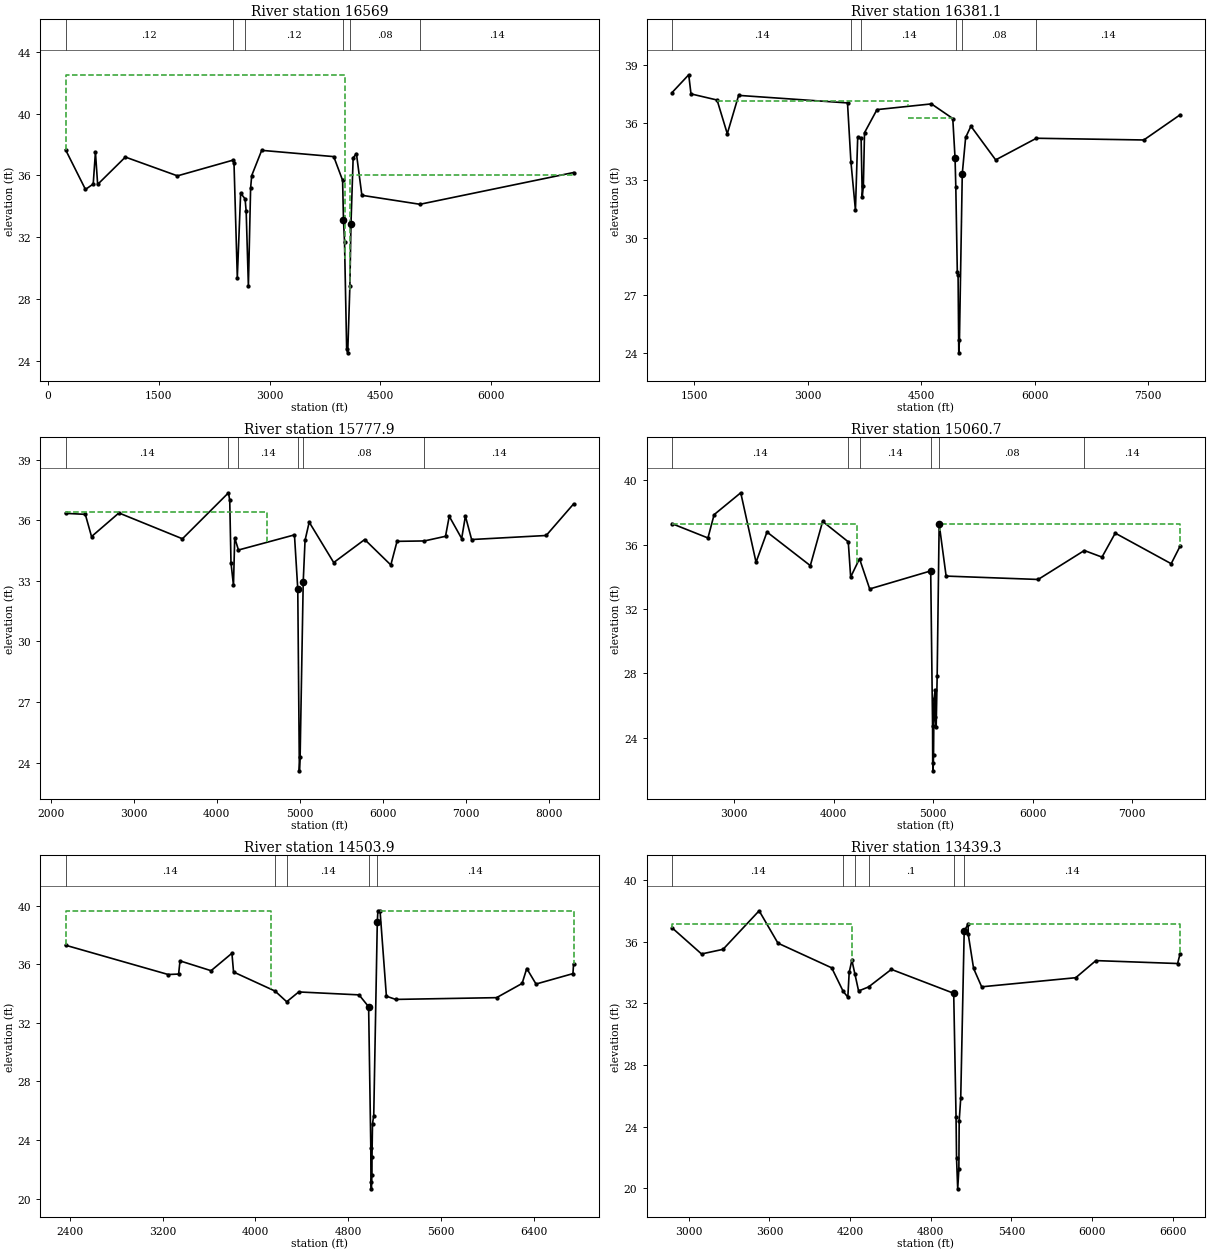
Type RM Length L Ch R = 1 ,16569   ,292,187.9,212
BEGIN DESCRIPTION:
New section cut to align with US 90 embankment
END DESCRIPTION:
XS GIS Cut Line= 6
 3180994.346595813869145.0854113 3177449.037342413868056.1157635
 3177402.430808413868007.9468966 3175746.4833329 13867142.320347
 3175119.822184613866649.8236286  3174728.01644713866481.1725652
#Sta/Elev= 30
  237.58  37.668  507.58    35.1  612.58  35.448  642.58  37.503  672.58  35.423
 1047.58  37.188 1752.58  35.975 2502.58  36.987 2517.58  36.836 2562.58  29.403
 2607.58  34.852 2667.58  34.491 2682.58  33.679 2712.58  28.836 2742.58  35.187
 2757.58  35.995 2892.58  37.622 3867.58  37.217 3987.58  35.685 3999.23   33.15
 4013.38   31.73  4042.3   24.81 4056.75   24.55 4085.97   28.87 4100.72   32.86
 4130.23   37.14  4174.5   37.41 4248.28   34.72 5033.87   34.14  7112.8   36.19
#Mann= 6 ,-1 , 0
  237.58     .12       0 2502.58      .1       0 2667.58     .12       0
 3999.23     .04       0 4085.97     .08       0 5033.87     .14       0
#XS Ineff= 2 , 0
       0    4018    42.5    4084       0      36
Permanent Ineff=
       F       F
#Block Obstruct= 2 , 0
       0                    4200       0   35.45
Bank Sta=3999.23,4100.72
XS Rating Curve= 0 ,0
Exp/Cntr=0.5,0.3

Type RM Length L Ch R = 1 ,16381.1 ,316.6,603.2,71
BEGIN DESCRIPTION:
Cross Section 16381.1-Interpolated - Revised right overbank to align with US 90 embankment
END DESCRIPTION:
XS GIS Cut Line= 6
  3181140.560143 13868276.389929  3179534.279891  13868104.72984
   3178924.01766 13868061.420871  3177599.609876 13867967.429917
  3177262.592177 13867730.284066 3174859.603342613866388.0208683
#Sta/Elev= 30
  1203.1   37.581424.696  38.5131454.696  37.5151799.696  37.1951934.696  35.436
2084.696  37.4383524.696  37.0443569.696  33.9833629.696  31.4453659.696  35.262
3704.696  35.1943719.696  32.1533734.696  32.7023749.696  35.4893914.696  36.695
4634.696  36.993  4917.1   36.23  4947.1   34.17  4957.1   32.68  4977.1    28.2
  4987.1   28.08  4996.4      24  5005.4   24.68  5042.7   33.35  5087.1   35.24
  5157.1   35.83 5484.32   34.07 6022.83    35.2 7443.92   35.11  7922.6   36.42
#Mann= 6 ,-1 , 0
  1203.1     .14       03569.696      .1       03704.696     .14       0
  4957.1     .04       0  5042.7     .08       0 6022.83     .14       0
#XS Ineff= 3 ,-1
    1800  4319.7   37.15 4319.71    4915   36.24  5157.1    7900   35.83
Permanent Ineff=
       F       F       F
#Block Obstruct= 2 , 0
       0                    5200       0   35.36
Bank Sta=4947.1,5042.7
XS Rating Curve= 0 ,0
Exp/Cntr=0.3,0.1

Type RM Length L Ch R = 1 ,15777.9 ,874,717.2,711.2
BEGIN DESCRIPTION:
Cross Section 15777.9 - Revised right overbank to align with US 90 embankment
END DESCRIPTION:
XS GIS Cut Line= 6
  3180739.379843 13867744.030102  3178315.929966 13867778.920124
  3177923.502273 13867716.810012  3177747.790026 13867689.000028
  3177249.008543 13867643.271445 3174993.976681313866308.1111452
#Sta/Elev= 30
    2179  36.3352417.498  36.2872492.498  35.1862822.498  36.355  3587.5  35.077
  4142.5  37.354  4157.5  36.982  4172.5  33.897  4202.5  32.765  4217.5  35.125
  4262.5  34.521  4937.2   35.27  4977.1   32.59  4996.4   23.59  5005.4   24.27
  5042.7   32.94  5064.8      35  5114.8    35.9    5410    33.9 5783.61   35.04
 6098.09   33.78 6172.96   34.95 6502.42   34.97    6757    35.2 6801.92   36.19
 6951.67   35.09  6996.6    36.2 7071.47   35.04 7969.98   35.24 8299.44    36.8
#Mann= 6 ,-1 , 0
    2179     .14       0  4142.5      .1       0  4262.5     .14       0
  4977.1     .04       0  5042.7     .08       0 6502.42     .14       0
#XS Ineff= 2 , 0
       0  4600.8    36.4  5114.8       0    35.9
Permanent Ineff=
       F       F
#Block Obstruct= 2 , 0
       0                    5200       0   34.87
Bank Sta=4977.1,5042.7
XS Rating Curve= 0 ,0
Exp/Cntr=0.3,0.1

Type RM Length L Ch R = 1 ,15060.7 ,384.9,556.8,535.8
BEGIN DESCRIPTION:
Cross Section 15060.7-Interpolated - Revised right overbank to align with US 90 embankment
END DESCRIPTION:
XS GIS Cut Line= 6
  3180568.859843 13866891.350048  3178872.750046 13866869.029883
  3178086.399913 13867006.330133  3177811.800068 13866993.849843
   3176640.81783 13866929.273201 3175637.309575113866338.5810797
#Sta/Elev= 30
  2375.2   37.31 2736.83   36.42 2798.76   37.87 3066.49   39.23 3220.33   34.91
 3330.22   36.79 3765.78    34.7 3889.65   37.45  4147.3   36.18 4171.25   33.99
  4260.2   35.13  4362.6   33.25  4975.8   34.37  4994.6   24.75  4995.9    22.4
  4999.7   21.94  5004.4   22.91  5009.2   26.39  5019.9   26.94  5020.8   25.28
  5030.8   24.66  5040.8   27.85  5060.8   37.29  5130.8   34.05  6055.7   33.84
 6520.08   35.64 6697.57   35.23 6830.65   36.72    7393   34.82 7481.79    35.9
#Mann= 6 ,-1 , 0
  2375.2     .14       0  4147.3      .1       0  4260.2     .14       0
  4975.8     .04       0  5060.8     .08       0 6520.08     .14       0
#XS Ineff= 2 , 0
       0  4233.8   37.29  5070.8       0   37.29
Permanent Ineff=
       F       F
#Block Obstruct= 2 , 0
       0                    5100       0  34.454
Bank Sta=4975.8,5060.8
XS Rating Curve= 0 ,0
Exp/Cntr=0.3,0.1

Type RM Length L Ch R = 1 ,14503.9 ,1189.1,1064.6,1060.3
BEGIN DESCRIPTION:
Cross Section 14503.9
END DESCRIPTION:
XS GIS Cut Line= 4
      3180611.73     13866608.03      3178912.16     13866550.96
      3177942.76     13866439.71      3176239.08     13866428.99
#Sta/Elev= 30
  2362.5   37.29 3247.73   35.29 3337.65   35.32 3349.64   36.22 3617.41   35.55
 3797.26   36.74 3811.25   35.46 4169.01   34.16  4269.5   33.43  4373.2    34.1
  4893.2    33.9  4975.8   33.09  4994.6   23.47  4995.9   21.12  4999.7   20.66
  5004.4   21.63  5004.9   22.83  5009.2   25.11  5019.9   25.66  5050.6   38.88
  5055.7   39.64  5074.2   39.64    5129   33.81    5209   33.59    6079   33.71
    6299   34.68    6339    35.7    6419   34.64  6737.3   35.35  6742.5      36
#Mann= 5 ,-1 , 0
  2362.5     .14       0 4169.01      .1       0  4269.5     .14       0
  4975.8     .04       0  5050.6     .14       0
#XS Ineff= 2 , 0
       0  4130.2   39.64  5074.2       0   39.64
Permanent Ineff=
       F       F
#Block Obstruct= 2 , 0
       0                    5100       0   33.91
Bank Sta=4975.8,5050.6
XS Rating Curve= 0 ,0
Exp/Cntr=0.3,0.1

Type RM Length L Ch R = 1 ,13439.3 ,789.6,794.4,772.5
BEGIN DESCRIPTION:
Cross Section 13439.3
END DESCRIPTION:
XS GIS Cut Line= 6
      3179987.79     13866048.82      3179373.03     13865859.66
      3178610.22     13865374.96      3178220.86     13865374.96
      3177958.39     13865383.03      3176377.38     13865369.89
#Sta/Elev= 30
  2874.5    36.9  3094.5    35.2  3254.5    35.5    3523      38    3663    35.9
    4063    34.3  4148.7   32.77    4183    32.4    4193      34    4213    34.8
  4235.1   33.92    4263    32.8    4337   33.06  4506.7    34.2  4970.7   32.65
  4988.1   24.64  4991.7   21.98  5000.5   19.97    5009   21.24  5011.5   24.39
  5022.9   25.84  5048.7   36.68  5078.3   37.15  5078.7   36.48  5118.7   34.26
  5178.7   33.07  5878.7   33.66  6028.7   34.77  6636.6   34.58  6654.5    35.2
#Mann= 6 ,-1 , 0
  2874.5     .14       0  4148.7      .1       0  4235.1     .14       0
    4337      .1       0  4970.7     .04       0  5048.7     .14       0
#XS Ineff= 2 , 0
       0  4215.3   37.15  5078.3       0   37.15
Permanent Ineff=
       F       F
Bank Sta=4970.7,5048.7
XS Rating Curve= 0 ,0
Exp/Cntr=0.5,0.3

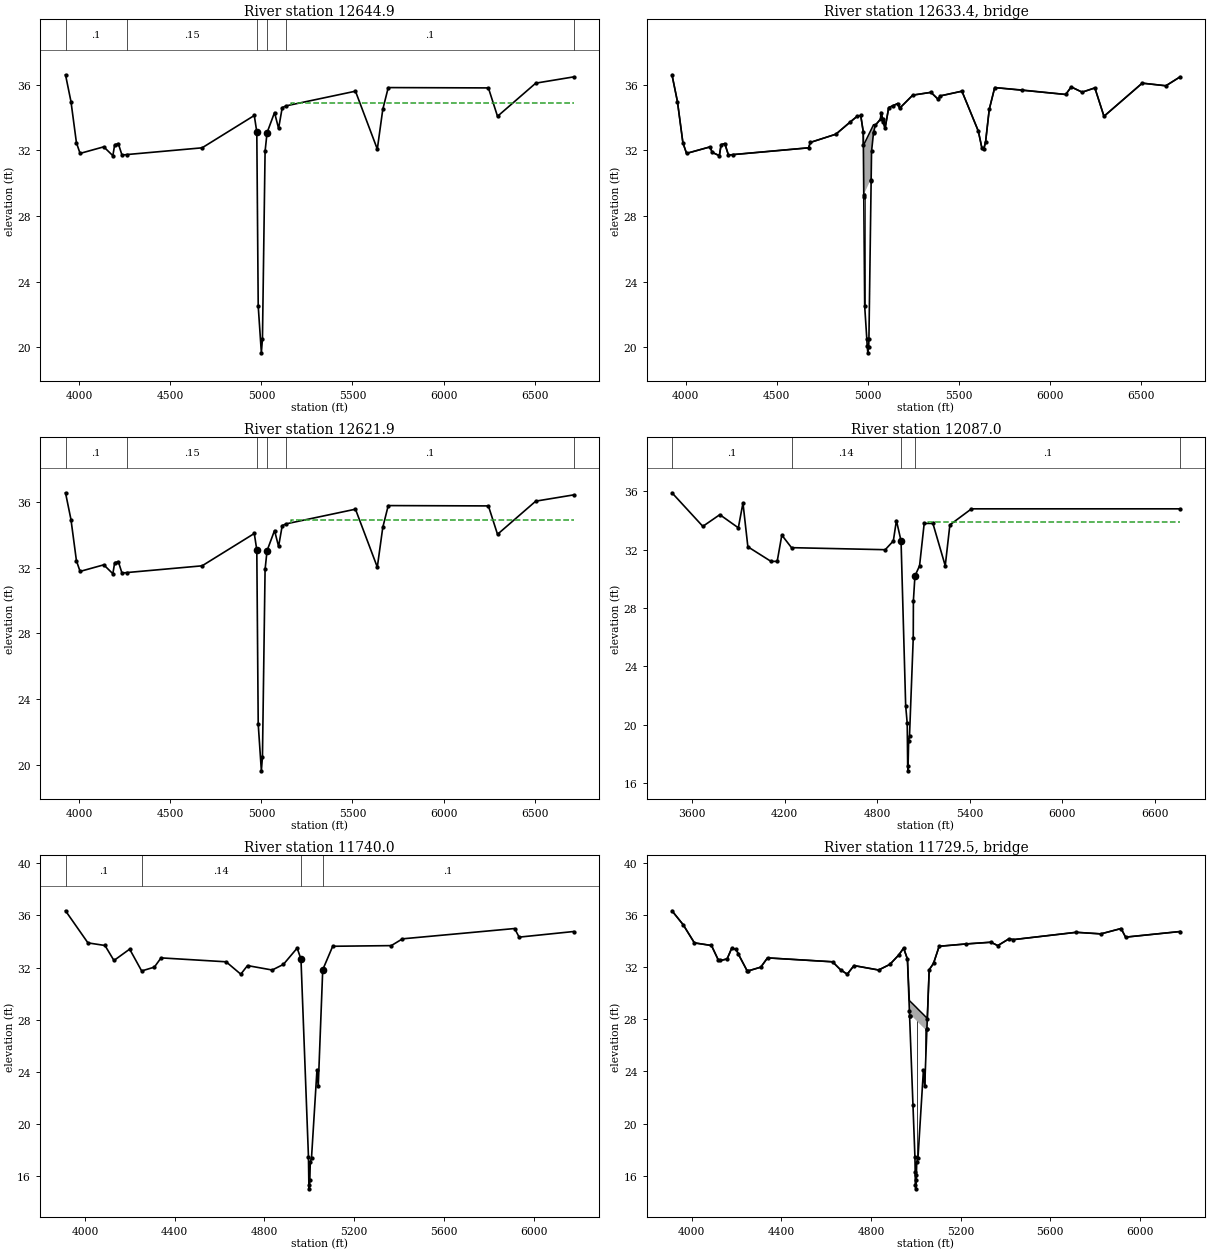
Type RM Length L Ch R = 1 ,12644.9 ,23,23,23
BEGIN DESCRIPTION:
Upstream Section of Bridge/Culvert/Weir
END DESCRIPTION:
XS GIS Cut Line= 6
      3179088.96     13864508.41      3178125.72     13864595.97
      3178037.47     13864596.55      3178018.47      13864595.5
      3177945.42     13864593.19      3176306.31      13864495.5
#Sta/Elev= 30
  3924.4   36.61  3954.4   34.98  3984.4   32.47  4004.4   31.82  4134.4   32.22
  4184.4   31.68  4194.4   32.35  4214.4   32.42  4234.4   31.72  4261.9   31.75
  4674.4   32.16 4960.95   34.13 4974.75   33.13 4982.55   22.52 4999.85   19.67
 5005.85   20.54 5020.25   31.94 5031.05   33.08  5072.1   34.31  5094.4   33.34
  5114.4   34.61    5137   34.72  5516.5   35.61  5636.5   32.08  5666.5    34.5
  5696.5   35.83  6246.5   35.81  6296.5   34.08  6506.5    36.1    6714   36.48
#Mann= 6 , 1 , 0
  3924.4      .1       0  4261.9     .15       0 4974.75     .04       0
 5031.05     .14       0    5137      .1       0    6714      .2       0
#XS Ineff= 2 , 0
       0    4950    32.3  5165.1       0   34.91
Permanent Ineff=
       F       F
Bank Sta=4974.75,5031.05
XS Rating Curve= 0 ,0
Exp/Cntr=0.5,0.3

Type RM Length L Ch R = 3 ,12633.4 ,,,
BEGIN DESCRIPTION:
36" PIPELINE
END DESCRIPTION:
Bridge Culvert--1,0,-1,-1, 0
Deck Dist Width WeirC Skew NumUp NumDn MinLoCord MaxHiCord MaxSubmerge Is_Ogee
10,3,2.6,0, 48, 48, , , 0.95, 0, 1,1,,
  3924.4  3954.4  3984.4  4004.4  4134.4  4144.4  4184.4  4194.4  4214.4  4234.4
  4674.4  4684.4  4824.4 4941.05 4960.95 4974.75 4975.35 4977.56 5017.94 5018.05
 5020.25 5031.05 5040.75 5069.75  5072.1  5094.4  5114.4  5164.4  5174.4  5246.5
  5346.5  5386.5  5396.5  5516.5  5606.5  5626.5  5636.5  5646.5  5666.5  5696.5
  6086.5  6116.5  6176.5  6246.5  6296.5  6506.5  6636.5    6714
   36.61   34.98   32.47   31.82   32.22   31.89   31.68   32.35   32.42   31.72
   32.16   32.49   32.99   34.08   34.13   33.13   32.32   32.35   33.27   33.27
   33.32   33.57   33.53   33.91   34.31   33.34   34.61   34.86   34.57   35.37
   35.54   35.11   35.32   35.61   33.18   32.13   32.08   32.53    34.5   35.83
   35.41   35.87   35.55   35.81   34.08    36.1   35.94   36.48
   36.61   34.98   32.47   31.82   32.22   31.89   31.68   32.35   32.42   31.72
   32.16   32.49   32.99   34.08   34.13   33.13   32.31   29.31   30.27    30.2
   31.94   33.08   33.53   33.91   34.31   33.34   34.61   34.86   34.57   35.37
   35.54   35.11   35.32   35.61   33.18   32.13   32.08   32.53    34.5   35.83
   35.41   35.87   35.55   35.81   34.08    36.1   35.94   36.48
  3924.4  3954.4  3984.4  4004.4  4134.4  4144.4  4184.4  4194.4  4214.4  4234.4
  4674.4  4684.4  4824.4 4941.05 4960.95 4974.75 4975.35 4977.56 5017.94 5018.05
 5020.25 5031.05 5040.75 5069.75  5072.1  5094.4  5114.4  5164.4  5174.4  5246.5
  5346.5  5386.5  5396.5  5516.5  5606.5  5626.5  5636.5  5646.5  5666.5  5696.5
  6086.5  6116.5  6176.5  6246.5  6296.5  6506.5  6636.5    6714
   36.61   34.98   32.47   31.82   32.22   31.89   31.68   32.35   32.42   31.72
   32.16   32.49   32.99   34.08   34.13   33.13   32.32   32.35   33.27   33.27
   33.32   33.57   33.53   33.91   34.31   33.34   34.61   34.86   34.57   35.37
   35.54   35.11   35.32   35.61   33.18   32.13   32.08   32.53    34.5   35.83
   35.41   35.87   35.55   35.81   34.08    36.1   35.94   36.48
   36.61   34.98   32.47   31.82   32.22   31.89   31.68   32.35   32.42   31.72
   32.16   32.49   32.99   34.08   34.13   33.13   32.31   29.31   30.27    30.2
   31.94   33.08   33.53   33.91   34.31   33.34   34.61   34.86   34.57   35.37
   35.54   35.11   35.32   35.61   33.18   32.13   32.08   32.53    34.5   35.83
   35.41   35.87   35.55   35.81   34.08    36.1   35.94   36.48
Pier Skew, UpSta & Num, DnSta & Num=  ,4982.6, 2 ,4982.6, 2 , 0 , 0 , 0 ,,
     1.5     1.5
   21.39   30.48
     1.5     1.5
   21.39   30.48
BR Coef= 1 , 1 , 0 ,1.25, 0 ,,,0.8,0,2,0,
WSPro=,,,, 1 ,,,, 0 ,,,, 0 ,,,,-1 ,-1 ,-1 , 0 , 0 , 0 , 0 , 0
BR U #Sta/Elev= 62
  3924.4   36.61  3954.4   34.98  3984.4   32.47  4004.4   31.82  4134.4   32.22
  4144.4   31.89  4184.4   31.68  4194.4   32.35  4214.4   32.42  4234.4   31.72
  4261.9   31.75  4674.4   32.16  4684.4   32.49  4824.4   32.99  4904.4   33.75
 4941.05   34.08 4960.95   34.13 4974.75   33.13 4975.35   32.31 4977.56   29.31
 4977.65   29.19 4982.55   22.52 4994.15   20.53 4996.55   20.06 4999.85   19.67
 5004.55   20.01 5005.85   20.54 5017.94   30.11 5018.05    30.2 5020.25   31.94
 5031.05   33.08 5031.95   33.12 5040.75   33.53 5069.75   33.91  5072.1   34.31
  5082.1   33.92  5084.4   33.73  5094.4   33.34  5114.4   34.61    5137   34.72
  5164.4   34.86  5174.4   34.57  5246.5   35.37  5346.5   35.54  5386.5   35.11
  5396.5   35.32  5516.5   35.61  5606.5   33.18  5626.5   32.13  5636.5   32.08
  5646.5   32.53  5666.5    34.5  5696.5   35.83  5846.5   35.68  6086.5   35.41
  6116.5   35.87  6176.5   35.55  6246.5   35.81  6296.5   34.08  6506.5    36.1
  6636.5   35.94    6714   36.48
BR U #Mann= 6
  3924.4      .1  4261.9     .15 4974.75     .04 5031.05     .14    5137      .1
    6714      .2
BR U Banks=4974.75,5031.05
BR D #Sta/Elev= 62
  3924.4   36.61  3954.4   34.98  3984.4   32.47  4004.4   31.82  4134.4   32.22
  4144.4   31.89  4184.4   31.68  4194.4   32.35  4214.4   32.42  4234.4   31.72
  4261.9   31.75  4674.4   32.16  4684.4   32.49  4824.4   32.99  4904.4   33.75
 4941.05   34.08 4960.95   34.13 4974.75   33.13 4975.35   32.31 4977.56   29.31
 4977.65   29.19 4982.55   22.52 4994.15   20.53 4996.55   20.06 4999.85   19.67
 5004.55   20.01 5005.85   20.54 5017.94   30.11 5018.05    30.2 5020.25   31.94
 5031.05   33.08 5031.95   33.12 5040.75   33.53 5069.75   33.91  5072.1   34.31
  5082.1   33.92  5084.4   33.73  5094.4   33.34  5114.4   34.61    5137   34.72
  5164.4   34.86  5174.4   34.57  5246.5   35.37  5346.5   35.54  5386.5   35.11
  5396.5   35.32  5516.5   35.61  5606.5   33.18  5626.5   32.13  5636.5   32.08
  5646.5   32.53  5666.5    34.5  5696.5   35.83  5846.5   35.68  6086.5   35.41
  6116.5   35.87  6176.5   35.55  6246.5   35.81  6296.5   34.08  6506.5    36.1
  6636.5   35.94    6714   36.48
BR D #Mann= 6
  3924.4      .1  4261.9     .15 4974.75     .04 5031.05     .14    5137      .1
    6714      .2
BR D Banks=4974.75,5031.05
BC Design=,, 0 ,, 0 ,,,,,,
BC HTab HWMax=36.61
BC Use User HTab Curves=0
BC User HTab FreeFlow(D)= 0

Type RM Length L Ch R = 1 ,12621.9 ,534.9,534.9,534.9
BEGIN DESCRIPTION:
Downstream Section of Bridge/Culvert/Weir
END DESCRIPTION:
XS GIS Cut Line= 6
      3179080.49     13864487.02      3178117.24     13864574.59
      3178028.99     13864575.17      3178009.99     13864574.12
      3177936.94     13864571.81      3176297.84     13864474.12
#Sta/Elev= 30
  3924.4   36.56  3954.4   34.93  3984.4   32.42  4004.4   31.77  4134.4   32.17
  4184.4   31.63  4194.4    32.3  4214.4   32.37  4234.4   31.67  4261.9    31.7
  4674.4   32.11 4960.95   34.08 4974.75   33.08 4982.55   22.47 4999.85   19.62
 5005.85   20.49 5020.25   31.89 5031.05   33.03  5072.1   34.26  5094.4   33.29
  5114.4   34.56    5137   34.67  5516.5   35.56  5636.5   32.03  5666.5   34.45
  5696.5   35.78  6246.5   35.76  6296.5   34.03  6506.5   36.05    6714   36.43
#Mann= 6 , 1 , 0
  3924.4      .1       0  4261.9     .15       0 4974.75     .04       0
 5031.05     .14       0    5137      .1       0    6714      .2       0
#XS Ineff= 2 , 0
       0    4950    32.3  5165.1       0   34.91
Permanent Ineff=
       F       F
Bank Sta=4974.75,5031.05
XS Rating Curve= 0 ,0
Exp/Cntr=0.5,0.3

Type RM Length L Ch R = 1 ,12087.0 ,318.5,347,316.9
BEGIN DESCRIPTION:
Cross Section 12087.0-Interpolated
END DESCRIPTION:
XS GIS Cut Line= 6
        3179552.     13864151.67      3179090.47     13864133.57
      3178122.18     13864043.08      3177895.95     13864034.03
      3177543.02     13864006.88      3176303.25      13863699.2
#Sta/Elev= 30
  3470.6    35.9  3670.6    33.6  3780.6    34.4  3900.6    33.5  3930.6    35.2
  3962.4    32.2  4112.4    31.2  4152.4    31.2  4182.4      33  4245.2   32.14
  4852.4      32    4905    32.6    4925      34    4955    32.6    4985    21.3
    4995    20.1 4997.95   17.17 4999.75   16.85 5004.25    18.9 5009.85   19.25
 5034.05   25.96    5035    28.5    5045    30.2    5075    30.9    5105    33.8
  5161.4    33.8  5241.4    30.9  5271.4    33.7  5411.4    34.8  6762.7    34.8
#Mann= 5 , 1 , 0
  3470.6      .1       0  4245.2     .14       0    4955     .04       0
    5045      .1       0  6762.7      .2       0
#XS Ineff= 2 , 0
       0    4925      34  5131.4       0    33.9
Permanent Ineff=
       F       F
Bank Sta=4955,5045
XS Rating Curve= 0 ,0
Exp/Cntr=0.5,0.3

Type RM Length L Ch R = 1 ,11740.0 ,21,21,21
BEGIN DESCRIPTION:
Upstream Section of Bridge/Culvert/Weir
END DESCRIPTION:
XS GIS Cut Line= 6
      3179133.88     13863673.72      3179108.54     13863672.91
      3178105.16     13863697.75      3177813.96      13863688.3
      3177117.24     13863555.85      3176891.22     13863489.37
#Sta/Elev= 30
  3912.9   36.36  4012.9    33.9  4088.9    33.7  4128.9   32.55  4198.9   33.42
  4252.4   31.75  4308.9   32.04  4338.9   32.75  4628.9   32.45  4694.4    31.5
  4724.4   32.16  4834.4   31.82  4884.4   32.25 4945.75    33.5 4962.75   32.66
 4996.15    17.5 4997.95   15.37 4999.75   15.05 5002.15   15.69 5004.25    17.1
 5009.85   17.45 5034.05   24.16 5039.75    22.9 5059.75   31.84 5104.25   33.64
  5365.4   33.69  5415.4   34.21  5915.4      35  5935.4   34.34  6178.1   34.77
#Mann= 4 , 1 , 0
  3912.9      .1       0  4252.4     .14       0 4962.75     .04       0
 5059.75      .1       0
#XS Ineff= 2 , 0
       0 4945.75   33.45  5050.8       0    27.8
Permanent Ineff=
       F       F
Bank Sta=4962.75,5059.75
XS Rating Curve= 0 ,0
Exp/Cntr=0.5,0.3

Type RM Length L Ch R = 3 ,11729.5 ,,,
BEGIN DESCRIPTION:
12" PIPELINE
END DESCRIPTION:
Bridge Culvert--1,0,-1,-1, 0
Deck Dist Width WeirC Skew NumUp NumDn MinLoCord MaxHiCord MaxSubmerge Is_Ogee
10,1,2.6,0, 53, 53, , , 0.95, 0, 1,1,,
  3912.9  3962.9  4012.9  4088.9  4118.9  4128.9  4158.9  4178.9  4198.9  4208.9
  4248.9  4252.4  4308.9  4338.9  4628.9  4664.4  4694.4  4724.4  4834.4  4884.4
 4924.45 4945.75 4962.75 4971.45 4972.36 4972.45 4987.45 4996.15 4997.35 4997.95
 4999.75 5002.15 5002.65 5004.25 5009.85 5034.05 5039.75 5049.54 5049.65 5051.35
 5059.75 5079.05 5104.25  5225.4  5335.4  5365.4  5415.4  5435.4  5715.4  5825.4
  5915.4  5935.4  6178.1
   36.31   35.24   33.85   33.65   32.56    32.5   32.62   33.43   33.37   32.99
   31.68    31.7   31.99    32.7    32.4   31.79   31.45   32.11   31.77    32.2
   32.93   33.45   32.61   29.43   29.41   29.41   29.16   29.01   28.99   28.98
   28.95   28.91    28.9   28.87   28.77   28.36   28.26   28.09   28.09   28.06
   31.79   32.28   33.59   33.77    33.9   33.64   34.16    34.1   34.66   34.54
   34.95   34.29   34.72
   36.31   35.24   33.85   33.65   32.56    32.5   32.62   33.43   33.37   32.99
   31.68    31.7   31.99    32.7    32.4   31.79   31.45   32.11   31.77    32.2
   32.93   33.45   32.61   28.66   28.25   28.41   28.16   28.01   27.99   27.98
   27.95   27.91    27.9   27.87   27.77   27.36   27.26   27.23   27.28   28.04
   31.79   32.28   33.59   33.77    33.9   33.64   34.16    34.1   34.66   34.54
   34.95   34.29   34.72
  3912.9  3962.9  4012.9  4088.9  4118.9  4128.9  4158.9  4178.9  4198.9  4208.9
  4248.9  4252.4  4308.9  4338.9  4628.9  4664.4  4694.4  4724.4  4834.4  4884.4
 4924.45 4945.75 4962.75 4971.45 4972.36 4972.45 4987.45 4996.15 4997.35 4997.95
 4999.75 5002.15 5002.65 5004.25 5009.85 5034.05 5039.75 5049.54 5049.65 5051.35
 5059.75 5079.05 5104.25  5225.4  5335.4  5365.4  5415.4  5435.4  5715.4  5825.4
  5915.4  5935.4  6178.1
   36.31   35.24   33.85   33.65   32.56    32.5   32.62   33.43   33.37   32.99
   31.68    31.7   31.99    32.7    32.4   31.79   31.45   32.11   31.77    32.2
   32.93   33.45   32.61   29.43   29.41   29.41   29.16   29.01   28.99   28.98
   28.95   28.91    28.9   28.87   28.77   28.36   28.26   28.09   28.09   28.06
   31.79   32.28   33.59   33.77    33.9   33.64   34.16    34.1   34.66   34.54
   34.95   34.29   34.72
   36.31   35.24   33.85   33.65   32.56    32.5   32.62   33.43   33.37   32.99
   31.68    31.7   31.99    32.7    32.4   31.79   31.45   32.11   31.77    32.2
   32.93   33.45   32.61   28.66   28.25   28.41   28.16   28.01   27.99   27.98
   27.95   27.91    27.9   27.87   27.77   27.36   27.26   27.23   27.28   28.04
   31.79   32.28   33.59   33.77    33.9   33.64   34.16    34.1   34.66   34.54
   34.95   34.29   34.72
Pier Skew, UpSta & Num, DnSta & Num=  ,5006.6, 2 ,5006.6, 2 , 0 , 0 , 0 ,,
       1       1
   16.16   28.84
       1       1
   16.16   28.84
Pier Skew, UpSta & Num, DnSta & Num=  ,5039.8, 2 ,5039.8, 2 , 0 , 0 , 0 ,,
       1       1
   21.96   28.27
       1       1
   21.96   28.27
BR Coef= 1 , 1 , 0 ,1.25, 0 ,,,0.8,0,2,0,
WSPro=,,,, 1 ,,,, 0 ,,,, 0 ,,,,-1 ,-1 ,-1 , 0 , 0 , 0 , 0 , 0
BR U #Sta/Elev= 53
  3912.9   36.31  3962.9   35.24  4012.9   33.85  4088.9   33.65  4118.9   32.56
  4128.9    32.5  4158.9   32.62  4178.9   33.43  4198.9   33.37  4208.9   32.99
  4248.9   31.68  4252.4    31.7  4308.9   31.99  4338.9    32.7  4628.9    32.4
  4664.4   31.79  4694.4   31.45  4724.4   32.11  4834.4   31.77  4884.4    32.2
 4924.45   32.93 4945.75   33.45 4962.75   32.61 4971.45   28.66 4972.36   28.25
 4972.45   28.21 4987.45    21.4 4996.15   17.45 4997.35   16.31 4997.95   15.32
 4999.75      15 5002.15   15.64 5002.65   16.06 5004.25   17.05 5009.85    17.4
 5034.05   24.11 5039.75   22.85 5049.54   27.23 5049.65   27.28 5051.35   28.04
 5059.75   31.79 5079.05   32.28 5104.25   33.59  5225.4   33.77  5335.4    33.9
  5365.4   33.64  5415.4   34.16  5435.4    34.1  5715.4   34.66  5825.4   34.54
  5915.4   34.95  5935.4   34.29  6178.1   34.72
BR U #Mann= 4
  3912.9      .1  4252.4     .14 4962.75    .055 5059.75      .1
BR U Banks=4962.75,5059.75
BR D #Sta/Elev= 53
  3912.9   36.31  3962.9   35.24  4012.9   33.85  4088.9   33.65  4118.9   32.56
  4128.9    32.5  4158.9   32.62  4178.9   33.43  4198.9   33.37  4208.9   32.99
  4248.9   31.68  4252.4    31.7  4308.9   31.99  4338.9    32.7  4628.9    32.4
  4664.4   31.79  4694.4   31.45  4724.4   32.11  4834.4   31.77  4884.4    32.2
 4924.45   32.93 4945.75   33.45 4962.75   32.61 4971.45   28.66 4972.36   28.25
 4972.45   28.21 4987.45    21.4 4996.15   17.45 4997.35   16.31 4997.95   15.32
 4999.75      15 5002.15   15.64 5002.65   16.06 5004.25   17.05 5009.85    17.4
 5034.05   24.11 5039.75   22.85 5049.54   27.23 5049.65   27.28 5051.35   28.04
 5059.75   31.79 5079.05   32.28 5104.25   33.59  5225.4   33.77  5335.4    33.9
  5365.4   33.64  5415.4   34.16  5435.4    34.1  5715.4   34.66  5825.4   34.54
  5915.4   34.95  5935.4   34.29  6178.1   34.72
BR D #Mann= 4
  3912.9      .1  4252.4     .14 4962.75    .055 5059.75      .1
BR D Banks=4962.75,5059.75
BC Design=,, 0 ,, 0 ,,,,,,
BC HTab HWMax=36.36
BC Use User HTab Curves=0
BC User HTab FreeFlow(D)= 0