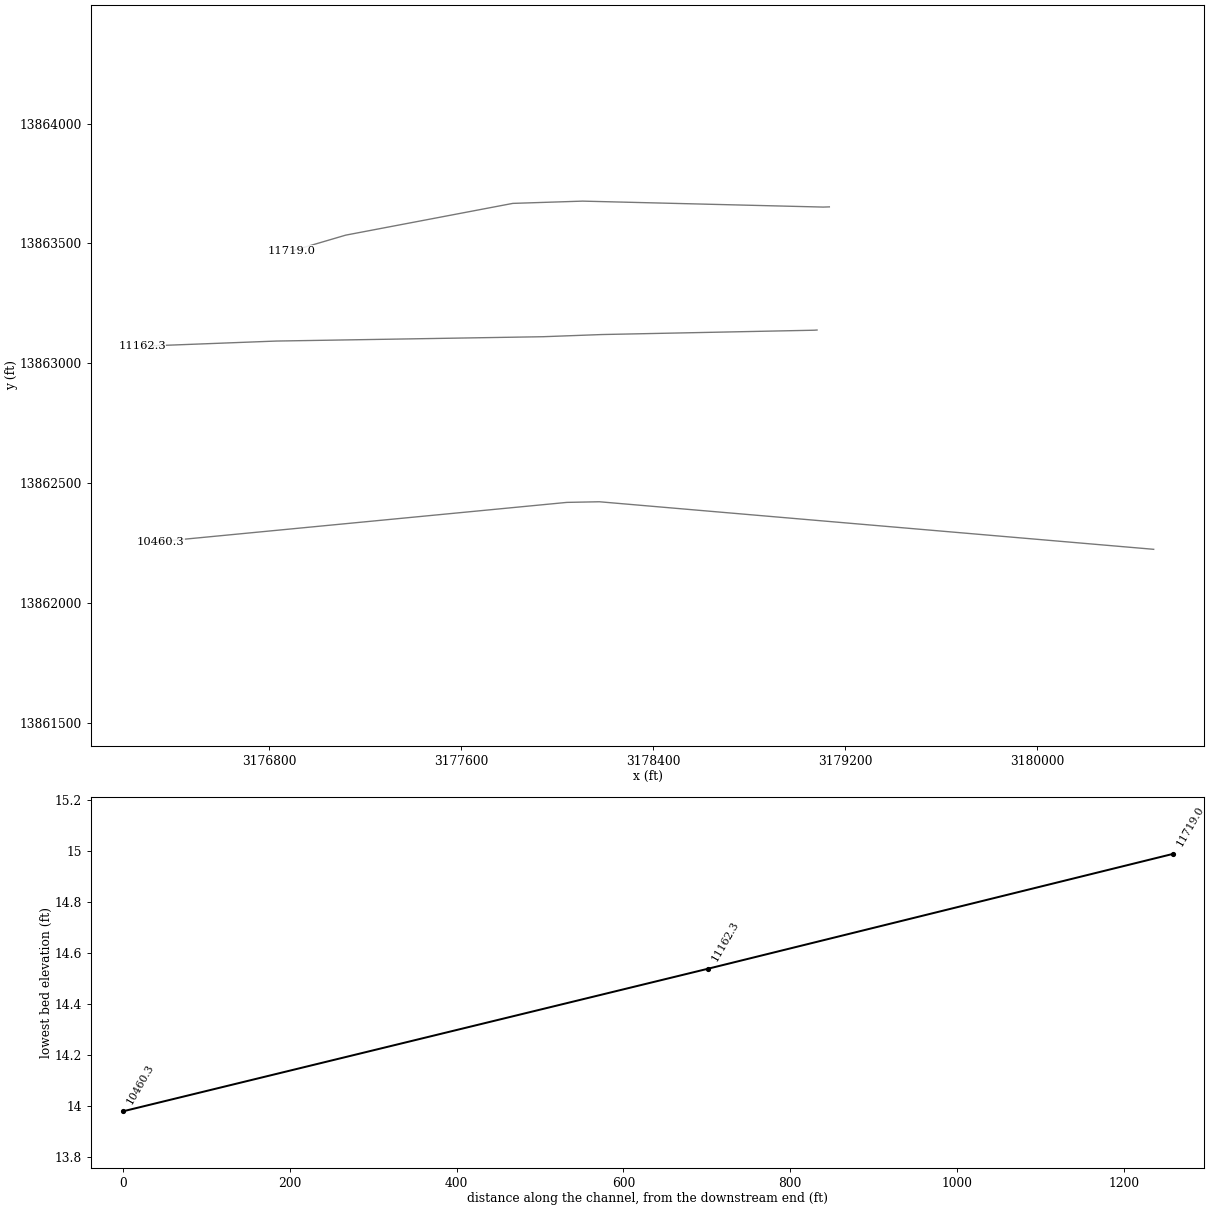
HEC-RAS study P107-00-00.prj: P107-00-00

--- P107-00-00.g01 (geometry) --- (continued)

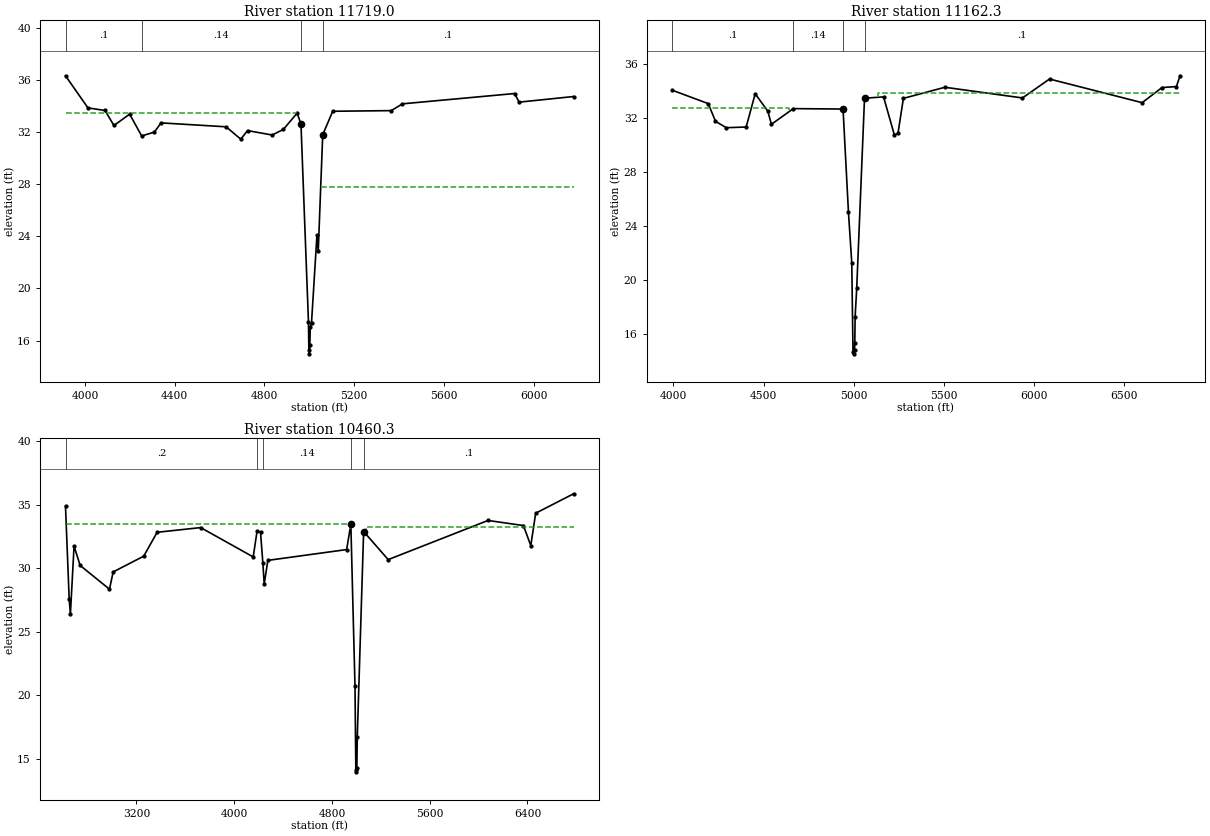
Type RM Length L Ch R = 1 ,11719.0 ,556.7,556.7,556.7
BEGIN DESCRIPTION:
Downstream Section of Bridge/Culvert/Weir
END DESCRIPTION:
XS GIS Cut Line= 6
      3179134.81     13863652.74      3179109.46     13863651.93
      3178106.08     13863676.77      3177814.88     13863667.32
      3177118.16     13863534.87      3176892.15      13863468.4
#Sta/Elev= 30
  3912.9    36.3  4012.9   33.84  4088.9   33.64  4128.9   32.49  4198.9   33.36
  4252.4   31.69  4308.9   31.98  4338.9   32.69  4628.9   32.39  4694.4   31.44
  4724.4    32.1  4834.4   31.76  4884.4   32.19 4945.75   33.44 4962.75    32.6
 4996.15   17.44 4997.95   15.31 4999.75   14.99 5002.15   15.63 5004.25   17.04
 5009.85   17.39 5034.05    24.1 5039.75   22.84 5059.75   31.78 5104.25   33.58
  5365.4   33.63  5415.4   34.15  5915.4   34.94  5935.4   34.28  6178.1   34.71
#Mann= 4 , 1 , 0
  3912.9      .1       0  4252.4     .14       0 4962.75     .04       0
 5059.75      .1       0
#XS Ineff= 2 , 0
       0 4945.75   33.45  5050.8       0    27.8
Permanent Ineff=
       F       F
Bank Sta=4962.75,5059.75
XS Rating Curve= 0 ,0
Exp/Cntr=0.5,0.3

Type RM Length L Ch R = 1 ,11162.3 ,661.3,702,660.4
BEGIN DESCRIPTION:
Cross Section 11162.3-Interpolated
END DESCRIPTION:
XS GIS Cut Line= 6
      3179083.52     13863138.94      3179072.37     13863138.13
      3178185.53     13863120.04       3177941.2     13863110.99
      3176828.12     13863092.89      3176268.56     13863071.37
#Sta/Elev= 30
    3992   34.05  4193.2   33.05  4233.2   31.74  4293.2   31.27  4403.2   31.32
  4453.2   33.78  4523.2   32.49  4543.2   31.52  4664.6   32.68  4940.2   32.65
  4970.2   25.01 4988.52   21.28 4995.42   14.65 4999.12   14.54 5003.72   14.82
 5005.32   15.35 5007.12   17.26 5015.92   19.38 5059.22   33.45  5164.7   33.55
  5224.7   30.73  5244.7   30.85  5274.7   33.44  5504.7   34.26  5934.7   33.47
  6084.7   34.87  6597.9   33.12  6707.9   34.24  6787.9   34.31  6807.9   35.11
#Mann= 4 , 1 , 0
    3992      .1       0  4664.6     .14       0  4940.2     .05       0
 5059.22      .1       0
#XS Ineff= 2 , 0
       0  4643.2    32.7  5134.7       0   33.81
Permanent Ineff=
       F       F
Bank Sta=4940.2,5059.22
XS Rating Curve= 0 ,0
Exp/Cntr=0.5,0.3

Type RM Length L Ch R = 1 ,10460.3 ,22,22,22
BEGIN DESCRIPTION:
Upstream Section of Bridge/Culvert/Weir
END DESCRIPTION:
XS GIS Cut Line= 4
      3180487.35     13862223.87      3178175.75     13862422.32
      3178040.24     13862419.66      3176345.62     13862256.49
#Sta/Elev= 30
  2619.2   34.86  2649.2    27.6  2659.2   26.39  2689.2   31.74  2739.2   30.22
  2979.2   28.35  3009.2   29.71  3259.2   30.95  3369.2   32.83  3725.5    33.2
  4155.5   30.89    4187   32.92  4215.5   32.83  4234.5   30.39  4245.5   28.77
  4275.5   30.62  4920.2   31.47 4954.52   33.47 4988.52   20.72 4995.42   14.09
 4999.12   13.98 5003.72   14.26 5007.12    16.7 5059.22   32.89  5260.2   30.68
  6077.3   33.76  6367.3   33.36  6427.3   31.78  6467.3   34.33  6777.3   35.86
#Mann= 5 , 1 , 0
  2619.2      .2       0    4187      .1       0  4234.5     .14       0
 4954.52     .05       0 5059.22      .1       0
#XS Ineff= 2 , 0
       0 4945.92   33.45 5076.32       0   33.25
Permanent Ineff=
       F       F
Bank Sta=4954.52,5059.22
XS Rating Curve= 0 ,0
Exp/Cntr=0.5,0.3