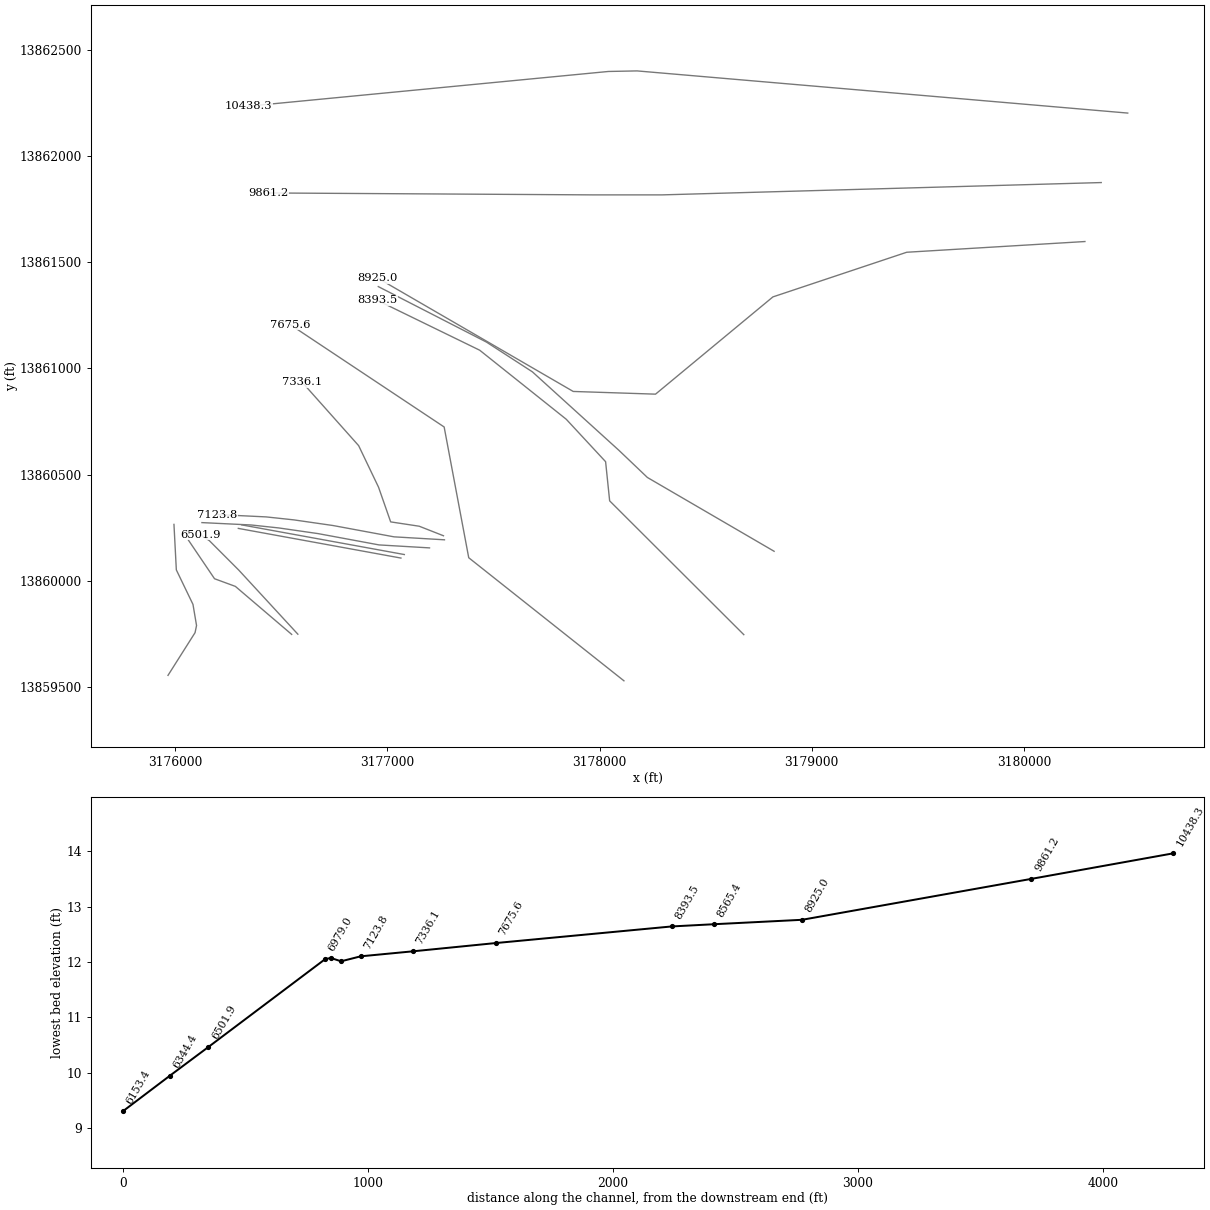
HEC-RAS study P107-00-00.prj: P107-00-00

--- P107-00-00.g01 (geometry) --- (continued)

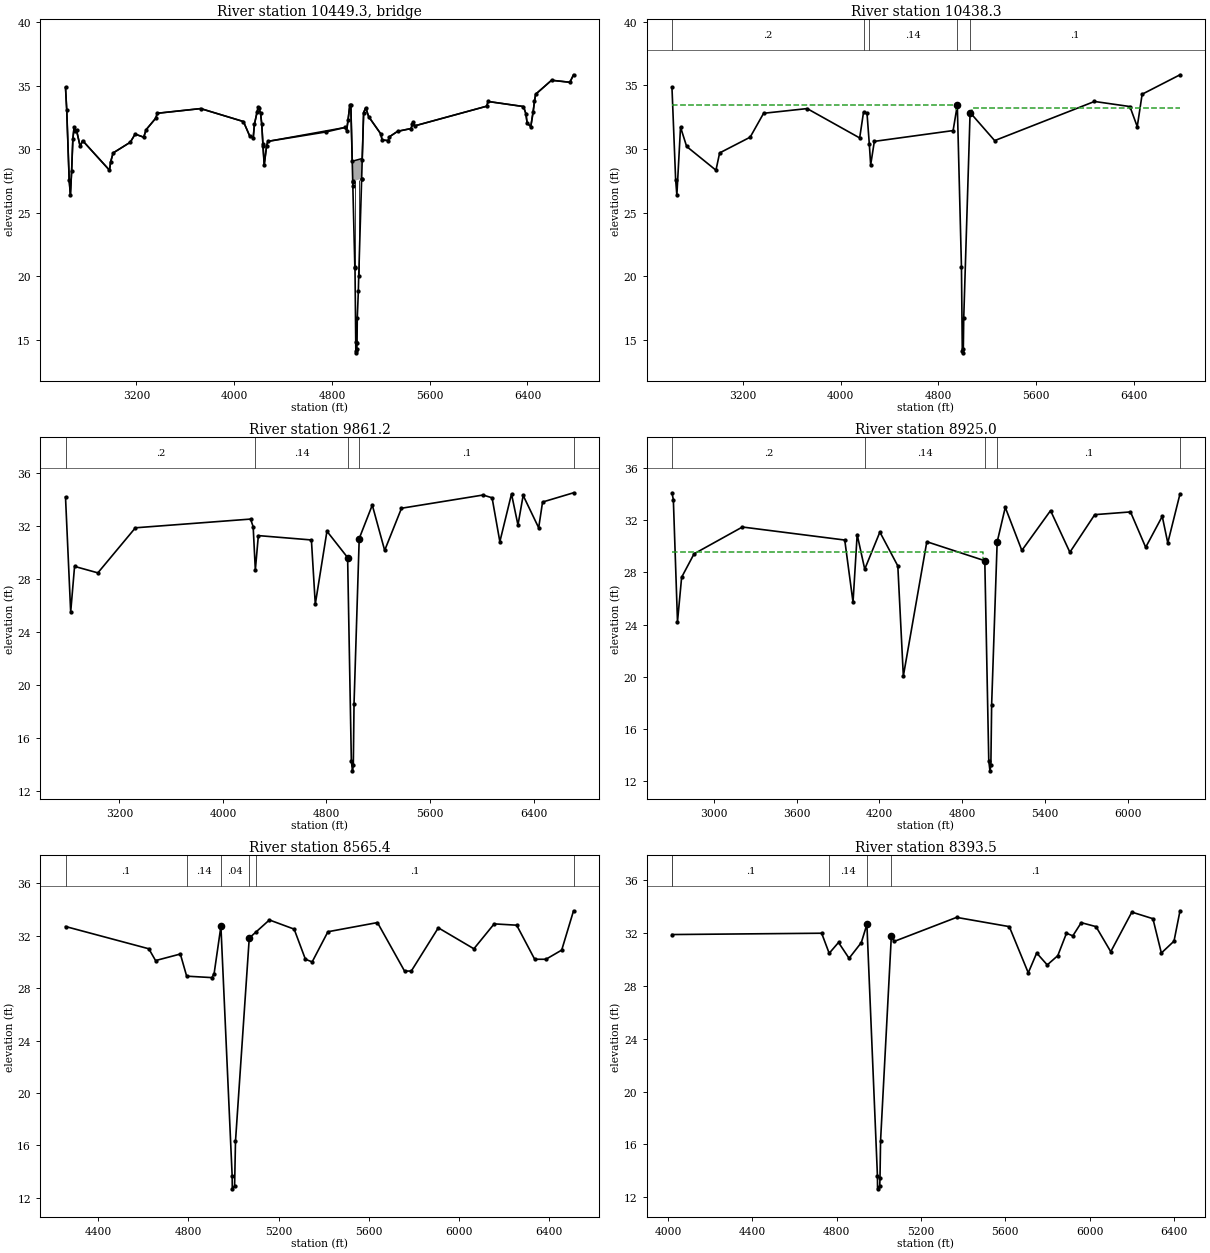
Type RM Length L Ch R = 3 ,10449.3 ,,,
BEGIN DESCRIPTION:
18" PIPELINE
END DESCRIPTION:
Bridge Culvert--1,0,-1,-1, 0
Deck Dist Width WeirC Skew NumUp NumDn MinLoCord MaxHiCord MaxSubmerge Is_Ogee
10,2,2.6,0, 60, 60, , , 0.95, 0, 1,1,,
  2619.2  2629.2  2649.2  2659.2  2669.2  2679.2  2689.2  2699.2  2709.2  2739.2
  2759.2  2979.2  2989.2  3009.2  3149.2  3189.2  3259.2  3279.2  3359.2  3369.2
  3725.5  4075.5  4125.5  4155.5  4165.5  4195.5  4215.5  4225.5  4245.5  4265.5
  4275.5  4910.2  4920.2 4945.92 4954.52 4965.92 4969.93 5042.92 5047.62 5059.22
 5076.32 5100.72  5200.2  5210.2  5260.2  5270.2  5337.3  5447.3  5467.3  5477.3
  6067.3  6077.3  6367.3  6387.3  6397.3  6427.3  6467.3  6597.3  6747.3  6777.3
   34.85   33.09   27.59   26.38   28.25   30.76   31.73   31.45   31.49   30.21
   30.67   28.34   29.02    29.7   30.54   31.18   30.94   31.53   32.45   32.82
   33.19   32.17   31.06   30.88   31.96   33.28   32.82   31.96   28.76   30.28
   30.61   31.71   31.46   33.45   33.46   29.06   29.06   29.25   29.26   32.88
   33.25   32.55   31.19   30.72   30.67   30.97    31.4   31.62    32.1   31.83
   33.38   33.75   33.35   32.79   32.05   31.77   34.32   35.42   35.26   35.85
   34.85   33.09   27.59   26.38   28.25   30.76   31.73   31.45   31.49   30.21
   30.67   28.34   29.02    29.7   30.54   31.18   30.94   31.53   32.45   32.82
   33.19   32.17   31.06   30.88   31.96   33.28   32.82   31.96   28.76   30.28
   30.61   31.71   31.46   33.45   33.46   29.03   27.47   27.66   29.16   32.88
   33.25   32.55   31.19   30.72   30.67   30.97    31.4   31.62    32.1   31.83
   33.38   33.75   33.35   32.79   32.05   31.77   34.32   35.42   35.26   35.85
  2619.2  2629.2  2649.2  2659.2  2669.2  2679.2  2689.2  2699.2  2709.2  2739.2
  2759.2  2979.2  2989.2  3009.2  3149.2  3189.2  3259.2  3279.2  3359.2  3369.2
  3725.5  4075.5  4125.5  4155.5  4165.5  4195.5  4215.5  4225.5  4245.5  4265.5
  4275.5  4910.2  4920.2 4945.92 4954.52 4965.92 4969.93 5042.92 5047.62 5059.22
 5076.32 5100.72  5200.2  5210.2  5260.2  5270.2  5337.3  5447.3  5467.3  5477.3
  6067.3  6077.3  6367.3  6387.3  6397.3  6427.3  6467.3  6597.3  6747.3  6777.3
   34.85   33.09   27.59   26.38   28.25   30.76   31.73   31.45   31.49   30.21
   30.67   28.34   29.02    29.7   30.54   31.18   30.94   31.53   32.45   32.82
   33.19   32.17   31.06   30.88   31.96   33.28   32.82   31.96   28.76   30.28
   30.61   31.71   31.46   33.45   33.46   29.06   29.06   29.25   29.26   32.88
   33.25   32.55   31.19   30.72   30.67   30.97    31.4   31.62    32.1   31.83
   33.38   33.75   33.35   32.79   32.05   31.77   34.32   35.42   35.26   35.85
   34.85   33.09   27.59   26.38   28.25   30.76   31.73   31.45   31.49   30.21
   30.67   28.34   29.02    29.7   30.54   31.18   30.94   31.53   32.45   32.82
   33.19   32.17   31.06   30.88   31.96   33.28   32.82   31.96   28.76   30.28
   30.61   31.71   31.46   33.45   33.46   29.03   27.47   27.66   29.16   32.88
   33.25   32.55   31.19   30.72   30.67   30.97    31.4   31.62    32.1   31.83
   33.38   33.75   33.35   32.79   32.05   31.77   34.32   35.42   35.26   35.85
Pier Skew, UpSta & Num, DnSta & Num=  ,4988.5, 2 ,4988.5, 2 , 0 , 0 , 0 ,,
       1       1
   19.23   28.61
       1       1
   19.23   28.61
Pier Skew, UpSta & Num, DnSta & Num=  ,5019, 2 ,5019, 2 , 0 , 0 , 0 ,,
       1       1
   18.81   28.69
       1       1
   18.81   28.69
BR Coef= 1 , 1 , 0 ,1.25, 0 ,,,0.8,0,2,0,
WSPro=,,,, 1 ,,,, 0 ,,,, 0 ,,,,-1 ,-1 ,-1 , 0 , 0 , 0 , 0 , 0
BR U #Sta/Elev= 82
  2619.2   34.85  2629.2   33.09  2649.2   27.59  2659.2   26.38  2669.2   28.25
  2679.2   30.76  2689.2   31.73  2699.2   31.45  2709.2   31.49  2739.2   30.21
  2759.2   30.67  2979.2   28.34  2989.2   29.02  3009.2    29.7  3149.2   30.54
  3189.2   31.18  3259.2   30.94  3279.2   31.53  3359.2   32.45  3369.2   32.82
  3725.5   33.19  4075.5   32.17  4125.5   31.06  4155.5   30.88  4165.5   31.96
    4187   32.91  4195.5   33.28  4205.5    33.2  4215.5   32.82  4225.5   31.96
  4234.5   30.38  4235.5   30.21  4245.5   28.76  4265.5   30.28  4275.5   30.61
  4750.2   31.35  4910.2   31.71  4920.2   31.46 4932.52    32.3 4945.92   33.45
 4954.52   33.46 4965.92   29.03 4969.93   27.47 4970.02   27.44 4970.92   27.09
 4987.52   20.64 4988.52   20.71 4994.62   14.83 4995.42   14.08 4999.12   13.97
 5003.72   14.25 5005.32   14.78 5007.12   16.69 5015.92   18.81 5019.02      20
 5042.81   27.62 5042.92   27.66 5047.62   29.16 5059.22   32.88 5076.32   33.25
 5100.72   32.55  5200.2   31.19  5210.2   30.72  5260.2   30.67  5270.2   30.97
  5337.3    31.4  5447.3   31.62  5457.3   31.98  5467.3    32.1  5477.3   31.83
  6067.3   33.38  6077.3   33.75  6367.3   33.35  6387.3   32.79  6397.3   32.05
  6427.3   31.77  6447.3   32.94  6457.3    33.8  6467.3   34.32  6597.3   35.42
  6747.3   35.26  6777.3   35.85
BR U #Mann= 5
  2619.2      .2    4187      .1  4234.5     .14 4954.52    .055 5059.22      .1
BR U Banks=4954.52,5059.22
BR D #Sta/Elev= 82
  2619.2   34.85  2629.2   33.09  2649.2   27.59  2659.2   26.38  2669.2   28.25
  2679.2   30.76  2689.2   31.73  2699.2   31.45  2709.2   31.49  2739.2   30.21
  2759.2   30.67  2979.2   28.34  2989.2   29.02  3009.2    29.7  3149.2   30.54
  3189.2   31.18  3259.2   30.94  3279.2   31.53  3359.2   32.45  3369.2   32.82
  3725.5   33.19  4075.5   32.17  4125.5   31.06  4155.5   30.88  4165.5   31.96
    4187   32.91  4195.5   33.28  4205.5    33.2  4215.5   32.82  4225.5   31.96
  4234.5   30.38  4235.5   30.21  4245.5   28.76  4265.5   30.28  4275.5   30.61
  4750.2   31.35  4910.2   31.71  4920.2   31.46 4932.52    32.3 4945.92   33.45
 4954.52   33.46 4965.92   29.03 4969.93   27.47 4970.02   27.44 4970.92   27.09
 4987.52   20.64 4988.52   20.71 4994.62   14.83 4995.42   14.08 4999.12   13.97
 5003.72   14.25 5005.32   14.78 5007.12   16.69 5015.92   18.81 5019.02      20
 5042.81   27.62 5042.92   27.66 5047.62   29.16 5059.22   32.88 5076.32   33.25
 5100.72   32.55  5200.2   31.19  5210.2   30.72  5260.2   30.67  5270.2   30.97
  5337.3    31.4  5447.3   31.62  5457.3   31.98  5467.3    32.1  5477.3   31.83
  6067.3   33.38  6077.3   33.75  6367.3   33.35  6387.3   32.79  6397.3   32.05
  6427.3   31.77  6447.3   32.94  6457.3    33.8  6467.3   34.32  6597.3   35.42
  6747.3   35.26  6777.3   35.85
BR D #Mann= 5
  2619.2      .2    4187      .1  4234.5     .14 4954.52    .055 5059.22      .1
BR D Banks=4954.52,5059.22
BC Design=,, 0 ,, 0 ,,,,,,
BC HTab HWMax=35.86
BC Use User HTab Curves=0
BC User HTab FreeFlow(D)= 0

Type RM Length L Ch R = 1 ,10438.3 ,577.1,577.1,577.1
BEGIN DESCRIPTION:
Downstream Section of Bridge/Culvert/Weir
END DESCRIPTION:
XS GIS Cut Line= 4
      3180488.57     13862201.91      3178176.97     13862400.36
      3178041.46      13862397.7      3176346.84     13862234.52
#Sta/Elev= 30
  2619.2   34.84  2649.2   27.58  2659.2   26.37  2689.2   31.72  2739.2    30.2
  2979.2   28.33  3009.2   29.69  3259.2   30.93  3369.2   32.81  3725.5   33.18
  4155.5   30.87    4187    32.9  4215.5   32.81  4234.5   30.37  4245.5   28.75
  4275.5    30.6  4920.2   31.45 4954.52   33.45 4988.52    20.7 4995.42   14.07
 4999.12   13.96 5003.72   14.24 5007.12   16.68 5059.22   32.87  5260.2   30.66
  6077.3   33.74  6367.3   33.34  6427.3   31.76  6467.3   34.31  6777.3   35.84
#Mann= 5 , 1 , 0
  2619.2      .2       0    4187      .1       0  4234.5     .14       0
 4954.52     .05       0 5059.22      .1       0
#XS Ineff= 2 , 0
       0 4945.92   33.45 5076.32       0   33.25
Permanent Ineff=
       F       F
Bank Sta=4954.52,5059.22
XS Rating Curve= 0 ,0
Exp/Cntr=0.5,0.3

Type RM Length L Ch R = 1 ,9861.2  ,924.8,936.2,936
BEGIN DESCRIPTION:
Cross Section 9861.2-Interpolated
END DESCRIPTION:
XS GIS Cut Line= 4
      3180363.66     13861874.93      3178294.12     13861816.92
      3177968.34     13861816.92      3176438.99     13861825.97
#Sta/Elev= 30
  2783.5   34.22  2823.5   25.51  2853.5   28.97  3033.5   28.48  3323.5   31.89
  4213.5   32.55  4233.5   31.97  4250.3    28.7  4273.5    31.3  4683.5   30.97
  4713.5   26.11  4803.5   31.63  4963.3   29.64  4992.1   14.27  5000.7    13.5
  5007.3   13.92  5012.9   18.59  5052.9   31.08  5153.9   33.61  5249.6   30.18
  5379.6   33.37  6009.6   34.37  6079.6   34.16  6139.6   30.84  6229.6   34.45
  6279.6    32.1  6319.6   34.34  6439.6   31.89  6469.6   33.84    6709   34.54
#Mann= 5 , 1 , 0
  2783.5      .2       0  4250.3     .14       0  4963.3     .05       0
  5052.9      .1       0    6709      .2       0
#XS Ineff= 2 , 0
       0  4803.5   31.63               0
Permanent Ineff=
       F       F
Bank Sta=4963.3,5052.9
XS Rating Curve= 0 ,0
Exp/Cntr=0.3,0.1

Type RM Length L Ch R = 1 ,8925.0  ,440.7,359.6,311.8
BEGIN DESCRIPTION:
Cross Section 8925.0
END DESCRIPTION:
XS GIS Cut Line= 6
      3180286.78     13861597.38      3179447.11     13861546.92
      3178816.81     13861336.82      3178263.77     13860879.14
      3177876.01     13860891.85      3176954.28     13861425.82
#Sta/Elev= 30
  2697.8   34.12  2707.8   33.59  2737.8   24.22  2767.8   27.63  2857.8   29.43
  3207.8   31.49    3949   30.49    4009   25.71    4039   30.91  4093.8   28.25
  4203.4    31.1  4333.4    28.5  4373.4   20.04  4543.4   30.36  4963.3    28.9
  4992.1   13.53  5000.7   12.76  5007.3   13.18  5012.9   17.85  5052.9   30.34
  5111.6      33  5231.6   29.69  5439.5   32.75  5579.5   29.55  5759.5   32.44
  6018.5   32.65  6128.5   29.93  6248.5   32.31  6288.5   30.27  6377.1   34.04
#Mann= 5 , 1 , 0
  2697.8      .2       0  4093.8     .14       0  4963.3     .04       0
  5052.9      .1       0  6377.1      .2       0
#XS Ineff= 2 , 0
       0    4949   29.57               0
Permanent Ineff=
       F       F
Bank Sta=4963.3,5052.9
XS Rating Curve= 0 ,0
Exp/Cntr=0.3,0.1

Type RM Length L Ch R = 1 ,8565.4  ,208.9,171.9,119.5
BEGIN DESCRIPTION:
Cross Section 8565.4-Interpolated
END DESCRIPTION:
XS GIS Cut Line= 6
      3178822.46     13860139.67      3178225.37     13860487.07
      3178091.59     13860614.48      3177683.86     13860983.98
      3177467.26     13861124.14       3176957.6     13861385.34
#Sta/Elev= 30
  4253.8    32.7  4623.8      31  4653.8    30.1  4763.8    30.6  4791.9   28.91
  4903.8    28.8  4913.8    29.1    4944   32.71    4994   13.65  4994.5   12.68
  5004.8    12.9  5008.8   16.32  5069.9   31.82  5098.5   32.26  5159.3    33.2
  5269.3    32.5  5319.3    30.2  5349.3      30  5419.3    32.3  5639.3      33
  5759.6    29.3  5789.6    29.3  5909.6    32.6  6067.6      31  6157.6    32.9
  6257.6    32.8  6337.6    30.2  6387.6    30.2  6457.6    30.9  6510.2    33.9
#Mann= 6 , 1 , 0
  4253.8      .1       0  4791.9     .14       0    4944     .04       0
  5069.9     .14       0  5098.5      .1       0  6510.2      .2       0
Bank Sta=4944,5069.9
XS Rating Curve= 0 ,0
Exp/Cntr=0.3,0.1

Type RM Length L Ch R = 1 ,8393.5  ,707.6,717.9,724.8
BEGIN DESCRIPTION:
Cross Section 8393.5
END DESCRIPTION:
XS GIS Cut Line= 6
      3178679.63     13859747.32      3178047.64     13860376.95
      3178028.57      13860561.3      3177843.13     13860761.01
      3177435.41     13861085.91      3176951.23     13861321.63
#Sta/Elev= 30
  4019.4    31.9  4729.4      32  4765.1   30.48  4809.4    31.3  4859.4    30.1
  4917.5   31.29    4944   32.67    4994   13.61  4994.5   12.64  5004.8   12.86
  5006.1   13.43  5008.8   16.28  5059.9   31.78  5073.5   31.38  5369.4    33.2
  5619.4    32.5  5709.4      29  5749.4    30.5  5799.4    29.6  5849.4    30.3
  5890.7      32  5920.7    31.8  5960.7    32.8  6030.7    32.5  6100.7    30.6
  6200.7    33.6  6300.7    33.1  6340.7    30.5  6400.7    31.4  6429.2    33.7
#Mann= 5 , 1 , 0
  4019.4      .2       0  4019.4      .1       0  4765.1     .14       0
    4944     .04       0  5059.9      .1       0
Bank Sta=4944,5059.9
XS Rating Curve= 0 ,0
Exp/Cntr=0.3,0.1

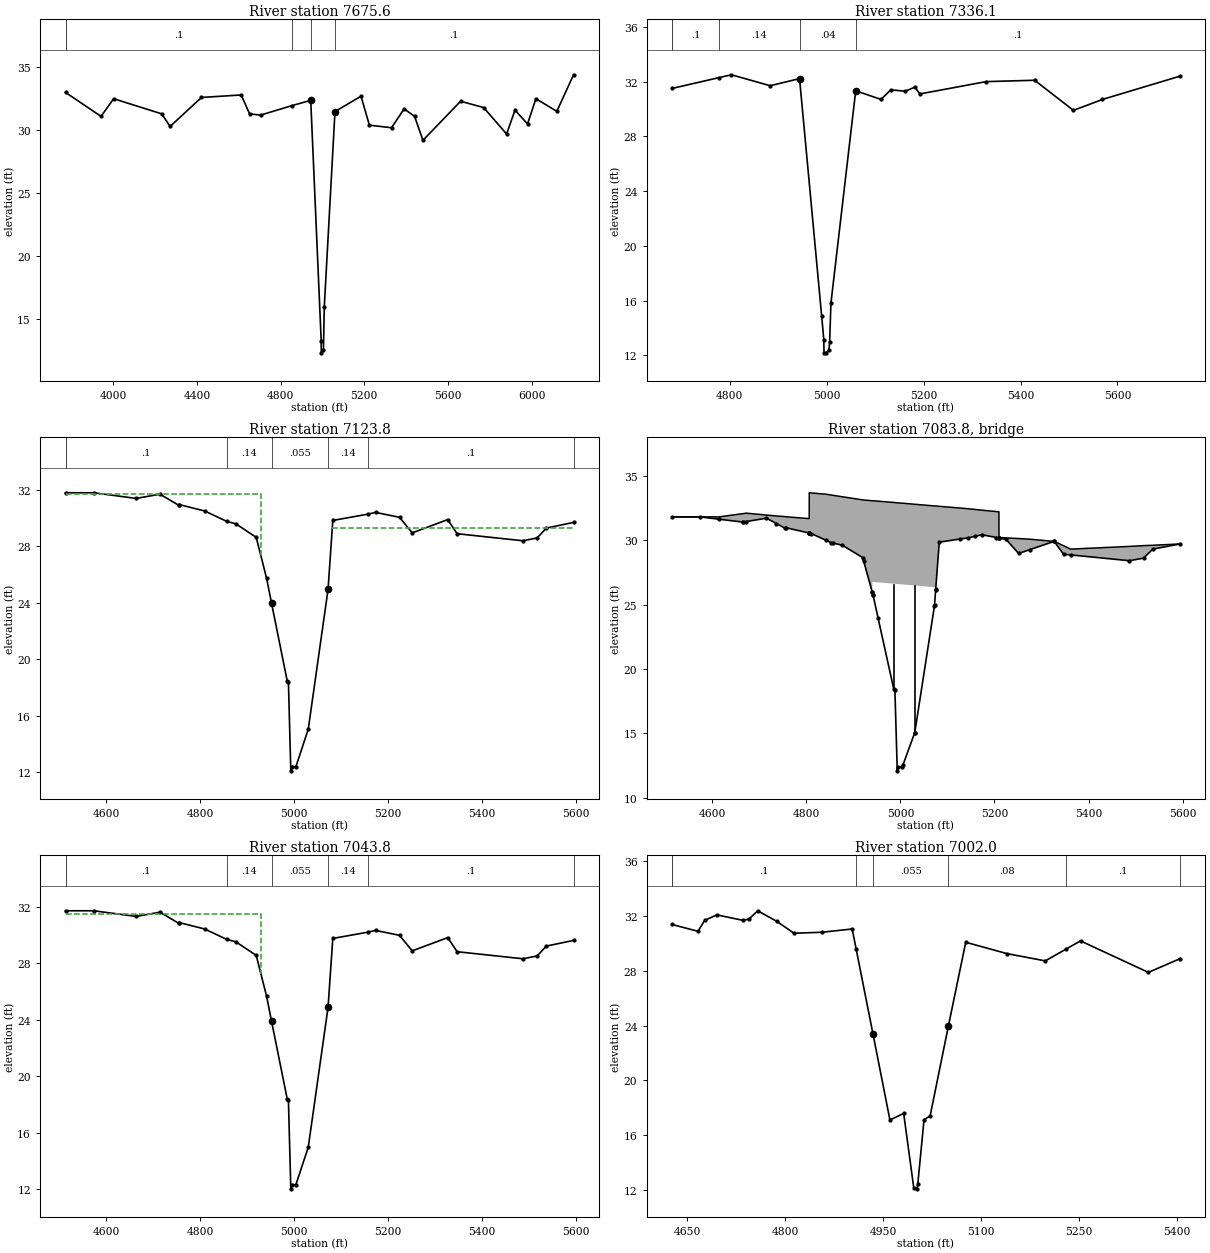
Type RM Length L Ch R = 1 ,7675.6  ,335.3,339.5,352.2
BEGIN DESCRIPTION:
Cross Section 7675.6-Interpolated
END DESCRIPTION:
XS GIS Cut Line= 4
      3178114.94     13859530.13      3177383.75     13860109.29
      3177267.92     13860724.65       3176543.2     13861205.95
#Sta/Elev= 30
  3771.6      33  3941.6    31.1  4001.6    32.5  4231.6    31.3  4271.6    30.3
  4421.6    32.6  4611.6    32.8  4651.6    31.3  4704.4    31.2  4853.2   31.95
    4944   32.37    4994   13.31  4994.5   12.34  5004.8   12.56  5008.8   15.98
  5059.9   31.48  5184.4    32.7  5224.4    30.4  5330.5    30.2  5390.5    31.7
  5440.5    31.1  5480.5    29.2  5660.5    32.3  5770.5    31.8  5880.5    29.7
  5920.5    31.6  5980.5    30.5  6020.5    32.5  6120.5    31.5  6200.5    34.4
#Mann= 5 , 1 , 0
  3771.6      .2       0  3771.6      .1       0  4853.2     .14       0
    4944    .055       0  5059.9      .1       0
Bank Sta=4944,5059.9
XS Rating Curve= 0 ,0
Exp/Cntr=0.3,0.1

Type RM Length L Ch R = 1 ,7336.1  ,93.9,212.3,309.5
BEGIN DESCRIPTION:
Cross Section 7336.1-Interpolated
END DESCRIPTION:
XS GIS Cut Line= 6
      3177264.67     13860212.75      3177150.51     13860257.59
      3177015.96     13860277.98      3176958.88     13860441.07
       3176865.1     13860636.78      3176598.86      13860935.3
#Sta/Elev= 23
  4680.7    31.5  4777.4   32.29  4803.4    32.5  4883.4    31.7    4944   32.22
  4989.6   14.89    4994   13.16  4994.5   12.19  4999.5   12.19  5004.8   12.41
  5006.1   12.98  5008.8   15.83  5059.9   31.33  5112.2    30.7  5132.2    31.4
  5162.2    31.3  5182.2    31.6  5192.2    31.1  5329.2      32  5429.2    32.1
  5509.2    29.9  5569.2    30.7  5729.2    32.4
#Mann= 5 , 1 , 0
  4680.7      .2       0  4680.7      .1       0  4777.4     .14       0
    4944     .04       0  5059.9      .1       0
Bank Sta=4944,5059.9
XS Rating Curve= 0 ,0
Exp/Cntr=0.5,0.3

Type RM Length L Ch R = 1 ,7123.8  ,80,80,80
BEGIN DESCRIPTION:
Upstream Section of Bridge/Culvert/Weir
END DESCRIPTION:
XS GIS Cut Line= 6
      3177269.41     13860193.67      3177031.45     13860207.67
      3176744.51     13860260.86      3176559.74     13860287.46
      3176429.57     13860301.45      3176197.21     13860312.65
#Sta/Elev= 30
  4514.1    31.8  4574.3    31.8  4664.3    31.4  4715.1    31.7  4754.5   30.92
 4756.26   30.96 4810.11   30.51  4857.2   29.77 4876.52    29.6 4919.72   28.64
 4941.78   25.74 4952.35   23.97 4985.75   18.45  4988.2   18.38 4993.26    12.1
 4994.79    12.4 5004.06   12.39 5030.41   15.05 5072.46   24.95 5082.57   29.84
  5158.1   30.29 5173.65   30.41 5224.44   30.06 5251.48   28.96    5327    29.9
    5347    28.9    5487    28.4    5517    28.6  5536.9    29.3  5594.6    29.7
#Mann= 7 , 1 , 0
  4514.1      .2       0  4514.1      .1       0  4857.2     .14       0
 4952.35    .055       0 5072.46     .14       0  5158.1      .1       0
  5594.6      .2       0
#XS Ineff= 2 , 0
       0    4930    31.7  5081.4       0    29.3
Permanent Ineff=
       F       F
Bank Sta=4952.35,5072.46
XS Rating Curve= 0 ,0
Exp/Cntr=0.5,0.3

Type RM Length L Ch R = 3 ,7083.8  ,,,
BEGIN DESCRIPTION:
WALLISVILLE ROAD, SKEW ANGLE OF 40 DEGREES
Structure ID: P07-4
END DESCRIPTION:
Bridge Culvert--1,0,-1,-1, 0
Deck Dist Width WeirC Skew NumUp NumDn MinLoCord MaxHiCord MaxSubmerge Is_Ogee
10,60,2.6,0, 58, 58, , , 0.95, 0, 1,1,,
  4514.1  4574.3  4614.1  4664.3  4665.1  4672.3  4715.1  4736.4  4754.5 4756.26
  4804.5 4805.99  4806.1 4806.21 4810.11  4841.3 4852.09  4857.2 4876.52 4919.72
  4921.9 4940.09 4940.18 4941.68 4941.78 4952.35 4985.75  4988.2 4993.26 4994.79
 5004.06 5005.29 5030.33 5030.41 5072.36 5072.46 5074.96 5075.07 5082.57  5126.2
 5143.78  5158.1 5173.65  5204.3 5209.39  5209.5 5209.61 5224.44 5251.48  5275.3
  5326.9    5327    5347    5362    5487    5517  5536.9  5594.6
    31.8    31.8    31.8   32.05   32.05   32.09   31.94   31.87   31.82   31.81
   31.67   31.67   33.67   33.67   33.66   33.56    33.5   33.47   33.36   33.12
   33.11   33.05   33.05   33.05   33.05   33.02   32.92   32.91   32.89   32.89
   32.86   32.86   32.78   32.78   32.65   32.65   32.65   32.65   32.62   32.49
   32.43   32.38   32.32   32.21    32.2    32.2    30.2   30.17   30.12   30.07
    29.9    29.9   29.56    29.3   29.51   29.57    29.6    29.7
    31.8    31.8   31.62    31.4    31.4   31.44    31.7   31.28   30.92   30.96
   30.56   30.54   30.54   30.54   30.51   29.99   29.81   29.77    29.6   28.64
   28.35   25.96   26.75   26.75   26.75   26.72   26.62   26.61   26.59   26.59
   26.56   26.56   26.48   26.48   26.35   26.35   26.35   26.21   29.84   30.08
   30.17   30.29   30.41    30.2   30.16   30.16   30.16   30.06   28.96   29.26
    29.9    29.9    28.9   28.85    28.4    28.6    29.3    29.7
  4514.1  4574.3  4614.1  4664.3  4665.1  4672.3  4715.1  4736.4  4754.5 4756.26
  4804.5 4805.99  4806.1 4806.21 4810.11  4841.3 4852.09  4857.2 4876.52 4919.72
  4921.9 4940.09 4940.18 4941.68 4941.78 4952.35 4985.75  4988.2 4993.26 4994.79
 5004.06 5005.29 5030.33 5030.41 5072.36 5072.46 5074.96 5075.07 5082.57  5126.2
 5143.78  5158.1 5173.65  5204.3 5209.39  5209.5 5209.61 5224.44 5251.48  5275.3
  5326.9    5327    5347    5362    5487    5517  5536.9  5594.6
    31.8    31.8    31.8   32.05   32.05   32.09   31.94   31.87   31.82   31.81
   31.67   31.67   33.67   33.67   33.66   33.56    33.5   33.47   33.36   33.12
   33.11   33.05   33.05   33.05   33.05   33.02   32.92   32.91   32.89   32.89
   32.86   32.86   32.78   32.78   32.65   32.65   32.65   32.65   32.62   32.49
   32.43   32.38   32.32   32.21    32.2    32.2    30.2   30.17   30.12   30.07
    29.9    29.9   29.56    29.3   29.51   29.57    29.6    29.7
    31.7    31.7   31.52    31.3    31.3   31.34    31.6   31.18   30.82   30.86
   30.46   30.44   30.44   30.44   30.41   29.89   29.71   29.67    29.5   28.54
   28.25   25.86   26.65   26.65   26.65   26.62   26.52   26.51   26.49   26.49
   26.46   26.46   26.38   26.38   26.25   26.25   26.25   26.11   29.74   29.98
   30.07   30.19   30.31    30.1   30.06   30.06   30.06   29.96   28.86   29.16
    29.8    29.8    28.8   28.75    28.3    28.5    29.2    29.6
Pier Skew, UpSta & Num, DnSta & Num=  ,4985.8, 2 ,4985.8, 2 , 0 , 0 , 0 ,,
     2.8     2.8
   17.41   27.62
     2.8     2.8
   17.31   27.52
Pier Skew, UpSta & Num, DnSta & Num=  ,5030.4, 2 ,5030.4, 2 , 0 , 0 , 0 ,,
     2.8     2.8
   13.92   27.48
     2.8     2.8
   13.82   27.38
Abutment Skew #Up #Dn= , 2 , 2
 4939.98 4941.78
   26.75   25.74
 4939.98 4941.78
   26.65   25.64
Abutment Skew #Up #Dn= , 2 , 2
 5072.46 5075.16
   24.95   26.35
 5072.46 5075.16
   24.85   26.25
BR Coef= 1 , 1 , 0 ,1.25, 0 ,,,0.8,0,2,0,
WSPro=,,,, 1 ,,,, 0 ,,,, 0 ,,,,-1 ,-1 ,-1 , 0 , 0 , 0 , 0 , 0
BR U #Sta/Elev= 58
  4514.1    31.8  4574.3    31.8  4614.1   31.62  4664.3    31.4  4665.1    31.4
  4672.3   31.44  4715.1    31.7  4736.4   31.28  4754.5   30.92 4756.26   30.96
  4804.5   30.56 4805.99   30.54  4806.1   30.54 4806.21   30.54 4810.11   30.51
  4841.3   29.99 4852.09   29.81  4857.2   29.77 4876.52    29.6 4919.72   28.64
  4921.9   28.35 4940.09   25.96 4940.18   25.95 4941.68   25.75 4941.78   25.74
 4952.35   23.97 4985.75   18.45  4988.2   18.38 4993.26    12.1 4994.79    12.4
 5004.06   12.39 5005.29   12.55 5030.33   15.05 5030.41   15.05 5072.36    24.9
 5072.46   24.95 5074.96   26.16 5075.07   26.21 5082.57   29.84  5126.2   30.08
 5143.78   30.17  5158.1   30.29 5173.65   30.41  5204.3    30.2 5209.39   30.16
  5209.5   30.16 5209.61   30.16 5224.44   30.06 5251.48   28.96  5275.3   29.26
  5326.9    29.9    5327    29.9    5347    28.9    5362   28.85    5487    28.4
    5517    28.6  5536.9    29.3  5594.6    29.7
BR U #Mann= 7
  4514.1      .2  4514.1      .1  4857.2     .14 4952.35    .055 5072.46     .14
  5158.1      .1  5594.6      .2
BR U Banks=4952.35,5072.46
BR D #Sta/Elev= 58
  4514.1    31.7  4574.3    31.7  4614.1   31.52  4664.3    31.3  4665.1    31.3
  4672.3   31.34  4715.1    31.6  4736.4   31.18  4754.5   30.82 4756.26   30.86
  4804.5   30.46 4805.99   30.44  4806.1   30.44 4806.21   30.44 4810.11   30.41
  4841.3   29.89 4852.09   29.71  4857.2   29.67 4876.52    29.5 4919.72   28.54
  4921.9   28.25 4940.09   25.86 4940.18   25.85 4941.68   25.65 4941.78   25.64
 4952.35   23.87 4985.75   18.35  4988.2   18.28 4993.26      12 4994.79    12.3
 5004.06   12.29 5005.29   12.45 5030.33   14.95 5030.41   14.95 5072.36    24.8
 5072.46   24.85 5074.96   26.06 5075.07   26.11 5082.57   29.74  5126.2   29.98
 5143.78   30.07  5158.1   30.19 5173.65   30.31  5204.3    30.1 5209.39   30.06
  5209.5   30.06 5209.61   30.06 5224.44   29.96 5251.48   28.86  5275.3   29.16
  5326.9    29.8    5327    29.8    5347    28.8    5362   28.75    5487    28.3
    5517    28.5  5536.9    29.2  5594.6    29.6
BR D #Mann= 7
  4514.1      .2  4514.1      .1  4857.2     .14 4952.35    .055 5072.46     .14
  5158.1      .1  5594.6      .2
BR D Banks=4952.35,5072.46
BC Design=,, 0 ,, 0 ,,,,,,
BC HTab HWMax=31.8
BC Use User HTab Curves=0
BC User HTab FreeFlow(D)= 0

Type RM Length L Ch R = 1 ,7043.8  ,41.8,41.8,41.8
BEGIN DESCRIPTION:
Downstream Section of Bridge/Culvert/Weir
END DESCRIPTION:
XS GIS Cut Line= 6
      3177199.03     13860155.63      3176961.07     13860169.63
      3176674.13     13860222.82      3176489.36     13860249.42
      3176359.19     13860263.41      3176126.83     13860274.61
#Sta/Elev= 30
  4514.1   31.71  4574.3   31.71  4664.3   31.31  4715.1   31.61  4754.5   30.83
 4756.26   30.87 4810.11   30.42  4857.2   29.68 4876.52   29.51 4919.72   28.55
 4941.78   25.65 4952.35   23.88 4985.75   18.36  4988.2   18.29 4993.26   12.01
 4994.79   12.31 5004.06    12.3 5030.41   14.96 5072.46   24.86 5082.57   29.75
  5158.1    30.2 5173.65   30.32 5224.44   29.97 5251.48   28.87    5327   29.81
    5347   28.81    5487   28.31    5517   28.51  5536.9   29.21  5594.6   29.61
#Mann= 7 , 1 , 0
  4514.1      .2       0  4514.1      .1       0  4857.2     .14       0
 4952.35    .055       0 5072.46     .14       0  5158.1      .1       0
  5594.6      .2       0
#XS Ineff= 2 , 0
       0    4930    31.5  5081.4       0    29.1
Permanent Ineff=
       F       F
Bank Sta=4952.35,5072.46
XS Rating Curve= 0 ,0
Exp/Cntr=0.5,0.3

Type RM Length L Ch R = 1 ,7002.0  ,23,23,23
BEGIN DESCRIPTION:
Upstream Section of Bridge/Culvert/Weir
END DESCRIPTION:
XS GIS Cut Line= 2
      3177080.27     13860124.34      3176314.18      13860263.9
#Sta/Elev= 28
  4626.3   31.38  4666.3   30.88  4676.3   31.68  4695.2   32.08  4735.2   31.68
  4744.5   31.78 4757.68   32.38 4786.87   31.61  4813.3   30.74 4855.73   30.81
 4902.53   31.05  4908.5   29.61  4934.4   23.38 4960.37    17.1 4981.43   17.58
 4996.91   12.14 5001.81   12.07 5003.11   12.44 5012.61   17.11 5022.03   17.41
 5050.07   23.98 5076.57   30.08 5139.76   29.25 5198.52   28.72  5230.6   29.59
  5252.5   30.18  5356.5   27.88    5405   28.88
#Mann= 7 , 1 , 0
  4626.3      .2       0  4626.3      .1       0  4908.5     .08       0
  4934.4    .055       0 5050.07     .08       0  5230.6      .1       0
    5405      .2       0
#XS Ineff= 2 , 0
       0  4927.9    24.9  5057.2       0    25.6
Permanent Ineff=
       F       F
Bank Sta=4934.4,5050.07
XS Rating Curve= 0 ,0
Exp/Cntr=0.5,0.3

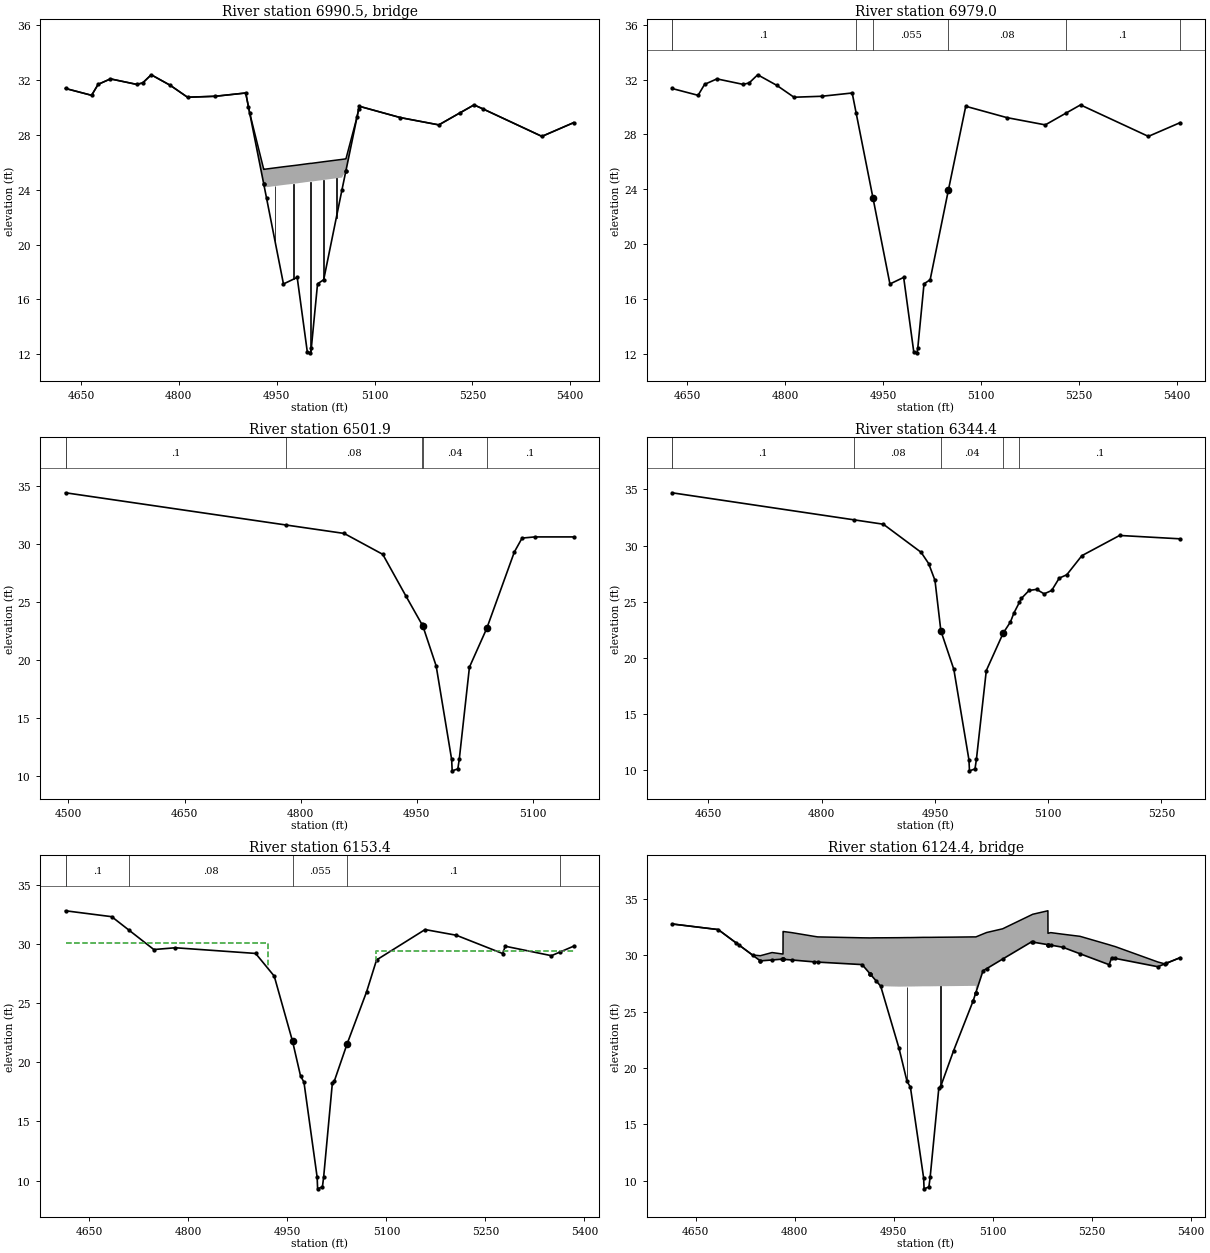
Type RM Length L Ch R = 3 ,6990.5  ,,,
BEGIN DESCRIPTION:
SERIES OF PIPELINES, SKEW ANGLE OF 40 DEGREES
END DESCRIPTION:
Bridge Culvert--1,0,-1,-1, 0
Deck Dist Width WeirC Skew NumUp NumDn MinLoCord MaxHiCord MaxSubmerge Is_Ogee
10,3,2.6,0, 36, 36, , , 0.95, 0, 1,1,,
  4626.3  4666.3  4676.3  4695.2  4735.2  4744.5 4757.68 4786.87  4813.3 4855.73
 4902.53 4906.76  4908.5 4930.17 4930.26  4934.4 4960.37 4981.43 4996.91 5001.81
 5003.11 5012.61 5022.03 5050.07 5056.01 5056.12 5073.26 5075.76 5076.57 5139.76
 5198.52  5230.6  5252.5  5266.5  5356.5    5405
    31.4    30.9    31.7    32.1    31.7    31.8    32.4   31.63   30.76   30.83
   31.07   30.06   29.64   25.49   25.49   25.52   25.68    25.8    25.9   25.93
   25.93   25.99   26.05   26.22   26.26   26.26   29.35   29.92    30.1   29.27
   28.74   29.61    30.2    29.9    27.9    28.9
    31.4    30.9    31.7    32.1    31.7    31.8    32.4   31.63   30.76   30.83
   31.07   30.05   29.63   24.42    24.4   24.19   24.35   24.47   24.57    24.6
    24.6   24.66   24.72   24.89   25.37   25.39   29.34   29.91    30.1   29.27
   28.74   29.61    30.2    29.9    27.9    28.9
  4626.3  4666.3  4676.3  4695.2  4735.2  4744.5 4757.68 4786.87  4813.3 4855.73
 4902.53 4906.76  4908.5 4930.17 4930.26  4934.4 4960.37 4981.43 4996.91 5001.81
 5003.11 5012.61 5022.03 5050.07 5056.01 5056.12 5073.26 5075.76 5076.57 5139.76
 5198.52  5230.6  5252.5  5266.5  5356.5    5405
    31.4    30.9    31.7    32.1    31.7    31.8    32.4   31.63   30.76   30.83
   31.07   30.06   29.64   25.49   25.49   25.52   25.68    25.8    25.9   25.93
   25.93   25.99   26.05   26.22   26.26   26.26   29.35   29.92    30.1   29.27
   28.74   29.61    30.2    29.9    27.9    28.9
    31.4    30.9    31.7    32.1    31.7    31.8    32.4   31.63   30.76   30.83
   31.07   30.05   29.63   24.42    24.4   24.19   24.35   24.47   24.57    24.6
    24.6   24.66   24.72   24.89   25.37   25.39   29.34   29.91    30.1   29.27
   28.74   29.61    30.2    29.9    27.9    28.9
Pier Skew, UpSta & Num, DnSta & Num=  ,4947.4, 2 ,4947.4, 2 , 0 , 0 , 0 ,,
     1.3     1.3
   19.09   25.27
     1.3     1.3
   19.09   25.27
Pier Skew, UpSta & Num, DnSta & Num=  ,4975.4, 2 ,4975.4, 2 , 0 , 0 , 0 ,,
     1.3     1.3
   16.45   25.44
     1.3     1.3
   16.45   25.44
Pier Skew, UpSta & Num, DnSta & Num=  ,5001.8, 2 ,5001.8, 2 , 0 , 0 , 0 ,,
     1.3     1.3
    11.1    25.6
     1.3     1.3
    11.1    25.6
Pier Skew, UpSta & Num, DnSta & Num=  ,5022, 2 ,5022, 2 , 0 , 0 , 0 ,,
     1.3     1.3
   16.41   25.72
     1.3     1.3
   16.41   25.72
Pier Skew, UpSta & Num, DnSta & Num=  ,5041.2, 2 ,5041.2, 2 , 0 , 0 , 0 ,,
     1.3     1.3
   20.76   25.84
     1.3     1.3
   20.76   25.84
BR Coef= 1 , 1 , 0 ,1.25, 0 ,,,0.8,0,2,0,
WSPro=,,,, 1 ,,,, 0 ,,,, 0 ,,,,-1 ,-1 ,-1 , 0 , 0 , 0 , 0 , 0
BR U #Sta/Elev= 36
  4626.3    31.4  4666.3    30.9  4676.3    31.7  4695.2    32.1  4735.2    31.7
  4744.5    31.8 4757.68    32.4 4786.87   31.63  4813.3   30.76 4855.73   30.83
 4902.53   31.07 4906.76   30.05  4908.5   29.63 4930.17   24.42 4930.26    24.4
  4934.4    23.4 4960.37   17.12 4981.43    17.6 4996.91   12.16 5001.81   12.09
 5003.11   12.46 5012.61   17.13 5022.03   17.43 5050.07      24 5056.01   25.37
 5056.12   25.39 5073.26   29.34 5075.76   29.91 5076.57    30.1 5139.76   29.27
 5198.52   28.74  5230.6   29.61  5252.5    30.2  5266.5    29.9  5356.5    27.9
    5405    28.9
BR U #Mann= 7
  4626.3      .2  4626.3      .1  4908.5     .08  4934.4    .055 5050.07     .08
  5230.6      .1    5405      .2
BR U Banks=4934.4,5050.07
BR D #Sta/Elev= 36
  4626.3    31.4  4666.3    30.9  4676.3    31.7  4695.2    32.1  4735.2    31.7
  4744.5    31.8 4757.68    32.4 4786.87   31.63  4813.3   30.76 4855.73   30.83
 4902.53   31.07 4906.76   30.05  4908.5   29.63 4930.17   24.42 4930.26    24.4
  4934.4    23.4 4960.37   17.12 4981.43    17.6 4996.91   12.16 5001.81   12.09
 5003.11   12.46 5012.61   17.13 5022.03   17.43 5050.07      24 5056.01   25.37
 5056.12   25.39 5073.26   29.34 5075.76   29.91 5076.57    30.1 5139.76   29.27
 5198.52   28.74  5230.6   29.61  5252.5    30.2  5266.5    29.9  5356.5    27.9
    5405    28.9
BR D #Mann= 7
  4626.3      .2  4626.3      .1  4908.5     .08  4934.4    .055 5050.07     .08
  5230.6      .1    5405      .2
BR D Banks=4934.4,5050.07
BC Design=,, 0 ,, 0 ,,,,,,
BC HTab HWMax=32.38
BC Use User HTab Curves=0
BC User HTab FreeFlow(D)= 0

Type RM Length L Ch R = 1 ,6979.0  ,477.1,477.1,477.1
BEGIN DESCRIPTION:
Downstream Section of Bridge/Culvert/Weir
END DESCRIPTION:
XS GIS Cut Line= 2
      3177064.32     13860107.77      3176298.23     13860247.33
#Sta/Elev= 28
  4626.3   31.36  4666.3   30.86  4676.3   31.66  4695.2   32.06  4735.2   31.66
  4744.5   31.76 4757.68   32.36 4786.87   31.59  4813.3   30.72 4855.73   30.79
 4902.53   31.03  4908.5   29.59  4934.4   23.36 4960.37   17.08 4981.43   17.56
 4996.91   12.12 5001.81   12.05 5003.11   12.42 5012.61   17.09 5022.03   17.39
 5050.07   23.96 5076.57   30.06 5139.76   29.23 5198.52    28.7  5230.6   29.57
  5252.5   30.16  5356.5   27.86    5405   28.86
#Mann= 7 , 1 , 0
  4626.3      .2       0  4626.3      .1       0  4908.5     .08       0
  4934.4    .055       0 5050.07     .08       0  5230.6      .1       0
    5405      .2       0
#XS Ineff= 2 , 0
       0  4927.9    24.9  5057.2       0    25.6
Permanent Ineff=
       F       F
Bank Sta=4934.4,5050.07
XS Rating Curve= 0 ,0
Exp/Cntr=0.5,0.3

Type RM Length L Ch R = 1 ,6501.9  ,71.3,157.5,117.8
BEGIN DESCRIPTION:
Cross Section 6501.9-Interpolated
END DESCRIPTION:
XS GIS Cut Line= 4
      3176578.71     13859749.49      3176300.72     13860050.65
      3176161.72     13860189.65      3176120.04     13860217.25
#Sta/Elev= 18
  4496.2    34.4  4780.7   31.63  4856.2    30.9  4906.1    29.1  4936.1    25.5
  4956.6   23.08  4957.9   22.93  4975.1   19.49  4995.1   11.44  4995.8   10.46
  5003.1   10.63    5005   11.49  5018.1   19.39  5040.5   22.73  5076.1    29.3
  5086.1    30.5  5102.6    30.6  5152.6    30.6
#Mann= 6 , 1 , 0
  4496.2      .2       0  4496.2      .1       0  4780.7     .08       0
  4956.6      .1       0  4957.9     .04       0  5040.5      .1       0
Bank Sta=4957.9,5040.5
XS Rating Curve= 0 ,0
Exp/Cntr=0.3,0.1

Type RM Length L Ch R = 1 ,6344.4  ,220.6,191,152.6
BEGIN DESCRIPTION:
Cross Section 6344.4-Interpolated
END DESCRIPTION:
XS GIS Cut Line= 4
      3176549.49     13859748.55      3176284.29     13859974.46
      3176186.07     13860010.48      3176062.76     13860192.63
#Sta/Elev= 27
  4601.7    34.7  4842.9   32.29  4881.7    31.9  4931.7    29.4  4941.7    28.4
  4950.1    26.9  4957.9   22.41  4975.1   18.97  4995.1   10.92  4995.8    9.94
  5003.1   10.11    5005   10.97  5018.1   18.87  5040.5   22.21  5050.1    23.2
  5054.7      24    5062   24.95  5064.7    25.3  5074.7      26  5084.7    26.1
  5094.7    25.7  5104.7      26  5114.7    27.1  5124.7    27.4  5144.7    29.1
  5194.7    30.9  5274.7    30.6
#Mann= 6 , 1 , 0
  4601.7      .2       0  4601.7      .1       0  4842.9     .08       0
  4957.9     .04       0  5040.5     .08       0    5062      .1       0
Bank Sta=4957.9,5040.5
XS Rating Curve= 0 ,0
Exp/Cntr=0.5,0.3

Type RM Length L Ch R = 1 ,6153.4  ,58,58,58
BEGIN DESCRIPTION:
Upstream Section of Bridge/Culvert/Weir
END DESCRIPTION:
XS GIS Cut Line= 6
      3175966.91      13859555.7      3176094.37     13859756.69
      3176101.37     13859790.28      3176084.57     13859889.66
      3176006.18     13860052.03      3175994.99     13860266.19
#Sta/Elev= 26
  4613.9   32.83  4683.9   32.33  4710.3   31.18  4747.7   29.55  4780.3    29.7
  4901.9   29.22  4930.1    27.3  4957.9   21.77  4969.9   18.86  4975.1   18.33
  4995.1   10.28  4995.8     9.3  5003.1    9.47    5005   10.33  5018.1   18.23
    5021    18.4  5040.5   21.57  5070.1   25.99  5085.1   28.67  5158.6   31.24
  5205.9   30.76  5276.2   29.21    5280   29.83    5350   29.03  5362.6   29.33
  5383.5   29.83
#Mann= 6 , 1 , 0
  4613.9      .2       0  4613.9      .1       0  4710.3     .08       0
  4957.9    .055       0  5040.5      .1       0  5362.6      .2       0
#XS Ineff= 2 , 0
       0    4920    30.1    5084       0    29.4
Permanent Ineff=
       F       F
Bank Sta=4957.9,5040.5
XS Rating Curve= 0 ,0
Exp/Cntr=0.5,0.3

Type RM Length L Ch R = 3 ,6124.4  ,,,
BEGIN DESCRIPTION:
ACCESS ROAD
Structure ID: P07-3
END DESCRIPTION:
Bridge Culvert--1,0,-1,-1, 0
Deck Dist Width WeirC Skew NumUp NumDn MinLoCord MaxHiCord MaxSubmerge Is_Ogee
10,38,2.6,0, 54, 54, , , 0.95, 0, 1,1,,
  4613.9  4683.9  4710.3    4716    4736  4747.7  4747.8  4765.5  4780.3 4782.09
  4782.2 4782.31  4795.3  4829.2  4834.8  4901.9  4913.7 4913.81  4913.9  4922.7
  4930.1  4957.9  4969.9  4975.1  4995.1  4995.8  5003.1    5005  5018.1    5021
  5040.5  5070.1  5070.2 5074.09  5074.2  5074.3  5085.1  5090.6  5114.8  5158.6
  5160.3 5183.29  5183.4 5183.51  5187.6  5205.9  5232.1  5276.2    5280  5285.3
    5350  5360.3  5362.6  5383.5
    32.8    32.3   31.15   30.91   30.04   29.98   29.98   30.26   30.14   30.13
   32.13   32.13   32.03    31.7   31.65   31.57   31.56   31.56   31.56   31.57
   31.57   31.58   31.59   31.59   31.61   31.61   31.61   31.61   31.62   31.62
   31.63   31.65   31.65   31.65   31.65   31.65   31.91   32.04   32.37   33.61
   33.66   33.97   33.97   31.97   32.03   31.89    31.7   30.95   30.88   30.79
   29.42   29.26   29.31    29.8
    32.8    32.3   31.15    30.9   30.03   29.52   29.52    29.6   29.67   29.66
   29.66   29.66    29.6   29.43   29.41   29.19   28.39   28.38   28.37   27.77
   27.27   27.23   27.24   27.24   27.26   27.26   27.26   27.26   27.27   27.27
   27.28    27.3    27.3    27.3   26.69   26.71   28.64   28.83   29.68   31.21
   31.19   30.96   30.96   30.96   30.92   30.73   30.15   29.18    29.8   29.74
      29   29.25    29.3    29.8
  4613.9  4683.9  4710.3    4716    4736  4747.7  4747.8  4765.5  4780.3 4782.09
  4782.2 4782.31  4795.3  4829.2  4834.8  4901.9  4913.7 4913.81  4913.9  4922.7
  4930.1  4957.9  4969.9  4975.1  4995.1  4995.8  5003.1    5005  5018.1    5021
  5040.5  5070.1  5070.2 5074.09  5074.2  5074.3  5085.1  5090.6  5114.8  5158.6
  5160.3 5183.29  5183.4 5183.51  5187.6  5205.9  5232.1  5276.2    5280  5285.3
    5350  5360.3  5362.6  5383.5
    32.8    32.3   31.15   30.91   30.04   29.98   29.98   30.26   30.14   30.13
   32.13   32.13   32.03    31.7   31.65   31.57   31.56   31.56   31.56   31.57
   31.57   31.58   31.59   31.59   31.61   31.61   31.61   31.61   31.62   31.62
   31.63   31.65   31.65   31.65   31.65   31.65   31.91   32.04   32.37   33.61
   33.66   33.97   33.97   31.97   32.03   31.89    31.7   30.95   30.88   30.79
   29.42   29.26   29.31    29.8
    32.7    32.2   31.05    30.8   29.93   29.42   29.42    29.5   29.57   29.56
   29.56   29.56    29.5   29.33   29.31   29.09   28.29   28.28   28.27   27.67
   27.17   27.13   27.14   27.14   27.16   27.16   27.16   27.16   27.17   27.17
   27.18    27.2    27.2    27.2   26.59   26.61   28.54   28.73   29.58   31.11
   31.09   30.86   30.86   30.86   30.82   30.63   30.05   29.08    29.7   29.64
    28.9   29.15    29.2    29.7
Pier Skew, UpSta & Num, DnSta & Num=  ,4969.9, 2 ,4969.9, 2 , 0 , 0 , 0 ,,
     1.4     1.4
   17.76   28.24
     1.4     1.4
   17.66   28.14
Pier Skew, UpSta & Num, DnSta & Num=  ,5021, 2 ,5021, 2 , 0 , 0 , 0 ,,
     1.4     1.4
   17.33   28.27
     1.4     1.4
   17.23   28.17
Abutment Skew #Up #Dn= , 2 , 2
  4913.7  4922.7
   28.37   27.77
  4913.7  4922.7
   28.27   27.67
Abutment Skew #Up #Dn= , 2 , 2
  5070.2 5074.29
   25.98    27.3
  5070.2 5074.29
   25.88    27.2
BR Coef= 1 , 1 , 0 ,1.25, 0 ,,,0.8,0,2,0,
WSPro=,,,, 1 ,,,, 0 ,,,, 0 ,,,,-1 ,-1 ,-1 , 0 , 0 , 0 , 0 , 0
BR U #Sta/Elev= 54
  4613.9    32.8  4683.9    32.3  4710.3   31.15    4716    30.9    4736   30.03
  4747.7   29.52  4747.8   29.52  4765.5    29.6  4780.3   29.67 4782.09   29.66
  4782.2   29.66 4782.31   29.66  4795.3    29.6  4829.2   29.43  4834.8   29.41
  4901.9   29.19  4913.7   28.39 4913.81   28.38  4913.9   28.37  4922.7   27.77
  4930.1   27.27  4957.9   21.74  4969.9   18.83  4975.1    18.3  4995.1   10.25
  4995.8    9.27  5003.1    9.44    5005    10.3  5018.1    18.2    5021   18.37
  5040.5   21.54  5070.1   25.96  5070.2   25.98 5074.09   26.67  5074.2   26.69
  5074.3   26.71  5085.1   28.64  5090.6   28.83  5114.8   29.68  5158.6   31.21
  5160.3   31.19 5183.29   30.96  5183.4   30.96 5183.51   30.96  5187.6   30.92
  5205.9   30.73  5232.1   30.15  5276.2   29.18    5280    29.8  5285.3   29.74
    5350      29  5360.3   29.25  5362.6    29.3  5383.5    29.8
BR U #Mann= 6
  4613.9      .2  4613.9      .1  4710.3     .08  4957.9    .055  5040.5      .1
  5362.6      .2
BR U Banks=4957.9,5040.5
BR D #Sta/Elev= 54
  4613.9    32.7  4683.9    32.2  4710.3   31.05    4716    30.8    4736   29.93
  4747.7   29.42  4747.8   29.42  4765.5    29.5  4780.3   29.57 4782.09   29.56
  4782.2   29.56 4782.31   29.56  4795.3    29.5  4829.2   29.33  4834.8   29.31
  4901.9   29.09  4913.7   28.29 4913.81   28.28  4913.9   28.27  4922.7   27.67
  4930.1   27.17  4957.9   21.64  4969.9   18.73  4975.1    18.2  4995.1   10.15
  4995.8    9.17  5003.1    9.34    5005    10.2  5018.1    18.1    5021   18.27
  5040.5   21.44  5070.1   25.86  5070.2   25.88 5074.09   26.57  5074.2   26.59
  5074.3   26.61  5085.1   28.54  5090.6   28.73  5114.8   29.58  5158.6   31.11
  5160.3   31.09 5183.29   30.86  5183.4   30.86 5183.51   30.86  5187.6   30.82
  5205.9   30.63  5232.1   30.05  5276.2   29.08    5280    29.7  5285.3   29.64
    5350    28.9  5360.3   29.15  5362.6    29.2  5383.5    29.7
BR D #Mann= 6
  4613.9      .2  4613.9      .1  4710.3     .08  4957.9    .055  5040.5      .1
  5362.6      .2
BR D Banks=4957.9,5040.5
BC Design=,, 0 ,, 0 ,,,,,,
BC HTab HWMax=32.83
BC Use User HTab Curves=0
BC User HTab FreeFlow(D)= 0