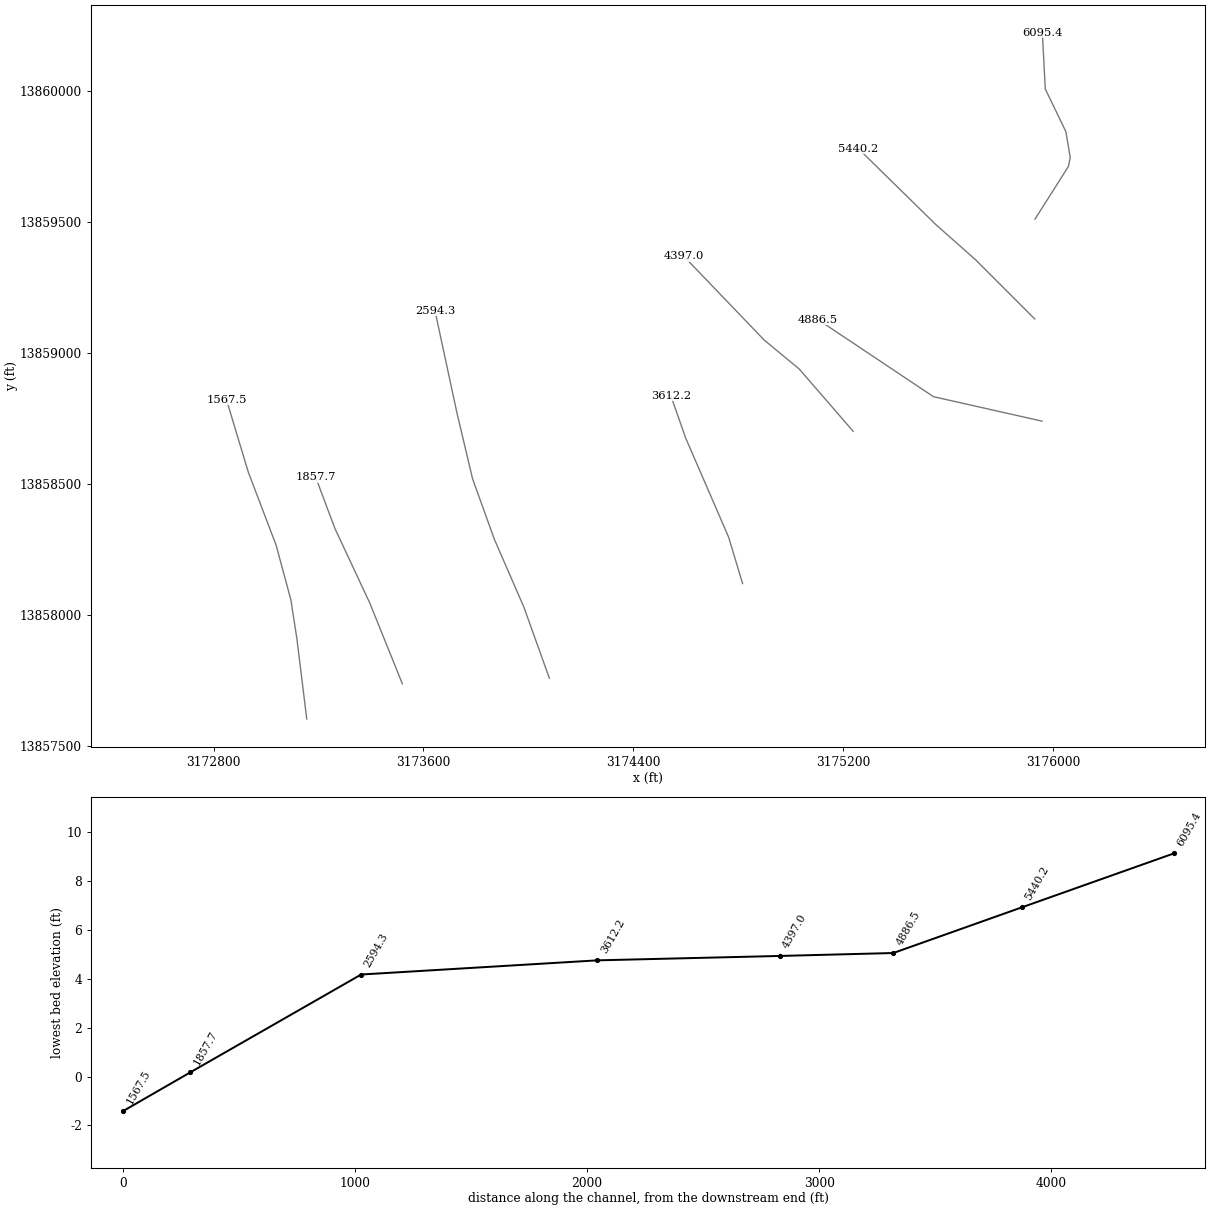
HEC-RAS study P107-00-00.prj: P107-00-00

--- P107-00-00.g01 (geometry) --- (continued)

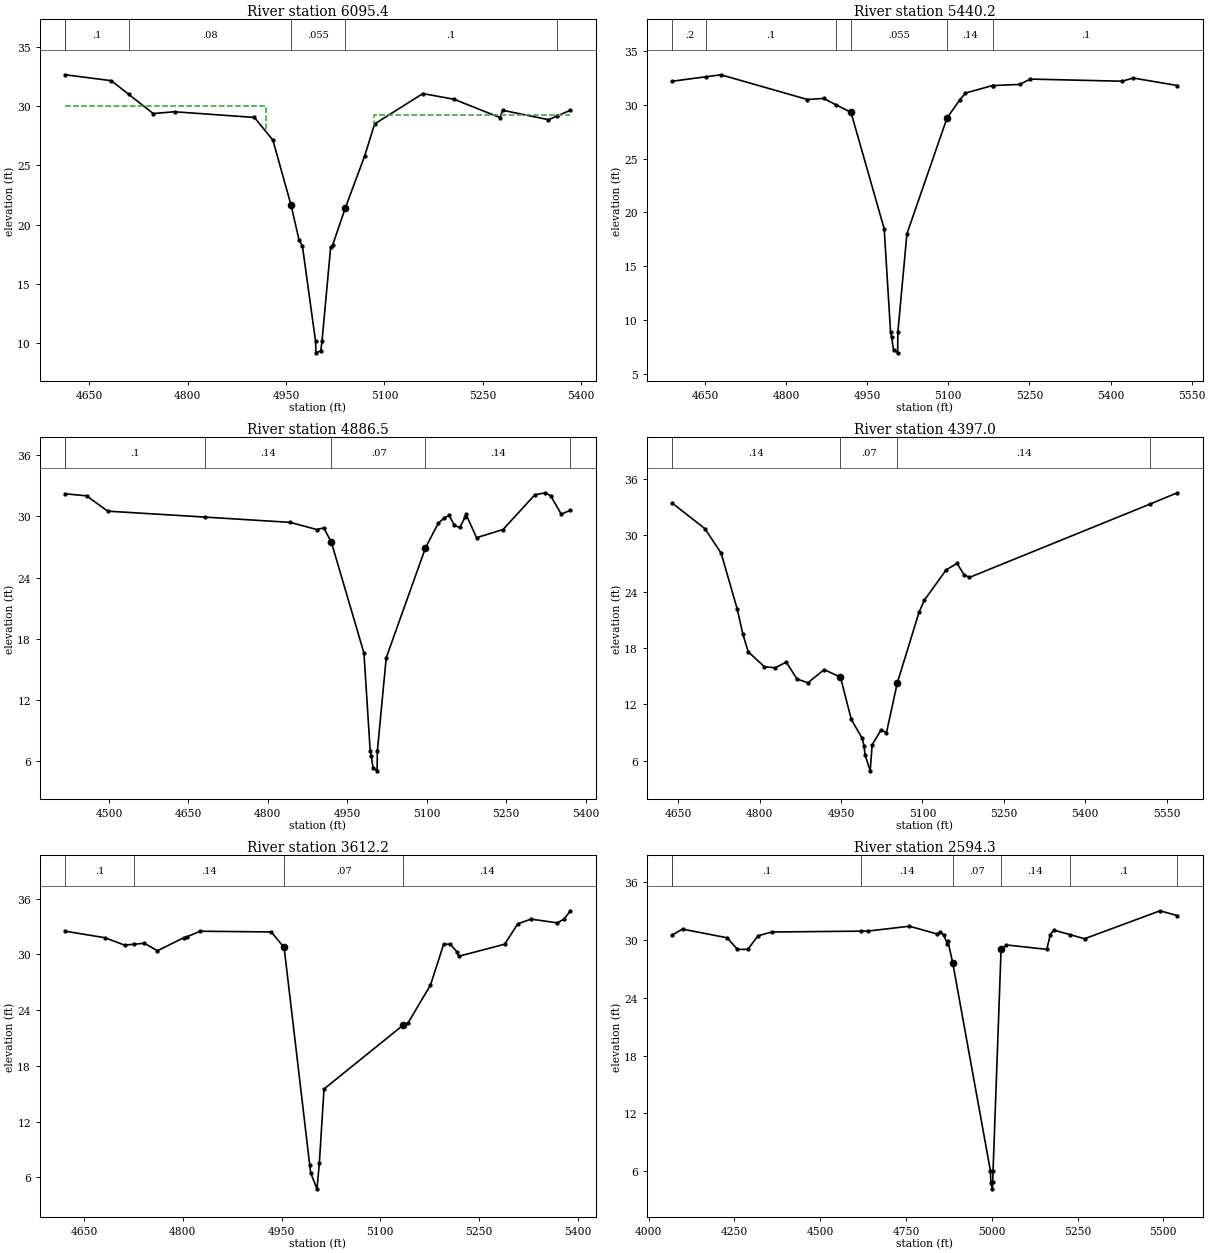
Type RM Length L Ch R = 1 ,6095.4  ,655.2,655.2,655.2
BEGIN DESCRIPTION:
Downstream Section of Bridge/Culvert/Weir
END DESCRIPTION:
XS GIS Cut Line= 6
      3175931.45      13859509.8      3176058.91     13859710.79
      3176065.91     13859744.38      3176049.11     13859843.76
      3175970.72     13860006.13      3175959.53     13860220.29
#Sta/Elev= 26
  4613.9   32.67  4683.9   32.17  4710.3   31.02  4747.7   29.39  4780.3   29.54
  4901.9   29.06  4930.1   27.14  4957.9   21.61  4969.9    18.7  4975.1   18.17
  4995.1   10.12  4995.8    9.14  5003.1    9.31    5005   10.17  5018.1   18.07
    5021   18.24  5040.5   21.41  5070.1   25.83  5085.1   28.51  5158.6   31.08
  5205.9    30.6  5276.2   29.05    5280   29.67    5350   28.87  5362.6   29.17
  5383.5   29.67
#Mann= 6 , 1 , 0
  4613.9      .2       0  4613.9      .1       0  4710.3     .08       0
  4957.9    .055       0  5040.5      .1       0  5362.6      .2       0
#XS Ineff= 2 , 0
       0    4920      30    5084       0    29.3
Permanent Ineff=
       F       F
Bank Sta=4957.9,5040.5
XS Rating Curve= 0 ,0
Exp/Cntr=0.5,0.3

Type RM Length L Ch R = 1 ,5440.2  ,526.2,553.7,546.9
BEGIN DESCRIPTION:
Cross Section 5440.2-Interpolated
END DESCRIPTION:
XS GIS Cut Line= 4
      3175930.52     13859129.32      3175704.18     13859355.66
       3175553.6     13859488.87      3175258.77     13859778.02
#Sta/Elev= 24
  4589.5    32.2  4652.5   32.62  4679.5    32.8  4839.5    30.5  4869.5    30.6
  4892.3   30.01  4920.1    29.3  4981.5   18.46  4993.3    8.83  4995.2    8.39
  4998.7    7.21  5006.3    6.93  5006.8    8.88  5023.5      18  5097.6   28.77
  5121.8    30.5  5131.8    31.1  5181.8    31.8  5183.4    31.8  5231.8    31.9
  5251.8    32.4  5421.8    32.2  5441.8    32.5  5523.6    31.8
#Mann= 6 , 1 , 0
  4589.5      .2       0  4652.5      .1       0  4892.3     .08       0
  4920.1    .055       0  5097.6     .14       0  5183.4      .1       0
Bank Sta=4920.1,5097.6
XS Rating Curve= 0 ,0
Exp/Cntr=0.3,0.1

Type RM Length L Ch R = 1 ,4886.5  ,427.3,489.5,498.5
BEGIN DESCRIPTION:
Cross Section 4886.5
END DESCRIPTION:
XS GIS Cut Line= 4
      3175958.31      13858739.7      3175544.07     13858833.03
       3175268.2     13859017.43      3175104.09     13859126.83
#Sta/Elev= 30
  4417.7    32.2  4457.7      32  4497.7    30.5  4680.9   29.92  4842.3    29.4
  4892.3    28.7  4905.7   28.86  4920.1   27.43  4981.5   16.59  4993.3    6.96
  4995.2    6.52  4998.7    5.34  5006.3    5.06  5006.8    7.01  5023.5   16.13
  5097.6    26.9  5121.8   29.32  5132.3    29.8  5142.3    30.1  5152.3    29.1
  5162.3    28.9  5172.3    29.9  5174.1    30.2  5194.1    27.9  5244.1    28.7
  5304.1    32.1  5324.1    32.3  5334.1      32  5354.1    30.2  5371.4    30.6
#Mann= 6 , 1 , 0
  4417.7      .2       0  4417.7      .1       0  4680.9     .14       0
  4920.1     .07       0  5097.6     .14       0  5371.4      .2       0
Bank Sta=4920.1,5097.6
XS Rating Curve= 0 ,0
Exp/Cntr=0.3,0.1

Type RM Length L Ch R = 1 ,4397.0  ,707.1,784.8,553.9
BEGIN DESCRIPTION:
Cross Section 4397.0-Interpolated
END DESCRIPTION:
XS GIS Cut Line= 4
      3175238.31     13858701.01      3175032.35     13858938.66
      3174899.14      13859048.7      3174592.11      13859368.8
#Sta/Elev= 30
    4639    33.4    4699    30.7    4729    28.1    4759    22.1    4769    19.5
    4779    17.6    4809      16    4829    15.9    4849    16.5    4869    14.7
    4889    14.3    4919    15.7    4949    14.9    4969    10.4    4989     8.4
  4992.7    7.55  4994.2    6.67  5003.8    4.94  5007.4    7.69  5023.8     9.3
  5033.8       9  5053.8    14.3  5093.8    21.8  5103.8    23.1  5143.8    26.3
  5163.8      27  5176.6    25.8  5186.6    25.5  5519.5    33.3  5569.8    34.5
#Mann= 4 , 1 , 0
    4639     .14       0    4949     .07       0  5053.8     .14       0
  5519.5      .2       0
Bank Sta=4949,5053.8
XS Rating Curve= 0 ,0
Exp/Cntr=0.3,0.1

Type RM Length L Ch R = 1 ,3612.2  ,1004.8,1017.9,937.4
BEGIN DESCRIPTION:
Cross Section 3612.2
END DESCRIPTION:
XS GIS Cut Line= 4
      3174816.69     13858120.41      3174763.24     13858297.86
      3174599.13     13858676.58      3174543.24     13858836.53
#Sta/Elev= 29
  4621.5    32.5  4681.5    31.8  4711.5      31  4726.1    31.1  4741.5    31.2
  4761.5    30.4  4801.5    31.8  4806.3    31.9  4826.3    32.5  4934.3   32.42
  4953.9   30.75  4992.7    7.37  4994.2    6.49  5003.8    4.76  5007.4    7.51
  5014.5   15.51  5134.6   22.38  5142.5   22.66  5176.3    26.7  5196.3    31.1
  5206.3    31.1  5216.3    30.3    5219    29.8    5289    31.1    5309    33.3
    5329    33.8    5369    33.4    5379    33.8    5389    34.7
#Mann= 4 , 1 , 0
  4621.5      .1       0  4726.1     .14       0  4953.9     .07       0
  5134.6     .14       0
Bank Sta=4953.9,5134.6
XS Rating Curve= 0 ,0
Exp/Cntr=0.3,0.1

Type RM Length L Ch R = 1 ,2594.3  ,653.8,736.6,652.2
BEGIN DESCRIPTION:
Cross Section 2594.3
END DESCRIPTION:
XS GIS Cut Line= 6
      3174080.03     13857759.57      3173982.23     13858032.17
      3173869.86      13858290.2      3173786.98     13858520.88
      3173728.07     13858769.15      3173643.91      13859160.5
#Sta/Elev= 30
  4069.1    30.5  4099.1    31.1  4229.1    30.2  4259.1      29  4289.1      29
  4319.1    30.4  4358.7    30.8  4619.3   30.89  4640.1    30.9  4760.1    31.4
  4840.1    30.6  4850.1    30.8  4860.1    30.5  4870.1    29.6  4871.9    29.9
  4886.4   27.59  4996.2    6.03  4997.5    4.75  5001.6    4.18  5002.8    4.84
  5003.8    6.06  5027.2   29.01  5042.6   29.46  5160.4      29  5170.4    30.5
  5180.4      31  5226.7   30.54  5270.4    30.1  5490.4      33  5540.7    32.5
#Mann= 7 , 1 , 0
  4069.1      .2       0  4069.1      .1       0  4619.3     .14       0
  4886.4     .07       0  5027.2     .14       0  5226.7      .1       0
  5540.7      .2       0
Bank Sta=4886.4,5027.2
XS Rating Curve= 0 ,0
Exp/Cntr=0.3,0.1

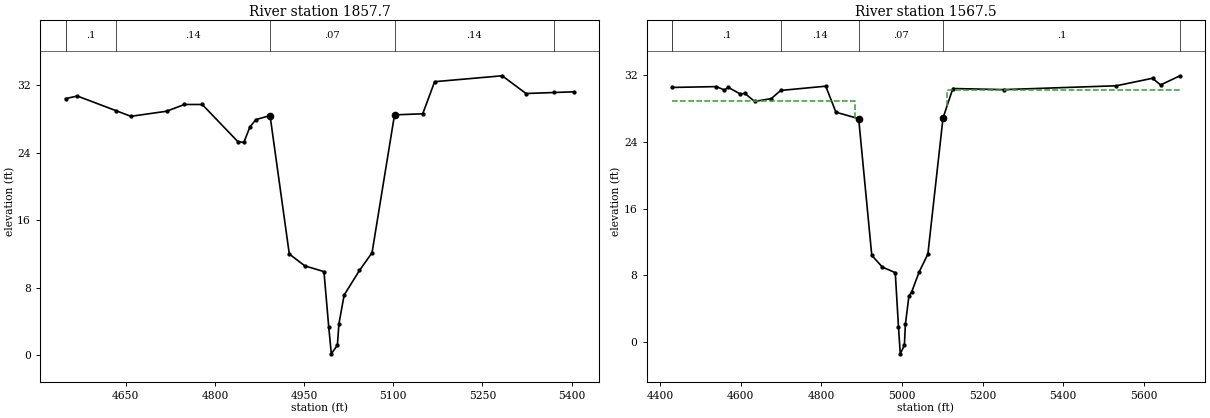
Type RM Length L Ch R = 1 ,1857.7  ,314.5,290.2,279.2
BEGIN DESCRIPTION:
Cross Section 1857.7-Interpolated
END DESCRIPTION:
XS GIS Cut Line= 4
      3173519.36     13857738.57      3173395.63      13858045.6
      3173262.74     13858329.71      3173188.78     13858526.33
#Sta/Elev= 29
  4548.6    30.4  4568.6    30.7  4634.2   28.95  4658.6    28.3  4718.6    28.9
  4748.6    29.7  4778.6    29.7  4838.6    25.3  4848.6    25.2  4858.6      27
  4868.6    27.9  4892.7   28.39  4925.1   11.99  4951.2   10.59  4983.4    9.91
  4991.4    3.39  4995.8     .17    5006     1.2  5008.6    3.74  5017.4    7.14
  5043.1   10.04  5064.3   12.14  5102.1   28.47  5149.6    28.6  5169.6    32.4
  5283.3    33.1  5323.3      31  5370.8   31.12  5403.3    31.2
#Mann= 6 , 1 , 0
  4548.6      .2       0  4548.6      .1       0  4634.2     .14       0
  4892.7     .07       0  5102.1     .14       0  5370.8      .1       0
Bank Sta=4892.7,5102.1
XS Rating Curve= 0 ,0
Exp/Cntr=0.5,0.3

Type RM Length L Ch R = 1 ,1567.5  ,120,120,120
BEGIN DESCRIPTION:
Upstream Section of Bridge/Culvert/Weir
END DESCRIPTION:
XS GIS Cut Line= 6
      3173155.02     13857604.43      3173117.36     13857910.75
      3173094.47      13858058.5      3173038.29     13858266.58
      3172932.16     13858545.42      3172848.88     13858821.76
#Sta/Elev= 30
  4429.3   30.55  4539.3   30.65  4559.3   30.25  4569.3   30.55  4599.3   29.75
  4609.7   29.85  4634.4   28.87  4675.7   29.21    4699   30.19  4810.9    30.7
  4836.1   27.58  4892.6    26.8  4925.1    10.4  4951.2       9  4983.4    8.32
  4991.4     1.8  4995.8   -1.42    5006    -.39  5008.6    2.15  5017.4    5.55
  5023.7    5.96  5043.1    8.45  5064.3   10.55  5101.9   26.88  5126.3   30.42
  5252.2   30.29  5531.8   30.75  5621.8   31.65  5641.8   30.85    5690   31.95
#Mann= 6 , 1 , 0
  4429.3      .2       0  4429.3      .1       0    4699     .14       0
  4892.6     .07       0  5101.9      .1       0    5690      .2       0
#XS Ineff= 2 , 0
       0    4883    28.9    5112       0    30.3
Permanent Ineff=
       F       F
Bank Sta=4892.6,5101.9
XS Rating Curve= 0 ,0
Exp/Cntr=0.5,0.3