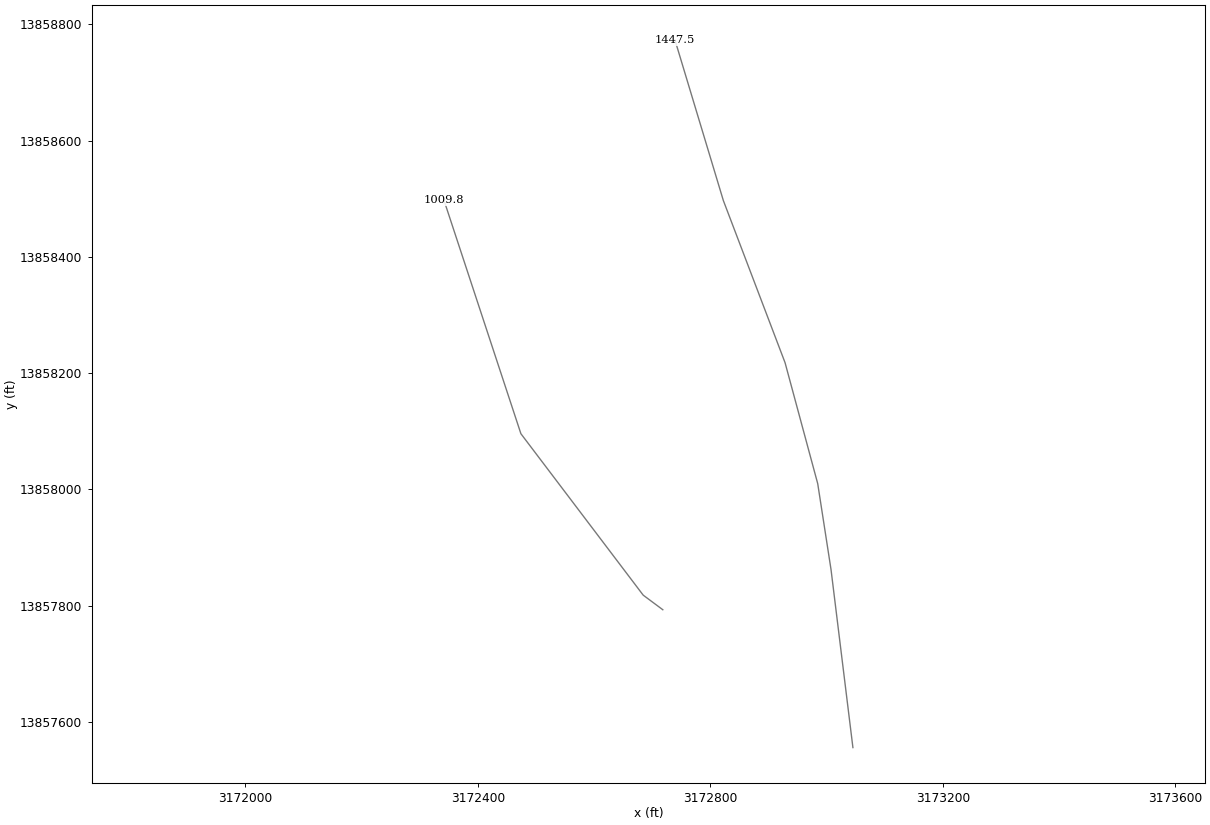
HEC-RAS study P107-00-00.prj: P107-00-00

--- P107-00-00.g01 (geometry) --- (continued)

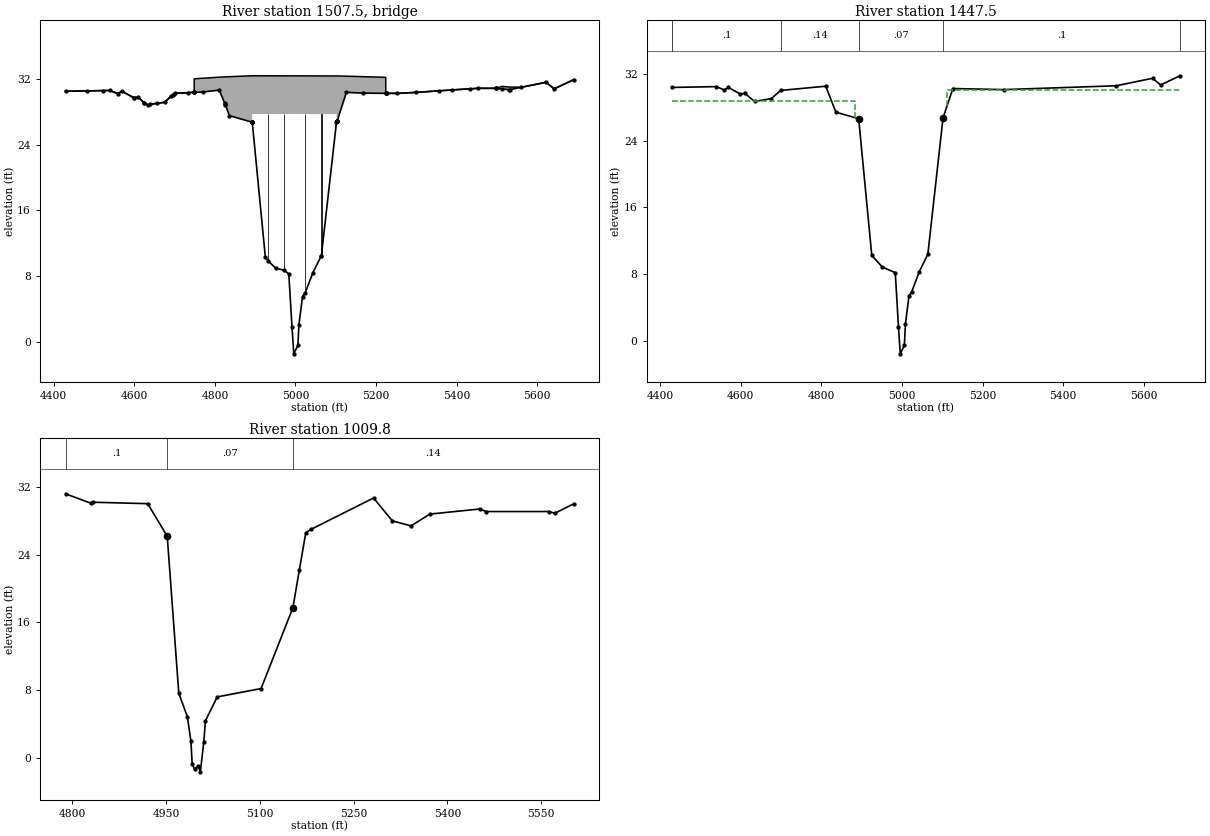
Type RM Length L Ch R = 3 ,1507.5  ,,,
BEGIN DESCRIPTION:
NORMANDY DRIVE
Structure ID: P07-2
END DESCRIPTION:
Bridge Culvert--1,0,-1,-1, 0
Deck Dist Width WeirC Skew NumUp NumDn MinLoCord MaxHiCord MaxSubmerge Is_Ogee
10,100,2.6,0, 37, 37, , , 0.95, 0, 1,1,,
  4429.3  4539.3  4559.3  4569.3  4599.3  4609.7    4625  4634.4  4638.5  4675.7
  4690.2  4702.2 4748.59  4748.7  4769.5  4810.9    4826  4836.1  4892.2 4892.41
  4892.5 5101.99  5102.1  5103.1  5126.3    5224 5224.11  5252.2  5298.4  5453.6
  5498.5  5511.3  5531.8    5560  5621.8  5641.8    5690
    30.5   30.61   30.21   30.51   29.71   29.81   29.08   28.83   28.92   29.17
   29.88   30.25   30.38   32.02   32.09   32.22   32.26   32.28   32.39   32.39
   32.39   32.37   32.37   32.37   32.34    32.2   30.26   30.25   30.37   30.87
   30.86    31.1   31.02   30.99    31.6    30.8    31.9
    30.5    30.6    30.2    30.5    29.7    29.8   29.07   28.82   28.91   29.16
   29.87   30.24   30.37   30.37   30.41   30.65   28.84   27.53   26.74   26.74
   27.74   27.72   26.83   26.83   30.37   30.25   30.25   30.24   30.36   30.86
   30.85   30.79    30.7   30.98    31.6    30.8    31.9
  4429.3  4539.3  4559.3  4569.3  4599.3  4609.7    4625  4634.4  4638.5  4675.7
  4690.2  4702.2 4748.59  4748.7  4769.5  4810.9    4826  4836.1  4892.2 4892.41
  4892.5 5101.99  5102.1  5103.1  5126.3    5224 5224.11  5252.2  5298.4  5453.6
  5498.5  5511.3  5531.8    5560  5621.8  5641.8    5690
    30.5   30.61   30.21   30.51   29.71   29.81   29.08   28.83   28.92   29.17
   29.88   30.25   30.38   32.02   32.09   32.22   32.26   32.28   32.39   32.39
   32.39   32.37   32.37   32.37   32.34    32.2   30.26   30.25   30.37   30.87
   30.86    31.1   31.02   30.99    31.6    30.8    31.9
   30.37   30.47   30.07   30.37   29.57   29.67   28.94   28.69   28.78   29.03
   29.74   30.11   30.24   30.24   30.28   30.52   28.71    27.4   26.61   26.61
   27.61   27.59    26.7    26.7   30.24   30.12   30.12   30.11   30.23   30.73
   30.72   30.66   30.57   30.85   31.47   30.67   31.77
Pier Skew, UpSta & Num, DnSta & Num=  ,4931.4, 2 ,4931.4, 2 , 0 , 0 , 0 ,,
     1.3     1.3
    8.85   28.74
     1.3     1.3
    8.72   28.61
Pier Skew, UpSta & Num, DnSta & Num=  ,4971.6, 2 ,4971.6, 2 , 0 , 0 , 0 ,,
     1.3     1.3
    7.69   28.73
     1.3     1.3
    7.56    28.6
Pier Skew, UpSta & Num, DnSta & Num=  ,5023.6, 2 ,5023.6, 2 , 0 , 0 , 0 ,,
     1.3     1.3
    4.86   28.73
     1.3     1.3
    4.73    28.6
Pier Skew, UpSta & Num, DnSta & Num=  ,5064.2, 2 ,5064.2, 2 , 0 , 0 , 0 ,,
     1.3     1.3
    9.43   28.72
     1.3     1.3
     9.3   28.59
BR Coef= 1 , 1 , 0 ,1.25, 0 ,,,0.8,0,2,0,
WSPro=,,,, 1 ,,,, 0 ,,,, 0 ,,,,-1 ,-1 ,-1 , 0 , 0 , 0 , 0 , 0
BR U #Sta/Elev= 77
  4429.3    30.5  4482.1   30.55  4522.1   30.58  4539.3    30.6  4559.3    30.2
  4569.3    30.5  4599.3    29.7  4599.7    29.7  4609.7    29.8    4625   29.07
  4625.1   29.07  4634.4   28.82  4638.5   28.91  4655.4   29.02  4675.7   29.16
  4690.2   29.87  4696.6   30.07    4699   30.14  4702.2   30.24  4733.3   30.34
 4748.59   30.37  4748.7   30.37 4748.81   30.37  4769.5   30.41  4810.9   30.65
  4824.4   29.03  4825.5    28.9    4826   28.84  4836.1   27.53  4892.2   26.74
  4892.3   26.74 4892.41   26.74  4892.5   26.75  4892.6   26.75  4892.7   26.75
  4925.1   10.35  4931.4    9.88  4951.2    8.95  4971.6    8.71  4983.4    8.27
  4991.4    1.75  4995.8   -1.47    5006    -.44  5008.6     2.1  5017.4     5.5
  5023.7    5.91  5043.1     8.4  5064.2   10.49  5064.3    10.5  5101.7   26.74
  5101.9   26.83 5101.99   26.83  5102.1   26.83  5102.2   26.83  5103.1   26.83
  5126.3   30.37  5167.3   30.28 5223.89   30.25    5224   30.25 5224.11   30.25
  5226.2   30.25  5252.2   30.24  5298.4   30.36  5357.2   30.56  5387.5   30.67
  5433.2    30.8  5453.6   30.86  5497.4   30.86  5498.2   30.85  5498.5   30.85
  5511.3   30.79  5529.7    30.7  5531.8    30.7    5560   30.98  5621.8    31.6
  5641.8    30.8    5690    31.9
BR U #Mann= 6
  4429.3      .2  4429.3      .1    4699     .14  4892.6     .07  5101.9      .1
    5690      .2
BR U Banks=4892.6,5101.9
BR D #Sta/Elev= 77
  4429.3   30.37  4482.1   30.42  4522.1   30.45  4539.3   30.47  4559.3   30.07
  4569.3   30.37  4599.3   29.57  4599.7   29.57  4609.7   29.67    4625   28.94
  4625.1   28.94  4634.4   28.69  4638.5   28.78  4655.4   28.89  4675.7   29.03
  4690.2   29.74  4696.6   29.94    4699   30.01  4702.2   30.11  4733.3   30.21
 4748.59   30.24  4748.7   30.24 4748.81   30.24  4769.5   30.28  4810.9   30.52
  4824.4    28.9  4825.5   28.77    4826   28.71  4836.1    27.4  4892.2   26.61
  4892.3   26.61 4892.41   26.61  4892.5   26.62  4892.6   26.62  4892.7   26.62
  4925.1   10.22  4931.4    9.75  4951.2    8.82  4971.6    8.58  4983.4    8.14
  4991.4    1.62  4995.8    -1.6    5006    -.57  5008.6    1.97  5017.4    5.37
  5023.7    5.78  5043.1    8.27  5064.2   10.36  5064.3   10.37  5101.7   26.61
  5101.9    26.7 5101.99    26.7  5102.1    26.7  5102.2    26.7  5103.1    26.7
  5126.3   30.24  5167.3   30.15 5223.89   30.12    5224   30.12 5224.11   30.12
  5226.2   30.12  5252.2   30.11  5298.4   30.23  5357.2   30.43  5387.5   30.54
  5433.2   30.67  5453.6   30.73  5497.4   30.73  5498.2   30.72  5498.5   30.72
  5511.3   30.66  5529.7   30.57  5531.8   30.57    5560   30.85  5621.8   31.47
  5641.8   30.67    5690   31.77
BR D #Mann= 6
  4429.3      .2  4429.3      .1    4699     .14  4892.6     .07  5101.9      .1
    5690      .2
BR D Banks=4892.6,5101.9
BC Design=,, 0 ,, 0 ,,,,,,
BC HTab HWMax=31.95
BC Use User HTab Curves=0
BC User HTab FreeFlow(D)= 0

Type RM Length L Ch R = 1 ,1447.5  ,437.7,437.7,437.7
BEGIN DESCRIPTION:
Downstream Section of Bridge/Culvert/Weir
END DESCRIPTION:
XS GIS Cut Line= 6
      3173045.26     13857555.93       3173007.6     13857862.25
      3172984.71       13858010.      3172928.53     13858218.08
       3172822.4     13858496.92      3172739.12     13858773.26
#Sta/Elev= 30
  4429.3   30.37  4539.3   30.47  4559.3   30.07  4569.3   30.37  4599.3   29.57
  4609.7   29.67  4634.4   28.69  4675.7   29.03    4699   30.01  4810.9   30.52
  4836.1    27.4  4892.6   26.62  4925.1   10.22  4951.2    8.82  4983.4    8.14
  4991.4    1.62  4995.8    -1.6    5006    -.57  5008.6    1.97  5017.4    5.37
  5023.7    5.78  5043.1    8.27  5064.3   10.37  5101.9    26.7  5126.3   30.24
  5252.2   30.11  5531.8   30.57  5621.8   31.47  5641.8   30.67    5690   31.77
#Mann= 6 , 1 , 0
  4429.3      .2       0  4429.3      .1       0    4699     .14       0
  4892.6     .07       0  5101.9      .1       0    5690      .2       0
#XS Ineff= 2 , 0
       0    4883    28.7    5112       0    30.1
Permanent Ineff=
       F       F
Bank Sta=4892.6,5101.9
XS Rating Curve= 0 ,0
Exp/Cntr=0.5,0.3

Type RM Length L Ch R = 1 ,1009.8  ,0,0,0
BEGIN DESCRIPTION:
Cross Section 1009.8
END DESCRIPTION:
XS GIS Cut Line= 4
      3172718.23     13857793.06      3172684.49     13857818.15
      3172474.09     13858095.87      3172341.88     13858497.19
#Sta/Elev= 29
    4789    31.2    4829    30.1  4833.5    30.2  4920.6   30.03  4951.8   26.17
  4970.3     7.6    4984    4.84  4989.7    1.91  4991.7    -.73  4995.6   -1.39
    5001    -.95  5004.8   -1.68  5010.3    1.85  5012.9    4.36  5031.8    7.18
    5102    8.17  5152.9   17.73  5163.3   22.24  5173.5    26.6    5182      27
    5282    30.7    5312      28    5342    27.4    5372    28.8    5452    29.4
    5462    29.1    5562    29.1    5572    28.9    5602      30
#Mann= 3 , 1 , 0
    4789      .1       0  4951.8     .07       0  5152.9     .14       0
Bank Sta=4951.8,5152.9
XS Rating Curve= 0 ,0
Exp/Cntr=0.3,0.1
LCMann Table=0

Chan Stop Cuts=-1
Use User Specified Reach Order=0
Composite Channel Slope=5